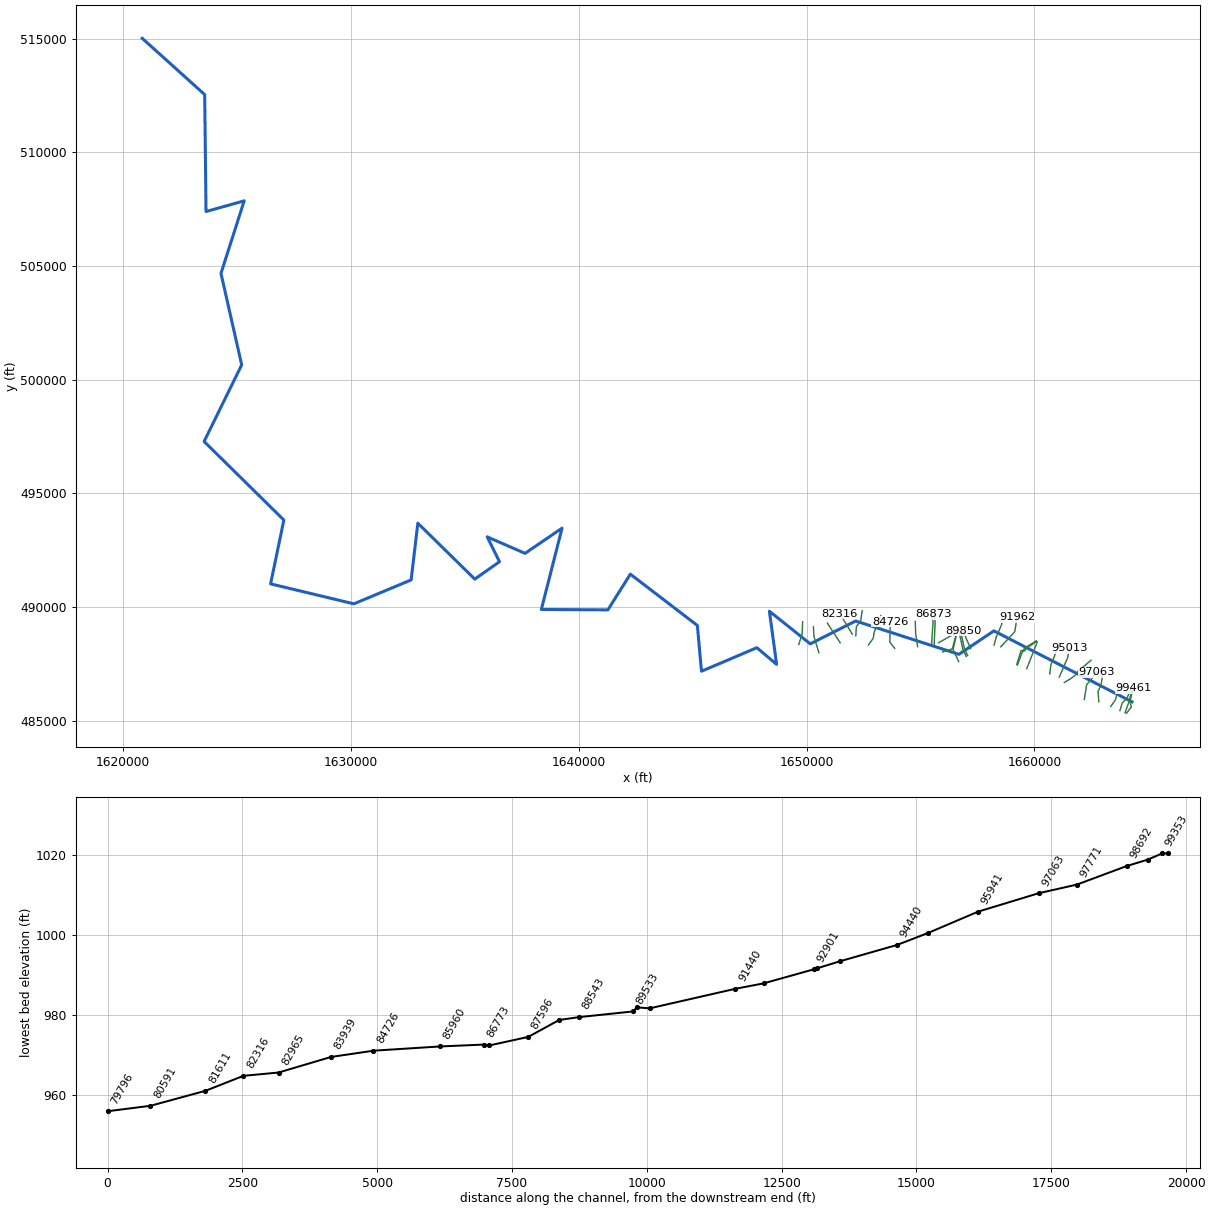
--- GraveCk1.prj (project) ---

Proj Title=GraveCk1
Current Plan=p01
Default Exp/Contr=0,0
English Units
Geom File=g01
Flow File=f01
Plan File=p01
BEGIN DESCRIPTION:
---------- MODELED AS PART OF WVEM CTP PROGRAM, 2025----------
Stream Name: Grave Creek
Flood Zone: AFH
Marshall County, WV
HEC-RAS Version: RAS 6.6
Vertical Datum: NAVD88
Projection: NAD 1983 StatePlane West Virginia N FIPS 4701 (US Feet)
Terrain: 1-meter West Virginia FEMA R3 South Central (collected 2018-2019)
Land Use: 2024 NLCD
Hydrologic Method:
Duda et al., "Estimation of magnitude and frequency of floods for rural, unregulated streams in and near Virginia and West Virginia." September 8, 2025.
Additional Model Notes:
None
END DESCRIPTION:
DSS Export Rating Curves= 0
DSS Export Rating Curve Sorted= 0
DSS Export Volume Flow Curves= 0
DXF OffsetX= 0
DXF OffsetY= 0
DXF ScaleX= 0
DXF ScaleY= 0

--- GraveCk1.p01 (plan) ---

Plan Title=Floodplain
Program Version=6.60
Short Identifier=Floodplain
Geom File=g01
Flow File=f01
Subcritical Flow
K Sum by GR= 0
Std Step Tol= 0.01
Critical Tol= 0.01
Num of Std Step Trials= 20
Max Error Tol= 0.3
Flow Tol Ratio= 0.001
Split Flow NTrial= 30
Split Flow Tol= 0.02
Split Flow Ratio= 0.02
Log Output Level= 0
Friction Slope Method= 1
Unsteady Friction Slope Method= 2
Unsteady Bridges Friction Slope Method= 1
Parabolic Critical Depth
Global Vel Dist= 0 , 0 , 0
Global Log Level= 0
CheckData=False
Encroach Param=-1 ,0,0, 0
Flow Ratio Tolerance=0.1
Flow Ratio Min Ratio=0.5
Flow Ratio Max Ratio=4
Flow Ratio Max Iterations= 10
Mapping Interval=1HOUR
Computation Time Step Use Courant=        0
Computation Time Step Use Time Series=    0
Computation Time Step Count To Double=0
Computation Time Step Max Doubling=0
Computation Time Step Max Halving=0
Computation Time Step Residence Courant=0
Run HTab= 0
Run UNet= 0
Run Sediment= 0
Run PostProcess= 0
Run WQNet= 0
Run RASMapper=-1
UNET Theta= 0
UNET Theta Warmup= 0
UNET ZTol= 0
UNET ZSATol= 0
UNET MxIter= 0
UNET Max Iter WO Improvement= 0
UNET MaxInSteps= 0
UNET DtIC= 0
UNET DtMin= 0
UNET MaxCRTS= 0
UNET WFStab= 0
UNET SFStab= 0
UNET WFX= 1
UNET SFX= 1
UNET Gravity=32.17405
UNET 1D Methodology=Finite Difference
UNET DSS MLevel= 1
UNET Pardiso=0
UNET DZMax Abort= 0
UNET Use Existing IB Tables= 0
UNET Froude Reduction=False
UNET Froude Limit= 0
UNET Froude Power= 0
UNET D1 Cores= 0
UNET WindReference=Eulerian
UNET WindDragFormulation=Hsu (1988)
UNET D2 Coriolis=0
UNET D2 Cores= 0
UNET D2 Theta= 1
UNET D2 Theta Warmup= 1
UNET D2 Z Tol= 0.01
UNET D2 Volume Tol= 0.01
UNET D2 Max Iterations= 20
UNET D2 Advanced Convergence=0
UNET D2 WS Max Tol=0.15
UNET D2 WS RMS Tol=0.002
UNET D2 WS Stall Tol=1
UNET D2 Equation= 0
UNET D2 RampUpFraction=0.1
UNET D2 TimeSlices= 1
UNET D2 Turbulence Formulation=Non-Conservative (original)
UNET D2 Eddy Viscosity=0.3
UNET D2 Transverse Eddy Viscosity=0.1
UNET D2 Smagorinsky Mixing=0
UNET D2 BCVolumeCheck=0
UNET D2 Cores=0
UNET D2 SolverType=PARDISO (Direct)
UNET D2 Minimum Iterations= 3
UNET D2 Maximum Iterations= 30
UNET D2 Restart Number= 10
UNET D2 Relaxation Coeff=1.3
UNET D2 SOR Precondition Iterations= 10
UNET D2 ILUT Maximum Fill= 8
UNET D2 ILUT Tolerance=1E-08
UNET D2 Convergence Tolerance=0.00001
PS Theta= 1
PS WS Tol= 0.01
PS Volume Tol= 0.01
PS Max Iterations= 20
PS Equation= 0
PS Advance Time Step=-1
PS Target Courant=0.9
PS Time Slices= 1
PS Iterate With 2D=0
PS Project Initial WSE from DS=-1
PS Ramp Up Initial WSE from US=-1
PS Cores=0
UNET D1D2 MaxIter= 0
UNET D1D2 ZTol=0.01
UNET D1D2 QTol=0.1
UNET D1D2 MinQTol=1
Write IC File= 0
Write IC File at Fixed DateTime=0
Write IC File at Sim End=0
Echo Input=False
Echo Parameters=False
Echo Output=False
Write Detailed= 0
HDF Write Warmup=0
HDF Write Time Slices=0
HDF Flush=0
HDF Compression= 1
HDF Chunk Size= 1
HDF Spatial Parts= 1
HDF Use Max Rows=0
HDF Fixed Rows= 1
Calibration Method= 0
Calibration Iterations= 20
Calibration Max Change=0.05
Calibration Tolerance=0.2
Calibration Maximum=1.5
Calibration Minimum=0.5
Calibration Optimization Method= 1
WQ AD Non Conservative
WQ ULTIMATE=-1
WQ Max Comp Step=1HOUR
WQ Output Interval=15MIN
WQ Output Selected Increments= 0
WQ Create Restart=0
WQ Fixed Restart=0
WQ System Summary=0
WQ Write To DSS=0
Sorting and Armoring Iterations= 10
XS Update Threshold= 0.02
Bed Roughness Predictor= 0
Processes Affected by Predictor=Sediment Only
Hydraulics Update Threshold= 0.02
Energy Slope Method= 1
Volume Change Method= 1
Sediment Retention Method= 0
Sediment TS Multiplier= 1
Warm Up Method= 0
XS Weighting Method= 0
Number of US Weighted Cross Sections= 1
Number of DS Weighted Cross Sections= 1
Upstream XS Weight=0
Main XS Weight=1
Downstream XS Weight=0
Number of DS XS's Weighted with US Boundary= 1
Upstream Boundary Weight= 1
Weight of XSs Associated with US Boundary= 0
Number of US XS's Weighted with DS Boundary= 1
Downstream Boundary Weight= 0.5
Weight of XSs Associated with DS Boundary= 0.5
Percentile Method= 0
Sediment Output Level= 3
Mass or Volume Output= 0
Output Increment Type= 1
Profile and TS Output Increment= 1
Transport Output Increment 1
XS Output Flag= 0
XS Output Increment= 10
Read HDF5 Sediment Hotstart= 0
Sediment Hotstart Type= 0
Write Gradation File= 0
Read Gradation Hotstart= 0
Write HDF5 File= 1
Write Binary Output= 1
Write DSS Sediment File= 0
DSS Sediment Output Type= 1
SV Curve= 0
Specific Gage Flag= 0
Subcell Erosion Methods= 0
Subcell Deposition Methods= 0
Advection Scheme= 1
Matrix Solver= 0
Implicit Weighting Factor= 1
Maximum Outer Loop Convergence Iterations= 5
Convergence Maximum Absolute= 0.001
Convergence RMSE= 0.0001
Grain Fractions Max Abs Error= 0.001
Max Subgrid Regions= 1
Max Subgrid Length Scale= 3.402823E+38
Initial Layer Thickness= 3
Min Layer Thickness= 0.1
Max Layer Thickness= 6
Number of Layers= 5

--- GraveCk1.f01 (steady flow) ---

Flow Title=Flow
Program Version=6.60
Number of Profiles= 1
Profile Names=P100yr
River Rch & RM=GraveCk1,Main,99461
    3660
River Rch & RM=GraveCk1,Main,89850
    4140
River Rch & RM=GraveCk1,Main,78638
    4600
River Rch & RM=GraveCk1,Main,65095
    5150
River Rch & RM=GraveCk1,Main,40500
    5740
River Rch & RM=GraveCk1,Main,24339
    6510
Boundary for River Rch & Prof#=GraveCk1,Main            , 1
Up Type= 0
Dn Type= 3
Dn Slope=0.001999
DSS Import GetInterval= 0
DSS Import GetPeak= 0
DSS Import FillOption= 0

--- GraveCk1.g01 (geometry) ---

Geom Title=Geometry
Program Version=6.60

River Reach=GraveCk1        ,Main
Reach XY= 30
     1664284.468      485824.566     1658220.742      488946.915
     1656684.893      487915.276     1652151.054      489381.498
     1650159.169      488376.797     1648366.368       489811.58
     1648680.996      487476.272     1647815.272      488207.028
     1645383.957      487171.532     1645203.345       489185.33
     1642261.122      491442.115     1641274.275      489870.864
     1638353.522      489888.786     1639263.007      493465.556
     1637637.492      492357.168     1635976.947      493082.935
     1636515.922      491988.415     1635430.847      491224.349
       1632931.3      493684.675     1632637.741      491188.232
     1630123.816       490137.27     1626467.379      491015.337
     1627050.157      493822.891     1623549.354      497278.037
     1625198.642      500648.325     1624289.182      504673.521
     1625309.725      507864.984     1623633.228      507394.194
      1623574.26       512538.51     1620832.795      515012.705

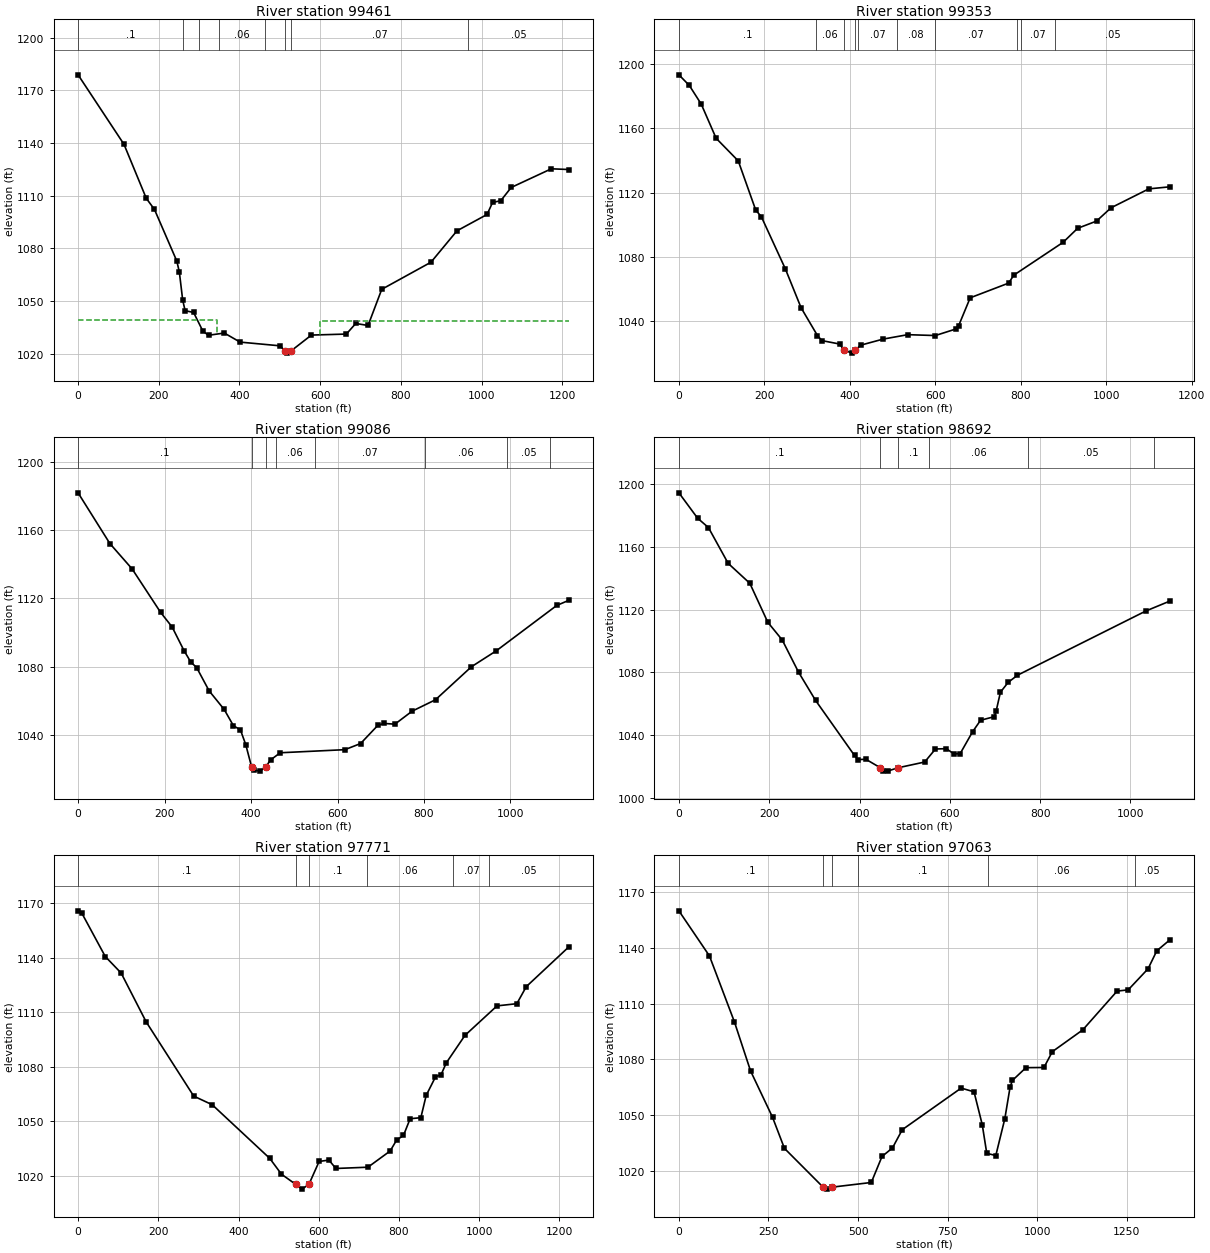
Type RM Length L Ch R = 1 ,99461   ,118.4,108.8,101.9
XS GIS Cut Line= 4
1664040.57809576485318.2837427941664255.34530017485597.920646795
1664189.97648212485843.5877464541664344.05038548486433.238366939
#Sta/Elev= 30
       0 1178.92   113.9 1139.28   169.1 1108.52   189.3 1102.24   244.7 1072.82
     251  1066.6   259.3  1050.6   265.3 1044.54   286.3 1043.53   309.5 1032.83
   323.3 1030.52   362.5  1031.8   401.6 1026.63   501.7 1024.49   511.8 1021.61
   518.6 1020.35  527.821021.598   578.4 1030.64     665 1031.21   688.3 1037.25
   718.8  1036.1   752.7 1056.71   874.8 1072.16   939.2 1090.04  1013.8 1099.36
  1027.4  1106.2  1047.7 1107.19  1073.6 1114.74  1173.1 1125.38  1216.3 1124.97
#Mann= 8 ,-1,0
       0      .1       0     260     .06       0     300     .07       0
     350     .06       0  462.59     .07       0   511.8    .045       0
  527.82     .07       0  966.81     .05       0
#XS Ineff= 2 , 0
          343.68 1039.44  599.62          1038.8
Permanent Ineff=
       F       F
Bank Sta=511.8,527.82
XS Rating Curve= 0 ,0
Exp/Cntr(USF)=0,0
Exp/Cntr=0.3,0.1

Type RM Length L Ch R = 1 ,99353   ,270,266.7,261.3
XS GIS Cut Line= 3
1663978.08829878485345.039467349 1664140.7397678485796.849103524
1664314.61479143486441.814279887
#Sta/Elev= 30
       0 1193.18    24.4 1186.58    52.3 1174.98    87.1 1153.79   138.9 1139.73
   179.9 1109.09   192.8 1105.14   249.2 1072.61   285.9 1048.53   324.2 1031.27
   334.7 1028.12   376.5 1025.98  385.711022.431   404.4 1020.35   413.21022.443
   426.1 1025.34   477.7 1029.05   535.5 1031.81   600.1 1031.27   647.6  1035.3
   654.4 1037.27   681.6  1054.7   771.7 1063.85   783.5 1068.74   899.1 1089.18
     933 1097.86   977.2 1102.34  1011.2 1110.61  1099.5 1122.35  1148.2 1123.62
#Mann= 10 ,-1,0
       0      .1       0     320     .06       0  385.71    .045       0
   413.2     .06       0     420     .07       0   510.2     .08       0
   600.2     .07       0   790.2     .06       0   800.2     .07       0
   880.2     .05       0
Bank Sta=385.71,413.2
XS Rating Curve= 0 ,0
Exp/Cntr(USF)=0,0
Exp/Cntr=0.3,0.1

Type RM Length L Ch R = 1 ,99086   ,384.6,394,400.2
XS GIS Cut Line= 4
1663753.96591712485438.5604840241663853.91734827485771.051979503
1664072.17863672486011.7513443291664265.96202365 486431.95532021
#Sta/Elev= 30
       0 1181.86    73.6 1152.12     125 1137.27   190.9  1111.8   217.5 1103.25
   244.9 1089.45   260.7 1082.69   274.2 1079.49   303.1 1065.82   337.9 1054.93
   359.2 1045.45   375.5 1042.91   387.7  1034.4  401.291021.292   405.7 1019.39
   420.7  1018.8  433.851021.279   445.1 1025.33   467.4 1029.56     617 1031.37
   653.4 1034.97     693 1045.55   707.3 1046.75   732.7 1046.31   772.4 1053.91
   826.6 1060.62   909.7 1079.96   967.1 1089.28    1107 1115.88  1134.8 1118.86
#Mann= 8 ,-1,0
       0      .1       0  401.29    .045       0  433.85      .1       0
  457.19     .06       0  547.19     .07       0  802.11     .06       0
  992.11     .05       0 1092.11      .1       0
Bank Sta=401.29,433.85
XS Rating Curve= 0 ,0
Exp/Cntr(USF)=0,0
Exp/Cntr=0.3,0.1

Type RM Length L Ch R = 1 ,98692   ,904.9,921.4,898.7
XS GIS Cut Line= 3
1663349.25324186485612.6144825661663549.55963851485903.470346186
1663760.84172812486605.914696062
#Sta/Elev= 30
       0  1194.4    41.5 1178.23    65.4 1172.29   109.1 1149.49   157.1 1136.78
   196.9 1111.97   228.8 1100.72   264.9 1080.24   302.6 1062.25   388.9 1027.15
   396.9 1024.53   414.1 1024.73   446.31019.298   451.7  1017.3     462 1017.18
   485.11019.297   544.3 1022.98   568.2 1031.28   592.2 1031.47   609.3 1028.13
     623 1028.38   650.4 1042.25   668.1 1049.56   698.4 1051.86   702.4 1055.23
   712.1 1067.45   729.2 1073.69   749.8 1078.25  1034.2 1119.16  1086.7  1125.4
#Mann= 6 ,-1,0
       0      .1       0   446.3    .045       0   485.1      .1       0
  553.16     .06       0  773.16     .05       0 1053.16     .06       0
Bank Sta=446.3,485.1
XS Rating Curve= 0 ,0
Exp/Cntr(USF)=0,0
Exp/Cntr=0.3,0.1

Type RM Length L Ch R = 1 ,97771   ,697.4,707.3,706.9
XS GIS Cut Line= 4
1662827.21732503485828.5262244271662791.54632289486286.761405791
1662915.02286877486533.7144975441663000.08448926487013.901064842
#Sta/Elev= 30
       0 1165.76     9.3  1164.5    67.8 1140.61   107.3 1131.53   169.8 1104.62
   288.3 1063.77   334.4 1059.02   477.8 1029.51   507.1 1020.78   542.21015.253
   558.5 1012.56   575.71015.246     601  1027.8   625.4 1028.55   642.8 1023.93
   722.7 1024.63     778 1033.54   794.2 1039.55   811.3 1042.13   827.9  1051.3
   854.6  1051.9   867.9 1064.15   891.1 1074.33   905.3 1075.65   917.9 1082.02
   964.5 1097.17  1044.5 1113.44  1093.9 1114.64  1117.5 1124.03  1223.4 1145.88
#Mann= 6 ,-1,0
       0      .1       0   542.2    .045       0   575.7      .1       0
  719.62     .06       0  935.72     .07       0 1025.72     .05       0
Bank Sta=542.2,575.7
XS Rating Curve= 0 ,0
Exp/Cntr(USF)=0,0
Exp/Cntr=0.3,0.1

Type RM Length L Ch R = 1 ,97063   ,1105.7,1122.4,1095.6
XS GIS Cut Line= 3
1662190.62713296 485930.05138437 1662292.1522929 486574.87334617
 1662739.4117813487134.633687477
#Sta/Elev= 30
       0 1159.75    85.3 1135.54     155 1100.12     200 1073.83   261.3 1048.97
   294.5 1032.29   402.41011.473   414.1 1010.41 426.9871011.459   536.9 1013.98
   566.8 1027.94     596 1032.51   623.3  1042.3   787.7 1064.63   823.6 1062.62
   846.5 1045.01   859.1 1029.64   884.3 1028.43   909.5 1048.18     924 1064.95
   930.5 1068.71   968.5 1075.59  1018.7 1075.68  1042.1 1084.18  1127.1 1095.88
  1222.8 1116.67  1253.8 1117.34  1309.2 1128.65  1333.6  1138.3  1369.3 1144.06
#Mann= 6 ,-1,0
       0      .1       0   402.4    .045       0 426.987     .05       0
     500      .1       0  862.77     .06       0 1272.77     .05       0
Bank Sta=402.4,426.987
XS Rating Curve= 0 ,0
Exp/Cntr(USF)=0,0
Exp/Cntr=0.3,0.1

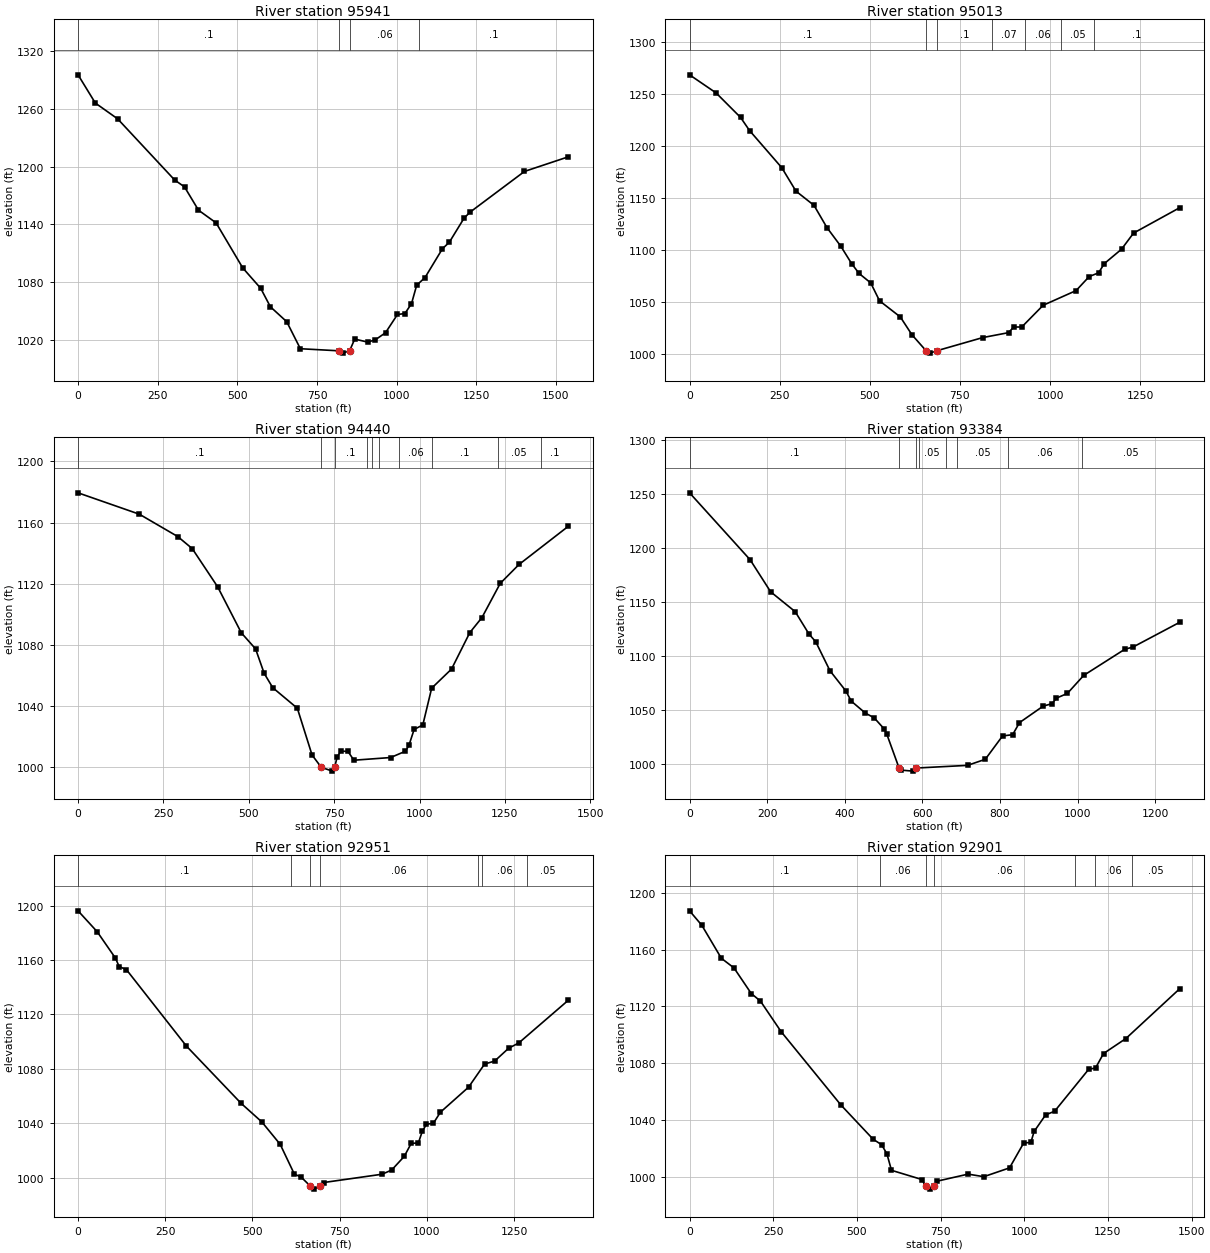
Type RM Length L Ch R = 1 ,95941   ,906.8,927.5,924.3
XS GIS Cut Line= 6
  1661313.458737486679.4019389151661600.21636559486850.923577502
1661792.17562734486996.1923158321661865.92679217487085.713462248
1661914.26068501487169.8898030821662486.05055192487655.784172505
#Sta/Elev= 30
       0 1295.58    54.2 1266.21   124.3 1249.72   303.2 1186.06   334.1 1178.91
     378 1154.65   433.2 1141.46     517 1094.51   573.3 1073.28   603.7 1054.06
     655 1038.51   697.7 1010.41  819.211008.215   830.1 1005.82  852.351008.269
   868.3 1020.46   909.2 1017.29   933.2 1019.71     965 1027.06  1002.6  1046.1
  1025.6 1046.99  1046.5 1057.25  1062.8 1076.53    1089 1084.52  1143.8 1114.58
  1165.2 1121.24  1211.8 1146.48  1230.4 1152.61  1401.2 1195.01  1538.6 1210.19
#Mann= 4 ,-1,0
       0      .1       0  819.21    .045       0  852.35     .06       0
 1070.75      .1       0
Bank Sta=819.21,852.35
XS Rating Curve= 0 ,0
Exp/Cntr(USF)=0,0
Exp/Cntr=0.3,0.1

Type RM Length L Ch R = 1 ,95013   ,571.4,573.7,573
XS GIS Cut Line= 3
1661093.05783628486917.8637513821661457.99962742487762.992109827
1661543.06124792488193.788058774
#Sta/Elev= 30
       0  1268.4    73.6 1250.98   141.5 1227.38   166.5 1214.71   255.8 1178.99
   295.1 1156.45   345.2 1142.73   380.9 1121.43   419.7 1103.32   449.6 1086.63
   470.2 1077.18   502.4 1068.12     527 1050.84   584.6 1035.32   616.8 1018.19
   656.11002.747   666.8  1000.5   685.21002.725   813.3 1015.48   884.8 1020.21
   899.1 1025.66   921.4 1025.63   980.7 1046.55  1072.2 1060.73  1108.5 1074.23
  1134.5 1077.78  1150.4 1086.69  1198.1 1100.53  1231.5 1116.06  1359.7 1140.52
#Mann= 7 ,-1,0
       0      .1       0   656.1    .045       0   685.2      .1       0
     840     .07       0  930.56     .06       0 1030.56     .05       0
 1120.56      .1       0
Bank Sta=656.1,685.2
XS Rating Curve= 0 ,0
Exp/Cntr(USF)=0,0
Exp/Cntr=0.3,0.1

Type RM Length L Ch R = 1 ,94440   ,1047.8,1055.5,1052.6
XS GIS Cut Line= 6
1660674.78875451 487056.019624011660695.70734784487265.775438085
 1660730.4405461487472.9275828451660763.34074275487564.965784594
1660831.39014734487717.0842467551661094.87091959 488419.69668667
#Sta/Elev= 30
       0 1179.45   179.6 1165.47     292 1150.86   334.4 1142.99   408.9 1117.98
   478.1 1087.94   519.9 1077.42   545.1 1061.42   570.3 1052.04   642.2 1038.62
   685.3 1008.06   712.31000.005   744.8  997.51   751.41000.038   758.8  1006.7
   769.4 1010.59   790.4 1010.41   807.9 1004.64   915.4  1006.4   958.8 1010.52
     969 1014.31   984.2 1024.76  1009.7 1027.71  1035.6 1051.74  1093.8 1064.24
  1147.3 1088.06  1182.8 1097.87  1236.5 1120.28  1291.4  1132.6  1435.7 1157.56
#Mann= 10 ,-1,0
       0      .1       0   712.3    .045       0   751.4      .1       0
  845.34     .05       0  860.34     .06       0  880.34     .05       0
  940.34     .06       0 1037.84      .1       0 1228.46     .05       0
 1356.12      .1       0
Bank Sta=712.3,751.4
XS Rating Curve= 0 ,0
Exp/Cntr(USF)=0,0
Exp/Cntr=0.3,0.1

Type RM Length L Ch R = 1 ,93384   ,449.2,433.3,421.9
XS GIS Cut Line= 2
1659662.67762314487282.9706992691660122.83124588488459.278903873
#Sta/Elev= 30
       0 1251.35   156.1 1189.32   208.9 1159.64   272.3 1141.18   307.5 1120.61
   325.2 1113.26   361.7 1086.53   402.7 1067.75   416.7 1058.29   452.9 1047.25
   475.7 1042.84   501.3 1032.63   507.8 1028.11   539.9996.2617   544.1  994.42
   575.3  993.45   584.2996.3161   716.2  998.78     762 1004.42   806.4 1026.03
   832.5 1027.24   850.1  1038.4   911.2 1053.71     934 1055.96   945.2  1061.1
   973.4 1065.43  1015.6 1082.17  1121.4 1106.38  1142.5 1108.42  1263.1 1131.41
#Mann= 8 ,-1,0
       0      .1       0   539.9    .045       0   584.2      .1       0
     590     .05       0     660      .1       0     690     .05       0
     820     .06       0    1010     .05       0
Bank Sta=539.9,584.2
XS Rating Curve= 0 ,0
Exp/Cntr(USF)=0,0
Exp/Cntr=0.3,0.1

Type RM Length L Ch R = 1 ,92951   ,49.1,50.3,50.4
XS GIS Cut Line= 6
 1659256.1806606487445.8401692211659474.91565733488034.966427064
1659555.11848946488064.1310932941659607.61488867488107.878092639
1659632.40485497488169.1238917221660090.29011478488487.018753627
#Sta/Elev= 30
       0 1196.18    54.8 1180.84   107.3 1161.39   117.8 1155.24   138.8 1152.92
   310.3  1096.9   467.7 1054.67   527.2 1040.98   579.6 1024.57   620.4 1002.59
   638.9 1000.69   665.2994.0928   676.5  991.66   693.8994.0853   704.4  996.52
   871.7 1002.61   899.2 1005.69   935.3 1015.72   955.1 1025.21   975.9 1025.66
   987.2 1034.29     999  1039.3    1019 1040.14  1039.1 1048.21  1119.7 1066.59
  1165.7 1083.58  1194.5 1085.77  1234.7 1095.22  1263.5 1099.04  1405.6 1130.44
#Mann= 7 ,-1,0
       0      .1       0     610     .06       0   665.2    .045       0
   693.8     .06       0 1148.17     .05       0 1158.17     .06       0
 1288.17     .05       0
Bank Sta=665.2,693.8
XS Rating Curve= 0 ,0
Exp/Cntr(USF)=0,0
Exp/Cntr=0.3,0.1

Type RM Length L Ch R = 1 ,92901   ,907.6,938.7,928.5
XS GIS Cut Line= 6
1659225.55776106487472.0883688281659416.31620483488087.636989251
1659465.27849159488079.4766081241659514.86849998488097.680535253
1659582.66243549488198.7437168981660088.02512864488508.972335623
#Sta/Elev= 30
       0 1187.21    36.6 1177.05      95 1153.83   132.8 1147.03   184.3 1129.05
   211.8  1123.7   273.6  1102.2   452.2 1050.62   548.4 1026.55   573.9 1022.65
   589.6 1016.26   603.3 1004.68   694.1   998.2   705.6 993.585   717.7  991.44
   731.1 993.592   740.7   997.1   832.3    1002     879 1000.18     956 1006.39
   998.3 1023.92  1019.7 1024.28  1029.4    1032  1063.8 1043.65  1090.8 1046.26
  1192.5 1075.74  1212.9 1076.63  1236.8 1086.83  1303.6 1097.37  1464.6 1132.45
#Mann= 7 ,-1,0
       0      .1       0     570     .06       0   705.6    .045       0
   731.1     .06       0 1151.58      .1       0 1211.58     .06       0
 1321.58     .05       0
Bank Sta=705.6,731.1
XS Rating Curve= 0 ,0
Exp/Cntr(USF)=0,0
Exp/Cntr=0.3,0.1

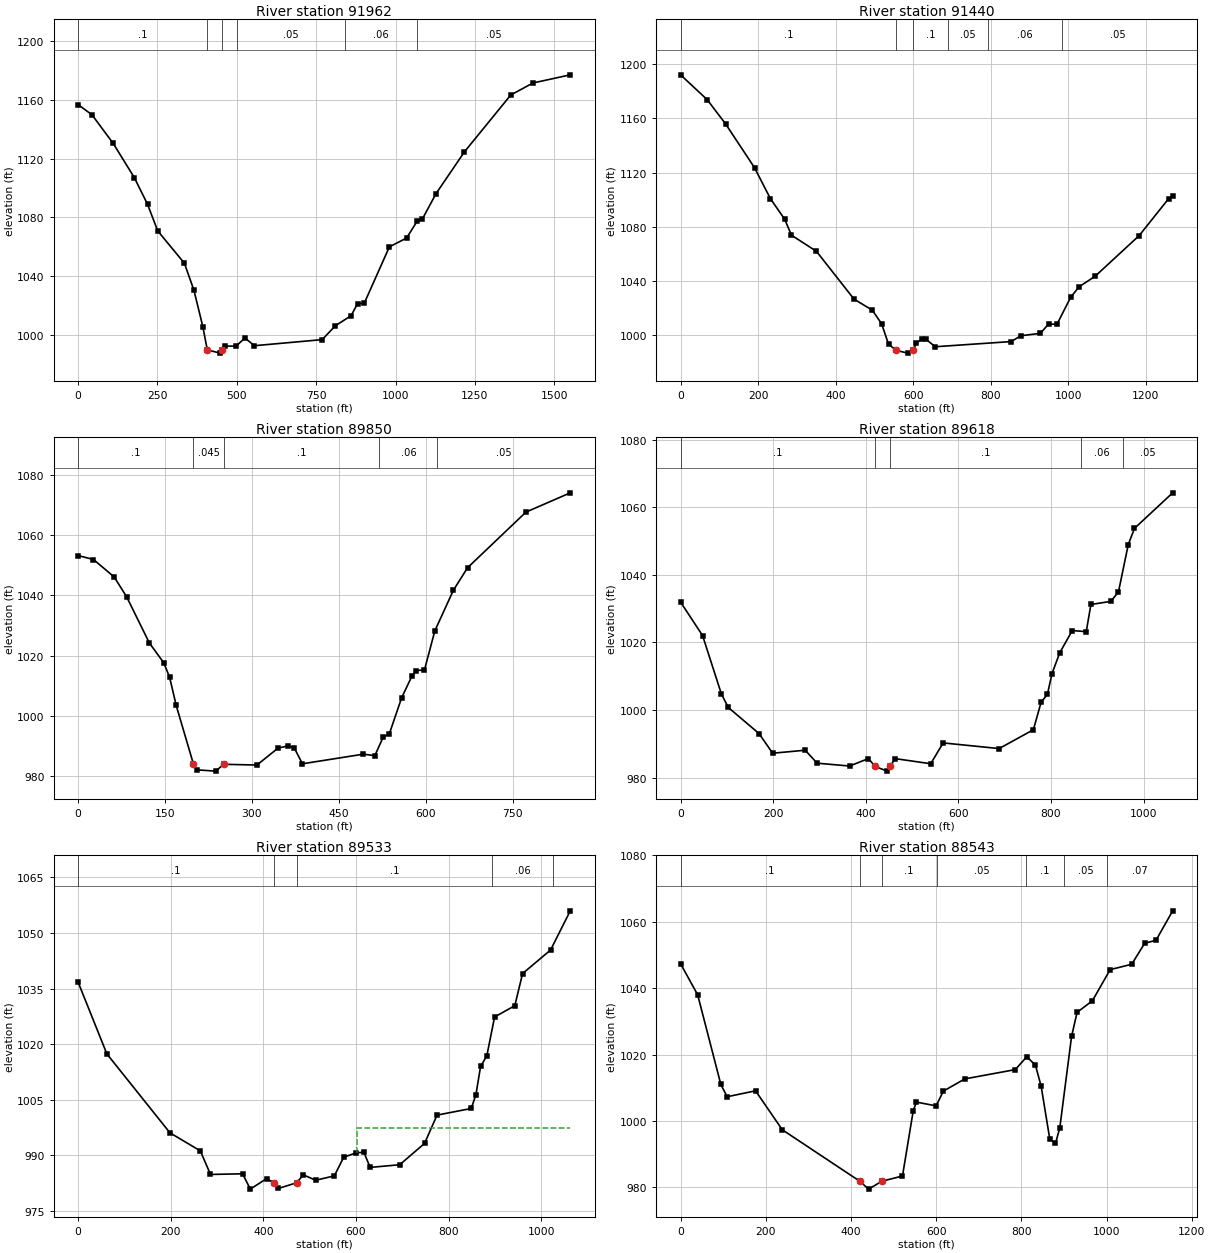
Type RM Length L Ch R = 1 ,91962   ,507.3,522.2,525.2
XS GIS Cut Line= 3
1658524.74568204488245.9226003661659139.38448819  488912.6959481
1659235.42180165489549.286140174
#Sta/Elev= 30
       0 1156.58    43.7 1149.65   110.6  1130.2   176.9 1107.06   218.7  1088.9
   250.7 1070.88   334.8 1048.92   364.9 1030.53   392.8  1005.9   406.9990.1389
   447.2  987.91   454.8990.1517   462.5  992.73   497.3   992.6   525.6  998.19
   555.3  992.95   768.9  997.07   810.7 1006.53   860.2 1013.33   880.4 1021.59
   901.3 1021.66   980.6 1060.04  1034.8 1066.02  1067.9 1077.37  1084.5 1078.92
  1127.8 1096.22  1217.2 1124.56  1363.2 1163.13  1432.9 1171.25  1550.6  1176.8
#Mann= 6 ,-1,0
       0      .1       0   406.9    .045       0   454.8      .1       0
     500     .05       0     840     .06       0 1066.84     .05       0
Bank Sta=406.9,454.8
XS Rating Curve= 0 ,0
Exp/Cntr(USF)=0,0
Exp/Cntr=0.3,0.1

Type RM Length L Ch R = 1 ,91440   ,1550.5,1589.4,1588.5
XS GIS Cut Line= 6
1658229.63855642488323.4165271931658325.05657734488678.654830173
1658362.46168625488758.0631359221658391.73820251 488827.12861459
1658567.57774584489244.7439210861658598.97074738489528.592297345
#Sta/Elev= 30
       0 1192.22    68.5 1173.92   116.5 1155.82   190.8 1123.58   231.6 1100.79
   268.9 1085.33   285.9 1073.74   350.5 1061.79   447.2 1026.53   494.5 1018.31
   518.6 1008.23   536.4  993.21   556.4988.5494   586.3  986.56   600.5  988.53
   607.6  993.76   622.2  997.07   633.3   996.7   656.9  991.28   852.7   995.1
   877.7  999.41     928 1001.17   949.4  1008.1   970.7  1007.8    1006 1027.69
  1027.8 1035.58    1069 1043.29  1182.9 1073.43  1258.8  1100.7  1269.3 1102.52
#Mann= 6 ,-1,0
       0      .1       0   556.4    .045       0   600.5      .1       0
  690.62     .05       0  793.12     .06       0  983.75     .05       0
Bank Sta=556.4,600.5
XS Rating Curve= 0 ,0
Exp/Cntr(USF)=0,0
Exp/Cntr=0.3,0.1

Type RM Length L Ch R = 1 ,89850   ,236.1,232.7,232.4
XS GIS Cut Line= 2
1657199.96243935488165.1470085231656864.10623456488945.518778463
#Sta/Elev= 30
       0 1053.26    26.5 1051.95    62.2 1046.15    83.6 1039.61   122.9 1024.25
   147.9 1017.62   157.9 1012.86   169.3 1003.48  199.13983.9625     205  982.11
   237.2  981.68   251.5  983.95   308.6   983.7   345.1  989.32   362.2  990.05
   372.9  989.45   387.2  984.12   492.5  987.31   512.2  986.82   526.5  992.94
   537.4  994.16   558.6 1006.11   576.5 1013.33   583.6 1015.05   597.9 1015.31
   615.8 1028.27   647.9 1041.78   672.2  1049.2     773 1067.68   849.6 1074.09
#Mann= 5 ,-1,0
       0      .1       0  199.13    .045       0   251.5      .1       0
     520     .06       0     620     .05       0
Bank Sta=199.13,251.5
XS Rating Curve= 0 ,0
Exp/Cntr(USF)=0,0
Exp/Cntr=0.3,0.1

Type RM Length L Ch R = 1 ,89618   ,79,84.4,79.7
XS GIS Cut Line= 3
1657071.75801488487861.7468127031656936.40105391488123.536099836
1656770.89131451488873.719598573
#Sta/Elev= 30
       0 1031.97    47.6 1022.04    88.2 1004.75     103 1000.77   169.4  993.04
     199  987.21   269.2   988.1     295  984.26   365.1  983.42   405.9  985.64
  419.86983.3084   446.2  981.91   453.2  983.31     463  985.62   540.3   984.1
   567.2  990.26   688.1  988.59     762  994.16   778.8 1002.34   792.3 1004.61
   802.3 1010.81   819.1 1016.97     846 1023.53   876.2  1023.2   886.3 1031.25
   929.3 1032.16   945.8 1034.97     967    1049   980.4 1053.78  1062.9  1064.3
#Mann= 5 ,-1,0
       0      .1       0  419.86    .045       0   453.2      .1       0
  864.71     .06       0  954.71     .05       0
Bank Sta=419.86,453.2
XS Rating Curve= 0 ,0
Exp/Cntr(USF)=0,0
Exp/Cntr=0.3,0.1

Type RM Length L Ch R = 1 ,89533   ,971.6,990.6,953.5
XS GIS Cut Line= 3
 1657005.7965166487826.0115466561656870.43955564 488087.80083379
1656704.92981624488837.984332526
#Sta/Elev= 30
       0 1036.71      62 1017.38   198.2  996.09   263.9  991.21   285.8  984.85
   355.1  985.03   371.9  980.89   406.9  983.73   422.3   982.6   432.4  981.07
  472.13982.6107   486.2  984.76     513  983.28   553.3  984.47   573.5  989.49
   600.4  990.69   617.2  990.83   630.6  986.75   694.5  987.47   748.2  993.23
   775.1 1000.86     849 1002.65   859.1 1006.37   869.2    1014   882.6 1016.84
   899.4 1027.33   943.1 1030.39   959.9 1039.06  1020.3  1045.4  1062.9 1055.98
#Mann= 5 ,-1,0
       0      .1       0   422.3    .045       0  472.13      .1       0
  894.71     .06       0 1024.71     .05       0
#XS Ineff= 2 , 0
                          603.03          997.32
Permanent Ineff=
       F       F
Bank Sta=422.3,472.13
XS Rating Curve= 0 ,0
Exp/Cntr(USF)=0,0
Exp/Cntr=0.3,0.1

Type RM Length L Ch R = 1 ,88543   ,415.7,372.5,334.1
XS GIS Cut Line= 3
1656676.71736915 487595.702292241656427.29474647488131.590501344
1656560.64941602488679.826365036
#Sta/Elev= 30
       0 1047.38    40.2    1038    94.6    1011   109.4 1007.31   176.1  1009.1
   238.8  997.37   420.6 981.885   441.4  979.49   472.5981.8593     521  983.44
   546.3 1003.14   553.6  1005.7     600 1004.56   616.9 1009.01   667.5 1012.69
   785.7 1015.48   812.7 1019.34     833 1016.88   846.5 1010.49   866.7  994.63
   880.2  993.24   890.4  998.04   917.9 1025.46   930.9 1032.73   966.8 1036.21
  1008.5 1045.59  1059.1 1047.21  1089.6 1053.53  1116.2 1054.44  1155.3  1063.3
#Mann= 7 ,-1,0
       0      .1       0   420.6    .045       0   472.5      .1       0
  601.09     .05       0  811.09      .1       0  901.09     .05       0
 1001.09     .07       0
Bank Sta=420.6,472.5
XS Rating Curve= 0 ,0
Exp/Cntr(USF)=0,0
Exp/Cntr=0.3,0.1

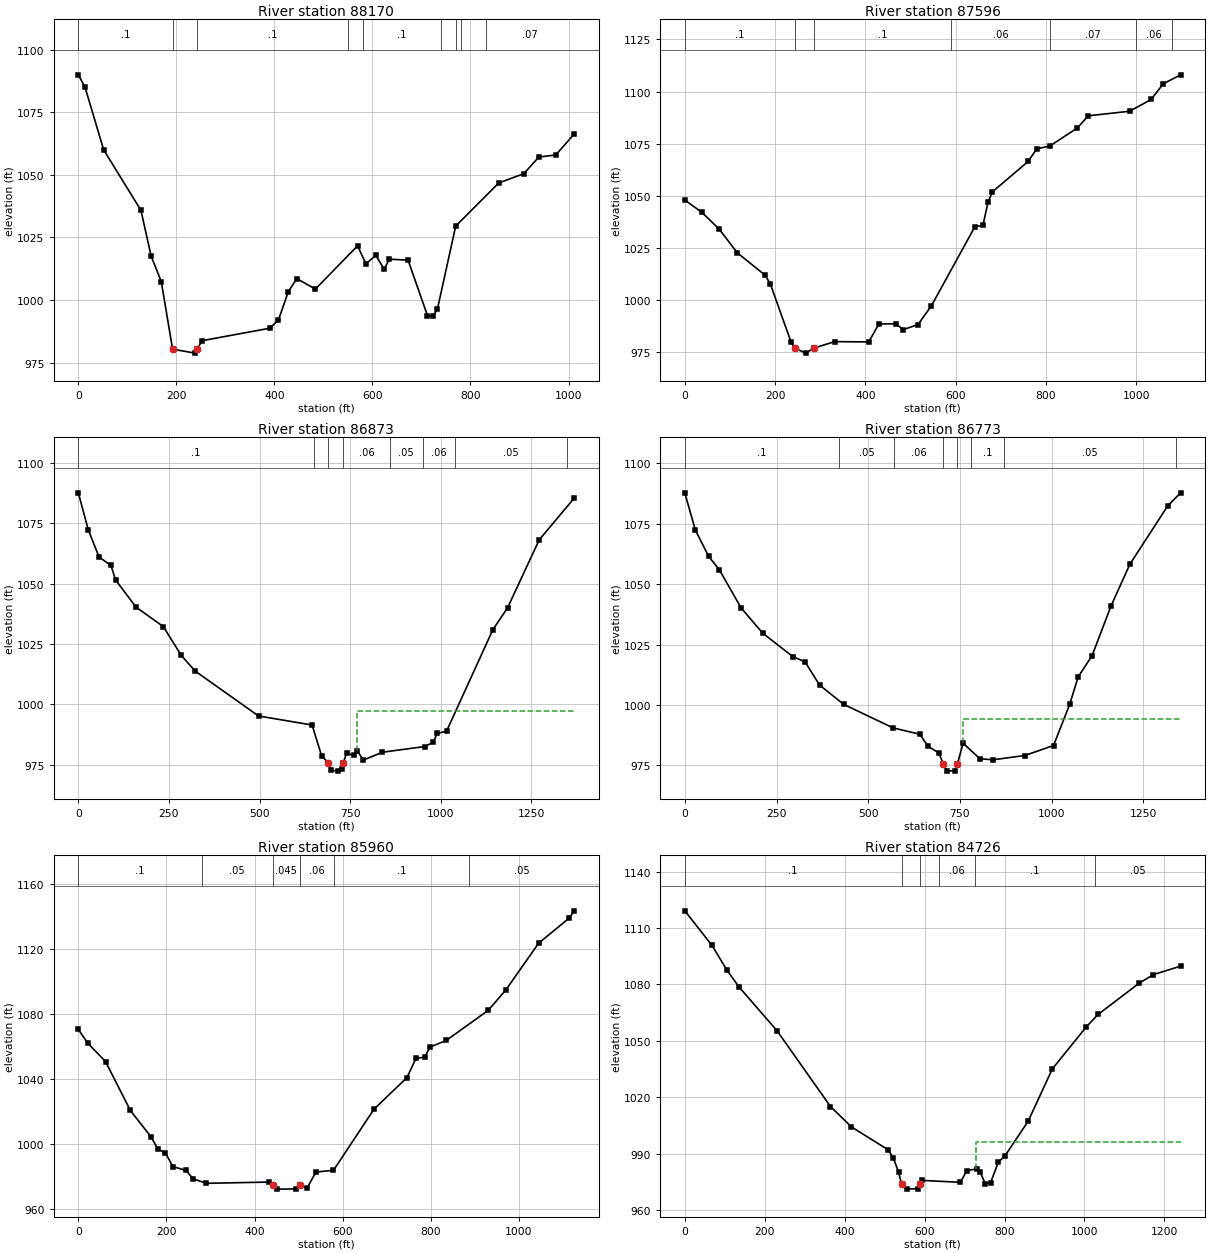
Type RM Length L Ch R = 1 ,88170   ,550.5,573.9,569.3
XS GIS Cut Line= 3
1655970.43152673488017.9920791381656398.26643786488159.601884288
1656540.89316868488702.052143294
#Sta/Elev= 30
       0 1090.03    13.7 1085.06    51.7 1060.04   127.7 1035.87   148.5 1017.57
   169.2 1007.37   192.3980.3492   238.3  978.77   242.8980.3734   252.1  983.73
   390.4  988.72   408.2  992.02   428.4 1003.36   445.7 1008.55   483.6 1004.38
   569.7 1021.68   586.6 1014.48     607 1017.86     624 1012.23   634.2 1016.33
   672.7 1015.94   712.2  993.79   723.7  993.47   732.6  996.42   769.9 1029.59
   857.7  1046.8     909 1050.53   939.5 1057.18   973.9 1057.97  1011.5 1066.37
#Mann= 9 ,-1,0
       0      .1       0   192.3    .045       0   242.8      .1       0
  550.66     .05       0  580.66      .1       0  740.66     .05       0
  770.66      .1       0  780.66     .05       0  830.66     .07       0
Bank Sta=192.3,242.8
XS Rating Curve= 0 ,0
Exp/Cntr(USF)=0,0
Exp/Cntr=0.3,0.1

Type RM Length L Ch R = 1 ,87596   ,700.8,723.7,742
XS GIS Cut Line= 3
1655795.09483159488427.934211448  1656501.380674488823.059158253
1656577.93613244489102.116151934
#Sta/Elev= 30
       0 1047.97    37.9 1042.04    76.4 1033.96   116.3 1022.66   178.2 1011.86
   189.5 1007.73   235.5  979.85   243.2976.9574   268.4  974.54   285.7976.9508
   332.3  980.06   407.5  979.91   430.1  988.49   467.7  988.62   483.8  985.81
   516.5  988.19   546.4  997.21   642.9  1035.2   660.6 1035.76   671.9 1046.95
   681.5 1051.87   760.9 1066.48   779.7 1072.46   809.3 1073.92   870.1 1082.56
   893.9 1088.35   985.8 1090.55  1033.4 1096.19  1060.2 1103.71  1098.7 1108.01
#Mann= 7 ,-1,0
       0      .1       0   243.2    .045       0   285.7      .1       0
     590     .06       0   809.3     .07       0   999.3     .06       0
  1079.3     .05       0
Bank Sta=243.2,285.7
XS Rating Curve= 0 ,0
Exp/Cntr(USF)=0,0
Exp/Cntr=0.3,0.1

Type RM Length L Ch R = 1 ,86873   ,99.5,99.1,98.7
XS GIS Cut Line= 3
 1655600.0018891488329.152974747 1655641.9839147 489346.59971277
1655562.95892534489687.394979389
#Sta/Elev= 30
       0 1087.56    27.6 1072.17    57.2    1061      90 1057.51   103.2 1051.43
   159.4 1040.23   234.5 1032.22   283.8 1020.35   322.5  1013.8   497.2  995.23
     645  991.49   671.2  978.81   689.4975.8809   697.5  972.76   717.2  972.41
     727  973.18   731.3975.8888   740.2  979.84   759.9  978.91   769.7  980.93
   786.2  976.97   838.7  980.22   956.9   982.6   979.9  984.45   989.7  987.98
    1016  988.92  1143.9 1030.95  1184.3 1039.95  1271.9 1068.14  1368.2 1085.34
#Mann= 8 ,-1,0
       0      .1       0     650     .06       0   689.4    .045       0
   731.3     .06       0     860     .05       0     950     .06       0
 1038.31     .05       0 1348.31      .1       0
#XS Ineff= 2 , 0
                          769.25          997.49
Permanent Ineff=
       F       F
Bank Sta=689.4,731.3
XS Rating Curve= 0 ,0
Exp/Cntr(USF)=0,0
Exp/Cntr=0.3,0.1

Type RM Length L Ch R = 1 ,86773   ,810.8,813.1,812.2
XS GIS Cut Line= 3
1655484.47682717488318.2620819331655550.58523301489355.796784728
1655456.93165807489653.284611016
#Sta/Elev= 30
       0 1087.83    28.7 1072.47    64.9 1061.58    94.5  1055.9   153.6 1040.17
   212.8 1029.69     295    1020   327.9 1017.85   367.2  1008.3   433.1 1000.27
   567.9  990.52   640.2  987.93   663.2  982.91   692.8  980.12   704.5  975.46
   715.8  972.63   735.5  972.86  742.73975.4078   758.5  984.19   804.6  977.74
   840.7  977.33   926.6   979.1  1005.1  983.23    1049 1000.24  1072.3 1011.66
  1110.1 1020.42  1161.7 1040.98  1213.3 1058.32  1316.5 1082.49  1351.5 1087.85
#Mann= 8 ,-1,0
       0      .1       0     420     .05       0     570     .06       0
   704.5    .045       0  742.73     .06       0     780      .1       0
     870     .05       0 1339.64      .1       0
#XS Ineff= 2 , 0
                          759.13          994.22
Permanent Ineff=
       F       F
Bank Sta=704.5,742.73
XS Rating Curve= 0 ,0
Exp/Cntr(USF)=0,0
Exp/Cntr=0.3,0.1

Type RM Length L Ch R = 1 ,85960   ,1229.3,1234.4,1221.4
XS GIS Cut Line= 3
1654873.44693744488249.8069834281654786.99291715488830.793862507
1654769.38008923489368.400894779
#Sta/Elev= 30
       0 1070.42    21.9 1061.82    61.7 1050.68   118.1 1020.56   164.5  1004.5
   181.1  996.67   197.7  994.52   214.3  986.05   244.1  983.68   260.7  978.47
   290.6  975.74   433.2  976.51  440.81974.7123   449.8  972.16   494.6  972.27
   502.9  974.72   519.4  972.94   539.3  982.69   579.1  983.74   671.1 1021.39
   745.8  1040.8   766.3 1052.63     786 1053.35   798.4 1059.64   835.3  1063.7
   930.5 1082.25   969.9 1094.62  1044.6 1123.46  1114.3 1139.03  1125.3 1143.43
#Mann= 6 ,-1,0
       0      .1       0     280     .05       0  440.81    .045       0
   502.9     .06       0     580      .1       0  887.38     .05       0
Bank Sta=440.81,502.9
XS Rating Curve= 0 ,0
Exp/Cntr(USF)=0,0
Exp/Cntr=0.3,0.1

Type RM Length L Ch R = 1 ,84726   ,775.4,786.8,775.3
XS GIS Cut Line= 3
1653866.39118499488178.5115887771653651.54199517488450.159989706
1653671.29824251489344.130181852
#Sta/Elev= 30
       0 1119.19    68.3 1100.74   105.2 1087.68   135.2 1078.82   231.5 1055.16
   364.5 1015.04     417  1004.2   508.9     992     522  987.55   535.1  979.97
   542.4  973.66   554.8   971.1   584.4  971.39   589.2973.7072   594.2  975.75
   689.4  974.72   705.8  980.97     732  981.89   738.6   980.4   751.7  974.06
   764.9  974.46   784.5   985.5     801  988.77     859 1007.23   919.4 1035.02
  1004.4  1057.4  1033.9 1064.04  1137.1 1080.74  1172.4 1085.26  1240.5 1089.76
#Mann= 6 ,-1,0
       0      .1       0   542.4    .045       0   589.2      .1       0
  636.34     .06       0  726.34      .1       0 1026.34     .05       0
#XS Ineff= 2 , 0
                          728.89          996.35
Permanent Ineff=
       F       F
Bank Sta=542.4,589.2
XS Rating Curve= 0 ,0
Exp/Cntr(USF)=0,0
Exp/Cntr=0.3,0.1

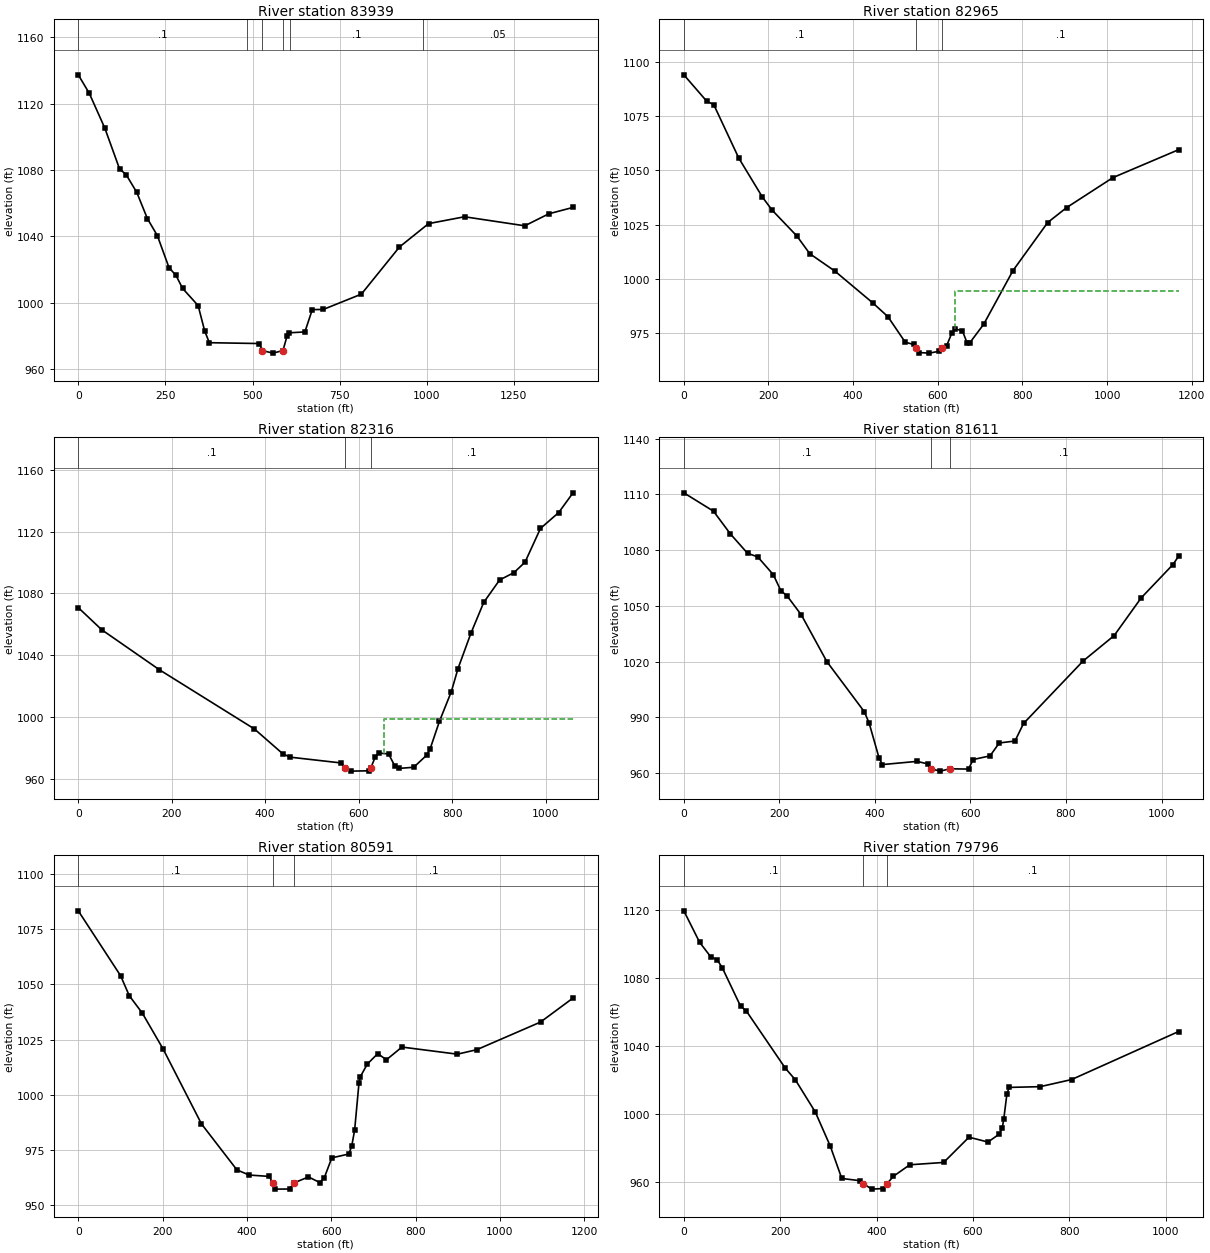
Type RM Length L Ch R = 1 ,83939   ,979.5,974.1,952.9
XS GIS Cut Line= 6
1652710.23046105488324.7367457081652918.71207508 488611.29669717
1652939.64543217488697.3513150961652949.63950667488771.777347341
1652959.03581335488871.340468422 1653251.7526996489617.791901736
#Sta/Elev= 30
       0  1137.3    31.6 1126.15    76.2 1105.15   118.5 1080.56   137.3 1077.15
   167.8 1066.47   198.3 1050.65   226.9 1040.39   260.3 1021.12   280.5 1016.36
   299.3 1008.58   343.9  998.22   362.5   983.1     376  975.83   519.7  975.32
   527.8971.0728   559.2  969.54   587.5971.1092   598.8  979.66   605.4  981.79
   650.3  982.32   671.5  995.76   703.2  995.88   812.4  1005.1   921.8 1033.54
  1005.3 1047.61  1108.4 1051.74  1281.3 1046.29  1350.3 1053.53  1419.8 1057.38
#Mann= 6 ,-1,0
       0      .1       0  482.94     .06       0   527.8    .045       0
   587.5     .06       0  608.03      .1       0  988.04     .05       0
Bank Sta=527.8,587.5
XS Rating Curve= 0 ,0
Exp/Cntr(USF)=0,0
Exp/Cntr=0.3,0.1

Type RM Length L Ch R = 1 ,82965   ,602.1,649.4,672.4
XS GIS Cut Line= 4
1652157.47579006488729.2169833871652184.64063016489139.159115697
1652372.32497989489393.5208002031652439.00231466489830.627772606
#Sta/Elev= 30
       0 1094.14    54.2 1081.93    70.6 1080.41   129.8  1055.7   185.7 1037.67
   208.7 1031.65   267.2  1019.7   297.5 1011.57   356.8 1003.54     447  988.75
   482.2  982.48   523.1  970.71   542.8  969.66   547.5  968.24   555.7  965.92
   580.1  965.65   603.6  966.52   611.2  968.18   620.9  969.01   633.2  974.91
   641.3  976.82   658.1  975.98   669.8  970.19   675.4  970.33   708.6     979
   777.8 1003.77   859.7 1025.93   904.4 1032.83  1013.9 1046.68  1169.1 1059.57
#Mann= 3 ,-1,0
       0      .1       0   547.5    .045       0   611.2      .1       0
#XS Ineff= 2 , 0
                          641.04          994.47
Permanent Ineff=
       F       F
Bank Sta=547.5,611.2
XS Rating Curve= 0 ,0
Exp/Cntr(USF)=0,0
Exp/Cntr=0.3,0.1

Type RM Length L Ch R = 1 ,82316   ,692,704.9,696.5
XS GIS Cut Line= 2
1652002.52521116488805.108869828 1651456.0535417489711.697814558
#Sta/Elev= 30
       0 1070.78    50.1 1056.46   173.7 1030.49   376.7  992.18     438  975.96
   453.3  973.88   563.1   970.1   571.1  966.71   583.6  964.83   621.3  965.04
   625.7  966.81   635.6  974.11   642.8  976.55     664  975.95   677.5  968.02
     687  966.61   717.7  967.33   745.6   975.2   752.8  979.23   772.8  997.14
   798.2 1016.34   812.5 1031.31   840.2 1054.24   867.5 1074.15   901.5 1088.68
   932.2 1093.46   955.9 1100.24   988.9 1122.08    1028 1132.41  1058.6 1145.16
#Mann= 3 ,-1,0
       0      .1       0   571.1    .045       0   625.7      .1       0
#XS Ineff= 2 , 0
                           655.1          998.48
Permanent Ineff=
       F       F
Bank Sta=571.1,625.7
XS Rating Curve= 0 ,0
Exp/Cntr(USF)=0,0
Exp/Cntr=0.3,0.1

Type RM Length L Ch R = 1 ,81611   ,1020.9,1020,1005.8
XS GIS Cut Line= 2
1651473.18498683488422.6180954161650910.13193763489291.892978387
#Sta/Elev= 30
       0  1110.8    62.1 1100.91    97.4 1088.71   133.3 1078.29   154.7 1076.34
   187.3 1066.78     203 1058.19   216.3  1055.3     246  1045.1   299.4    1020
   377.7  993.08   387.8  987.02   408.5  968.32   415.6  964.61   488.3  966.34
   510.5  964.96   516.5962.3832   536.6  961.09   556.8  962.34   595.9  962.19
   605.6  967.32     641   969.3   660.3  976.24   693.2  977.28   711.1  986.72
   835.5 1020.26   900.8    1034   957.4 1054.29  1023.9 1072.22  1035.7 1076.71
#Mann= 3 ,-1,0
       0      .1       0   516.5    .045       0   556.8      .1       0
Bank Sta=516.5,556.8
XS Rating Curve= 0 ,0
Exp/Cntr(USF)=0,0
Exp/Cntr=0.3,0.1

Type RM Length L Ch R = 1 ,80591   ,809.1,795.2,778.8
XS GIS Cut Line= 3
1650537.46350816487988.3577081271650322.61431834488702.052143294
1650297.91900916489129.280992027
#Sta/Elev= 30
       0 1083.29   100.4 1053.91   120.9 1044.89   151.8 1037.02   201.1 1020.79
   292.2  986.85   376.2  966.06   405.3  963.72   453.3   963.1   460.6960.1555
     467  957.35   501.2   957.4   510.6960.0912   545.8  962.87   573.2  960.29
   583.5  962.56   601.3  971.51   641.7  973.24   648.6  976.95   655.4  984.09
   665.7 1005.44   669.1  1008.3   685.6 1013.99   710.2 1018.66   730.8 1015.89
   767.5 1021.64     899 1018.42   945.2 1020.46  1096.2 1032.95  1173.3 1043.83
#Mann= 3 ,-1,0
       0      .1       0   460.6    .045       0   510.6      .1       0
Bank Sta=460.6,510.6
XS Rating Curve= 0 ,0
Exp/Cntr(USF)=0,0
Exp/Cntr=0.3,0.1

Type RM Length L Ch R = 1 ,79796   ,484.3,465.9,440.9
XS GIS Cut Line= 3
1649653.37143969488346.4396911691649804.01282566488818.120096418
  1649823.769073489349.069243687
#Sta/Elev= 30
       0 1119.72    32.8 1101.17    55.6 1092.74    69.4 1090.81    79.7 1086.26
   117.6 1063.67   129.4  1060.9   210.6 1027.11   231.3 1020.32   272.6 1001.42
   303.6  981.45   327.7  962.27   365.6  960.94   372.5  959.22   389.7  955.99
   413.8  956.34   421.6 959.213   434.8  963.54   468.7  970.31   539.1  971.69
   591.6  986.55     631  983.69     654  988.27   660.5  991.78   663.8  997.26
   670.4  1012.2   675.2 1015.84   739.3 1016.27   804.4 1020.44  1026.5 1048.71
#Mann= 3 ,-1,0
       0      .1       0   372.5    .045       0   421.6      .1       0
Bank Sta=372.5,421.6
XS Rating Curve= 0 ,0
Exp/Cntr(USF)=0,0
Exp/Cntr=0.3,0.1