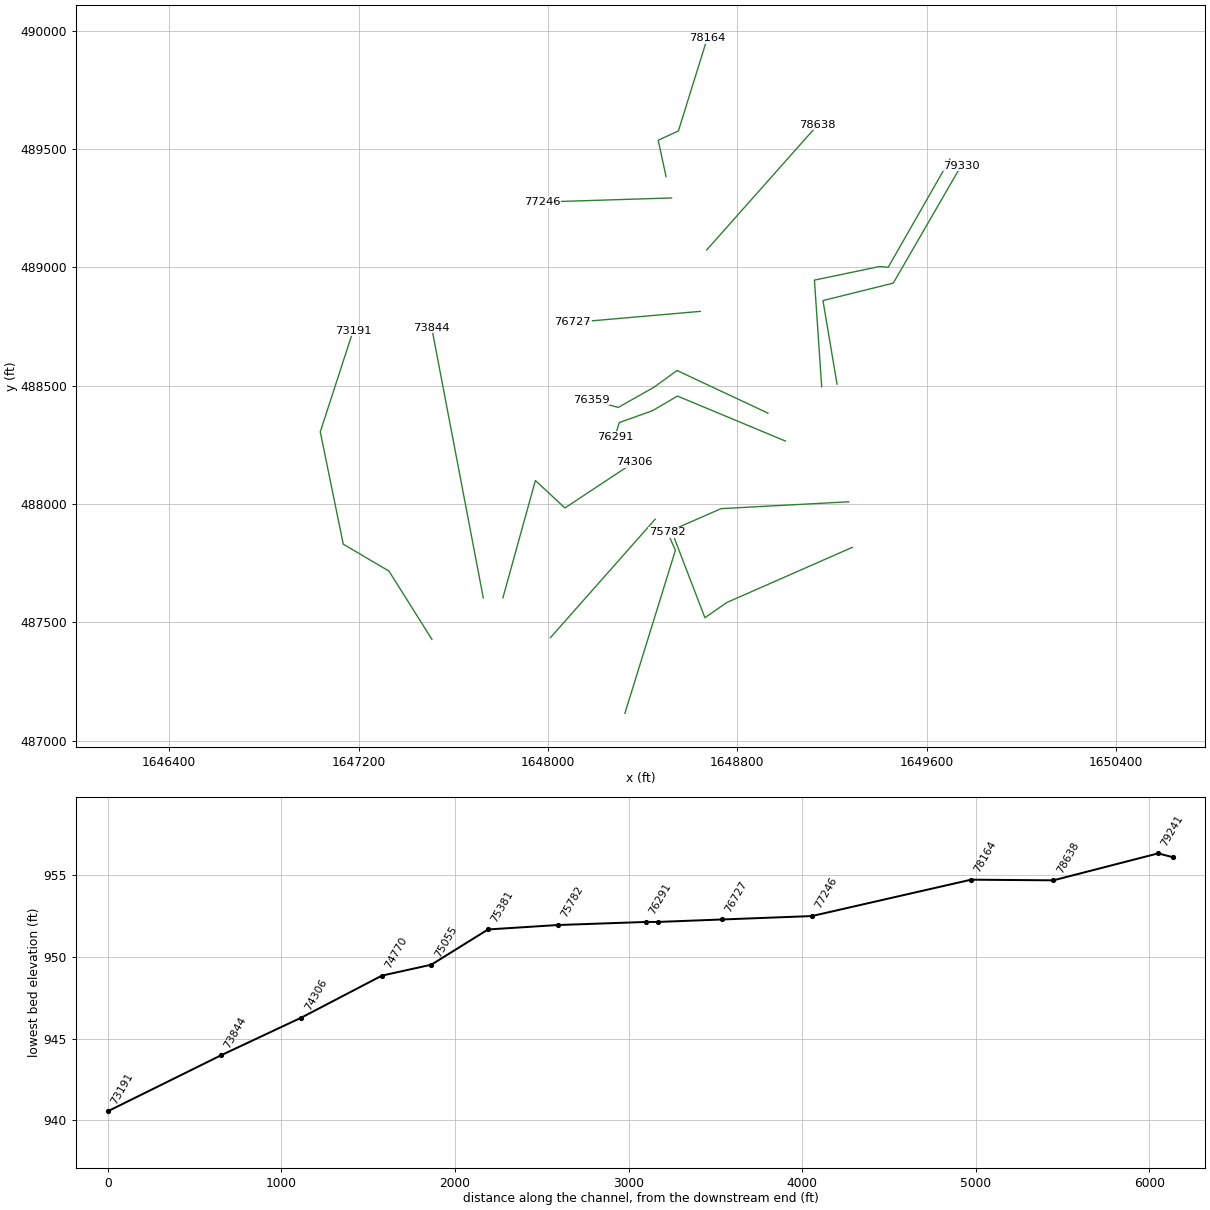
HEC-RAS study GraveCk1.prj: GraveCk1

--- GraveCk1.g01 (geometry) --- (continued)

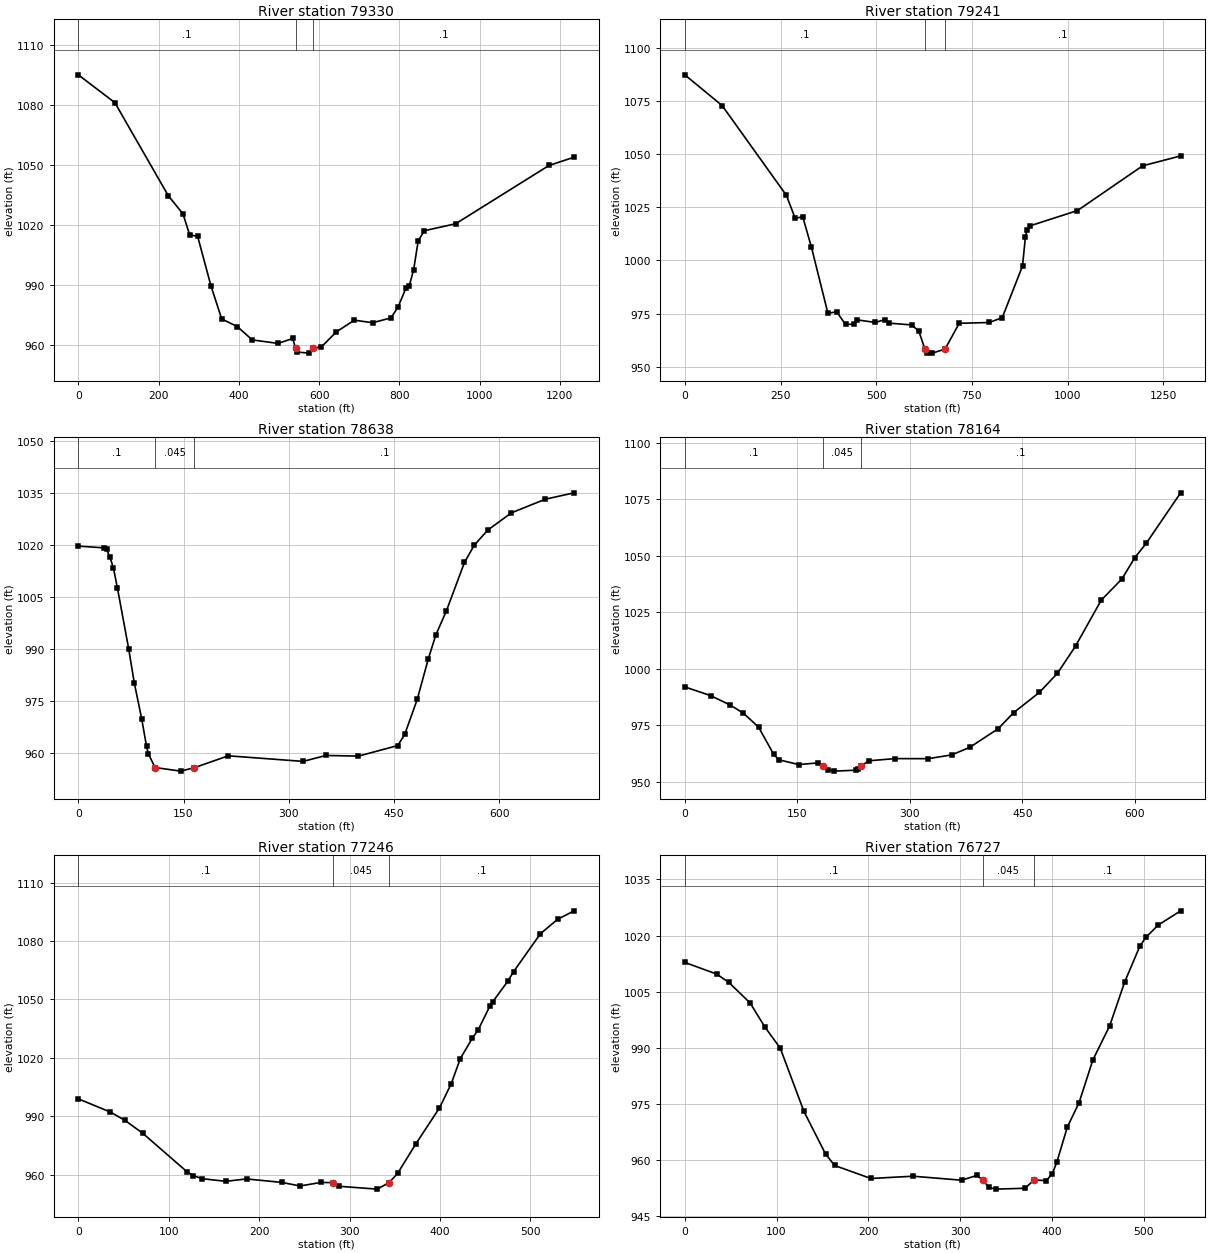
Type RM Length L Ch R = 1 ,79330   ,88.8,88.7,85.4
XS GIS Cut Line= 4
1649220.76174356488506.4109724331649161.35223828488859.267428053
1649458.39976469488933.0792376481649744.64556288 489428.15844834
#Sta/Elev= 30
       0 1095.32    91.1 1081.39   224.2 1034.85   260.8 1025.76   277.4 1015.34
   297.4 1014.49   330.6  989.73   357.3  973.21   396.3  969.38   433.5  962.73
   497.7  960.97   534.4  963.44   541.3958.5814   545.1  956.65   575.5  956.11
   585.6   958.6   605.9  959.23   643.1  966.75   687.9  972.59   733.4  971.32
   778.9  973.71   796.4  978.95   816.8  988.75   824.4  989.45   835.7  997.83
   847.1 1012.26   862.3 1017.33   940.5 1020.83    1173 1049.97  1235.8 1054.13
#Mann= 3 ,-1,0
       0      .1       0   541.3    .045       0   585.6      .1       0
Bank Sta=541.3,585.6
XS Rating Curve= 0 ,0
Exp/Cntr(USF)=0,0
Exp/Cntr=0.3,0.1

Type RM Length L Ch R = 1 ,79241   ,594.2,602.9,620
XS GIS Cut Line= 5
1649155.95137416  488495.6092442 1649125.3464775 488945.68125392
1649400.79054745489003.2904711641649436.79630823488999.689895086
1649697.83807387489456.963056962
#Sta/Elev= 30
       0 1087.46    97.6 1072.97   265.3 1030.71   288.3 1019.91   308.1 1020.54
   330.7 1006.34   373.8  975.14   396.8   975.8   419.9  969.85   442.9  970.03
   451.1  971.99   497.9  970.81   522.7  972.14   532.8  970.49   593.1  969.63
   611.5  966.62   627.2  958.27   633.3  956.52   646.7  956.35   679.9 958.265
   716.8   970.4   795.3  970.78   829.3  973.07   882.2   997.4   889.7 1010.97
   893.5 1014.24   901.1 1016.28  1025.7 1023.51  1195.7 1044.57  1295.2 1049.26
#Mann= 3 ,-1,0
       0      .1       0   627.2    .045       0   679.9      .1       0
Bank Sta=627.2,679.9
XS Rating Curve= 0 ,0
Exp/Cntr(USF)=0,0
Exp/Cntr=0.3,0.1

Type RM Length L Ch R = 1 ,78638   ,481.7,473.9,460.2
XS GIS Cut Line= 2
1648670.07036601489072.9604872231649139.28124034489601.440103575
#Sta/Elev= 30
       0 1019.66    36.8 1019.16    40.2 1018.72    45.1 1016.46    50.1 1013.27
    55.7 1007.59    71.7  990.08    79.7  980.22    90.3  969.82    97.2  961.88
    99.6  959.78   109.4  955.73     146   954.7   165.4   955.7   213.7  959.12
   320.3  957.51   352.9  959.22   399.3  959.04   455.3  962.08   465.2  965.31
     483  975.39   498.8  987.11   509.6  994.05   524.5 1000.92   550.4 1014.97
   564.3 1019.93   583.8 1024.33   617.3 1029.27   665.6 1033.21   706.7 1035.05
#Mann= 3 ,-1,0
       0      .1       0   109.4    .045       0   165.4      .1       0
Bank Sta=109.4,165.4
XS Rating Curve= 0 ,0
Exp/Cntr(USF)=0,0
Exp/Cntr=0.3,0.1

Type RM Length L Ch R = 1 ,78164   ,808.4,917.8,969
XS GIS Cut Line= 4
1648498.65580703489382.6838713551648465.43469426489536.465577047
1648550.74134298489575.8378764571648672.53989693 489966.93067937
#Sta/Elev= 30
       0     992    34.6  988.12    60.5  983.98    78.2  980.35    98.3  974.21
   118.5  962.17   125.2  959.77     152  957.64   177.2  958.37   184.2956.9822
   191.4  955.26   198.9  954.74   227.8  955.14   231.3  955.63   234.6  956.98
   245.9  959.33   280.2  960.28   324.5  960.25   355.7  961.92   379.9  965.27
   417.7   973.5   438.3   980.6   472.7  989.58   496.7  998.03   520.8 1010.05
   555.1 1030.37   582.6 1039.74   599.8 1049.16   615.2  1055.6   660.9 1077.86
#Mann= 3 ,-1,0
       0      .1       0   184.2    .045       0   234.6      .1       0
Bank Sta=184.2,234.6
XS Rating Curve= 0 ,0
Exp/Cntr(USF)=0,0
Exp/Cntr=0.3,0.1

Type RM Length L Ch R = 1 ,77246   ,509.7,519.6,515.6
XS GIS Cut Line= 2
1648521.89851096489292.7487388841647973.66264727489275.462022461
#Sta/Elev= 30
       0  998.88    35.1  992.19    51.5  987.86    71.2  981.22   120.5  961.32
     127   959.5   136.9  957.88   163.1  956.51   186.1  957.75   225.5  955.94
   245.2  954.12   268.2  955.94   281.3  955.86   287.9  953.99   330.5  952.51
   343.7  955.81   353.2  960.59   373.2  975.65   399.5  994.22   412.6 1006.76
   422.5 1019.53   435.9 1030.06   442.2 1034.22   455.3 1046.58   458.2 1048.62
     475 1059.26   481.5 1064.25   511.1 1083.69   530.1 1091.11   548.5  1095.5
#Mann= 3 ,-1,0
       0      .1       0   281.3    .045       0   343.7      .1       0
Bank Sta=281.3,343.7
XS Rating Curve= 0 ,0
Exp/Cntr(USF)=0,0
Exp/Cntr=0.3,0.1

Type RM Length L Ch R = 1 ,76727   ,345.6,368.1,371.4
XS GIS Cut Line= 2
1648642.90552592488813.6597408831648104.54778589 488766.73865345
#Sta/Elev= 30
       0 1012.82    34.9 1009.69      48 1007.47    71.1 1002.02    87.4  995.53
     104  989.95   129.8  973.06   153.4  961.68   163.3  958.61   202.8  955.14
   248.9  955.75   301.6  954.68   318.1  955.94   324.7  954.78   331.3  952.75
   338.8   952.3   370.8  952.53   380.7  954.74   393.8  954.57   400.4  956.32
   405.5  959.52   416.9  968.84   429.7  975.38   444.8  986.82     463  995.84
   479.4 1007.58   495.9 1017.12   502.6 1019.53   515.7 1022.74   540.4 1026.59
#Mann= 3 ,-1,0
       0      .1       0   324.7    .045       0   380.7      .1       0
Bank Sta=324.7,380.7
XS Rating Curve= 0 ,0
Exp/Cntr(USF)=0,0
Exp/Cntr=0.3,0.1

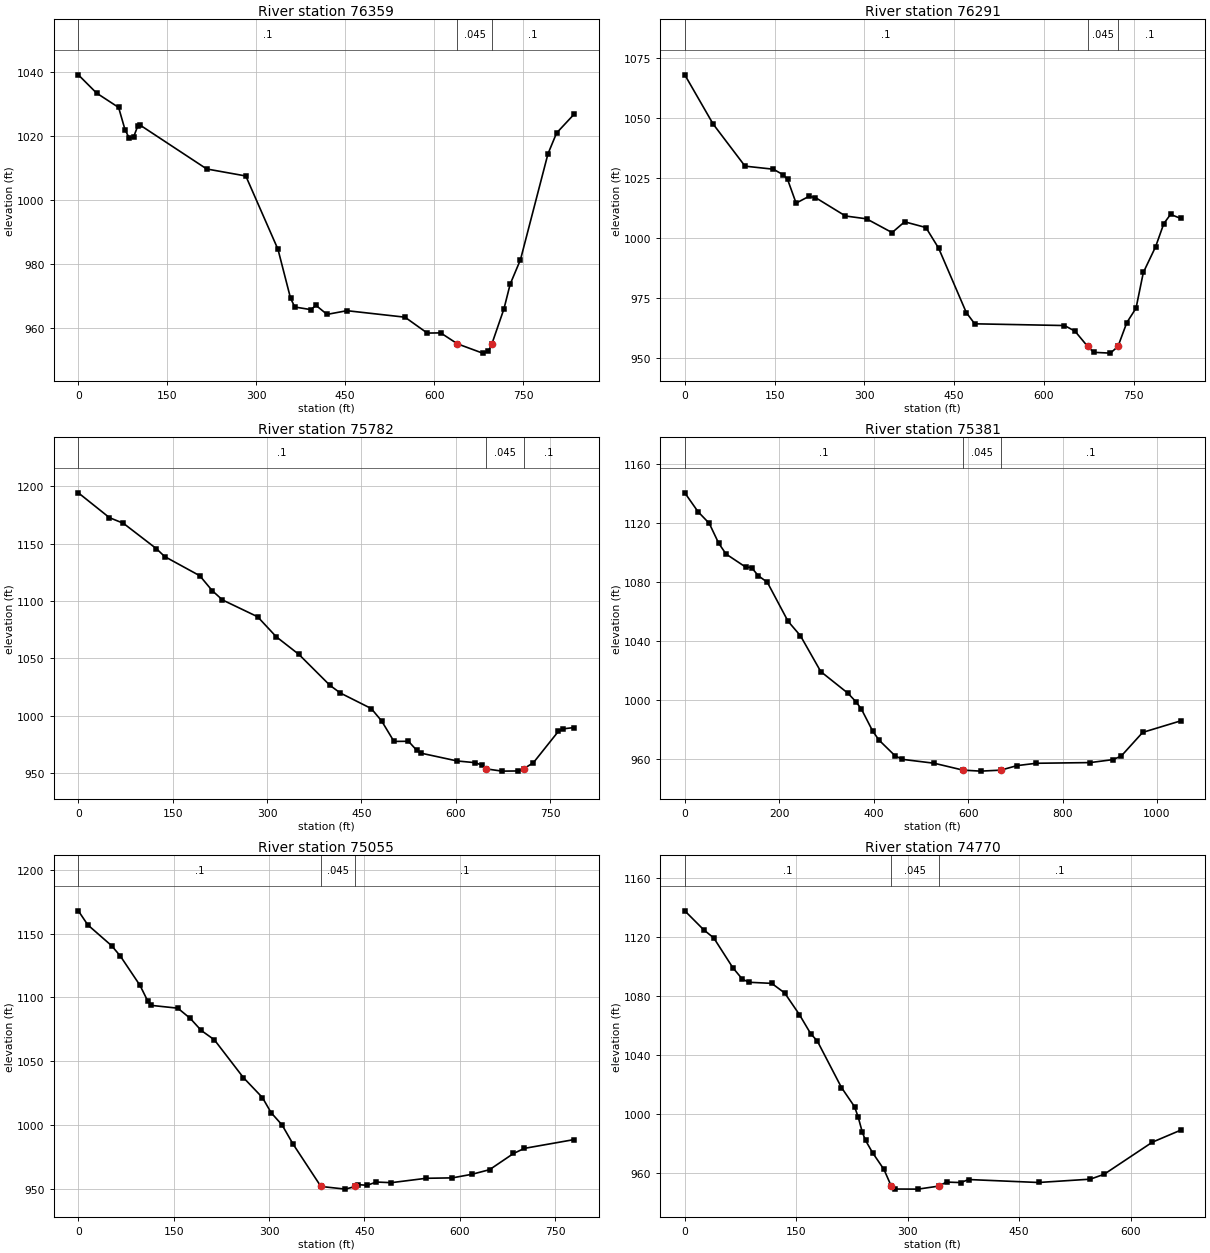
Type RM Length L Ch R = 1 ,76359   ,75.2,67.3,65.4
XS GIS Cut Line= 5
 1648928.8630464488383.9350360351648544.80159811488563.963839923
1648448.78623604488493.9526384111648296.76191275488407.938876553
1648182.74367029488439.943997245
#Sta/Elev= 30
       0 1039.03    30.8 1033.33    67.9 1028.85    78.8 1021.85      86 1019.23
    93.3  1019.7   100.5 1023.17   104.2 1023.33   216.5 1009.64   282.4 1007.45
   336.7  984.53   357.8  969.32     365  966.55   392.1  965.73   400.8  967.05
   419.4  964.24   452.9   965.4   550.8  963.37   588.4  958.41     611  958.47
   639.3 955.045   681.7  952.15   691.6  952.78   697.4955.0567   717.7  965.97
   728.2  973.68   745.6  981.34   791.9 1014.34   806.5 1020.88   836.1 1026.75
#Mann= 3 ,-1,0
       0      .1       0   639.3    .045       0   697.4      .1       0
Bank Sta=639.3,697.4
XS Rating Curve= 0 ,0
Exp/Cntr(USF)=0,0
Exp/Cntr=0.3,0.1

Type RM Length L Ch R = 1 ,76291   ,503.3,509.8,506.8
XS GIS Cut Line= 5
  1649002.874888488265.9161534861648546.80191815 488455.94655759
1648440.78495586488393.9366362511648300.76255284488343.928635171
1648282.75967245488283.919033875
#Sta/Elev= 30
       0 1068.05    47.3 1047.56   100.6 1030.02     148 1028.74   164.6 1026.38
   171.7 1024.48   185.9 1014.62   207.2 1017.41   218.3 1016.92   268.4 1009.26
   303.6 1008.08   346.2 1002.35   367.2 1006.84   402.7 1004.46     424  995.85
   470.2  969.05   484.2  964.36   634.2  963.64   651.7  961.31   672.9954.9424
     683  952.48   710.9  952.15   723.6954.9458   738.3  964.86   753.7  970.86
   765.9  985.73   786.4  996.45   800.1  1006.1   811.4 1009.93   828.2 1008.26
#Mann= 3 ,-1,0
       0      .1       0   672.9    .045       0   723.6      .1       0
Bank Sta=672.9,723.6
XS Rating Curve= 0 ,0
Exp/Cntr(USF)=0,0
Exp/Cntr=0.3,0.1

Type RM Length L Ch R = 1 ,75782   ,382.4,400.2,402.9
XS GIS Cut Line= 3
1649270.11424466488009.3752519171648731.21107368487980.509789175
1648503.32398013487880.774886707
#Sta/Elev= 30
       0 1194.18    49.5 1172.55    71.5 1167.71   124.1 1145.58   137.2 1138.75
   193.1 1122.02   212.8  1109.1   229.2 1100.95   285.1  1086.3   314.6 1068.96
   350.8 1053.51     400 1026.67   416.5 1019.98   465.8 1006.41   482.2  995.67
   501.9  977.81   524.9  977.94     538  970.15   545.1  967.57   602.4   960.8
   631.4   959.3   641.7  957.12   648.1953.9382   673.7  951.96     699   952.1
     708953.9736   723.6   959.3   763.4  986.63   770.9  988.75   788.4  989.91
#Mann= 3 ,-1,0
       0      .1       0   648.1    .045       0     708      .1       0
Bank Sta=648.1,708
XS Rating Curve= 0 ,0
Exp/Cntr(USF)=0,0
Exp/Cntr=0.3,0.1

Type RM Length L Ch R = 1 ,75381   ,412.2,326.7,261.9
XS GIS Cut Line= 4
1649285.20330528487816.8518597581648755.07999883487583.918891774
1648662.71002877487519.6615212961648534.19528781 487854.33532587
#Sta/Elev= 30
       0 1140.43      28 1127.63    51.8 1119.72    71.7 1106.28    87.3 1098.94
   128.9 1090.07   141.4 1089.76   155.4 1084.28   174.8 1079.76   218.6 1053.35
     245 1043.46     288 1019.19   345.3 1004.57   362.4  998.78     374  993.78
   397.8  978.91   411.3  972.73   445.1  962.16   460.2   959.7   528.1  957.04
  589.51952.3527   626.7  951.69   669.1  952.35   703.7  955.43   744.3  957.02
   858.6  957.48   906.5  959.49   924.1  961.83   969.7  977.95  1050.1  985.76
#Mann= 3 ,-1,0
       0      .1       0  589.51    .045       0   669.1      .1       0
Bank Sta=589.51,669.1
XS Rating Curve= 0 ,0
Exp/Cntr(USF)=0,0
Exp/Cntr=0.3,0.1

Type RM Length L Ch R = 1 ,75055   ,297.6,284.9,274.1
XS GIS Cut Line= 3
1648324.68634532487115.7038425241648538.10259746487804.733456551
1648514.47071098487858.191483787
#Sta/Elev= 30
       0 1167.79    14.9 1156.74    52.5 1140.37    66.2 1132.22    97.1 1109.24
   109.3 1096.88   114.3 1093.66   156.5 1091.43   176.1 1083.39   193.3 1073.96
   213.9 1066.65   259.6 1036.99   289.5 1021.36   303.2 1009.48   320.4  999.86
   337.7  984.86   381.5951.6273     420  949.53   435.7951.6349   440.6  953.02
   454.3  952.54   468.6   955.1   492.1  954.59   547.1  958.03   588.3  958.36
   619.2  961.19   646.7  964.77   684.4  977.48   701.6   981.5   779.8  988.39
#Mann= 3 ,-1,0
       0      .1       0   381.5    .045       0   435.7      .1       0
Bank Sta=381.5,435.7
XS Rating Curve= 0 ,0
Exp/Cntr(USF)=0,0
Exp/Cntr=0.3,0.1

Type RM Length L Ch R = 1 ,74770   ,522.2,463.3,411.9
XS GIS Cut Line= 2
1648010.65957433487435.828220722 1648452.7360966487935.832011432
#Sta/Elev= 30
       0 1138.02    25.4 1125.16    39.1 1119.52    64.7 1099.32    77.5 1091.57
    86.3 1089.47     117 1088.71   134.4  1082.2   154.2 1067.54   169.5 1054.47
   178.3 1049.59   210.9  1017.9   228.5 1004.88   233.4  997.81     239  987.43
   243.3  981.98   252.7  973.65   268.1  962.22   277.9950.8789   283.4  948.92
     314  948.86   341.7950.9048   352.3  953.66   371.5  953.31     382  955.38
   476.1  953.37   545.8  955.63   564.4  958.95   629.3  980.76   667.4  988.92
#Mann= 3 ,-1,0
       0      .1       0   277.9    .045       0   341.7      .1       0
Bank Sta=277.9,341.7
XS Rating Curve= 0 ,0
Exp/Cntr(USF)=0,0
Exp/Cntr=0.3,0.1

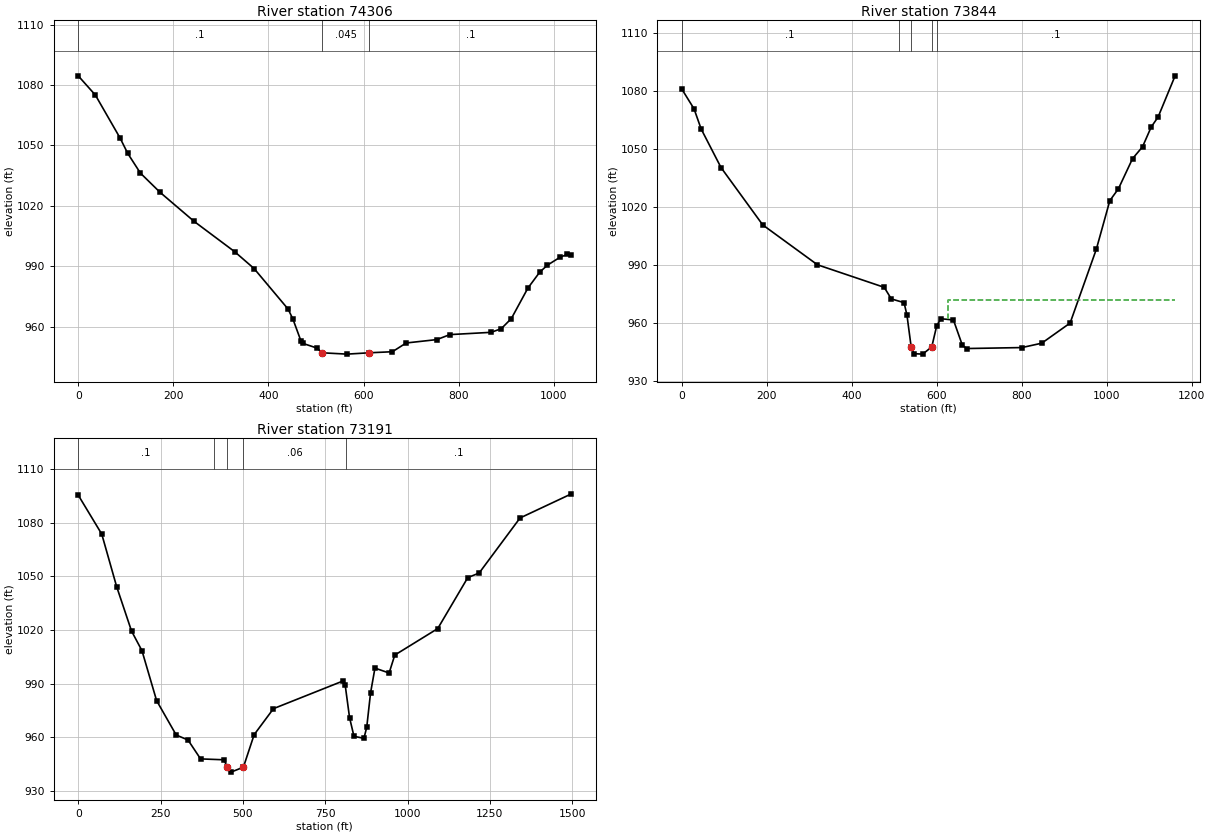
Type RM Length L Ch R = 1 ,74306   ,359.2,462.8,507.2
XS GIS Cut Line= 4
1647809.43853661487603.5124188261647946.65683089488099.316550818
 1648071.4228027487983.3764695311648365.33418105488177.676116062
#Sta/Elev= 30
       0 1084.56    36.1    1075    88.1 1053.63   104.2    1046   130.8 1036.22
   172.2 1026.66   243.7 1012.24   328.8  997.21   369.7  988.83   441.2   968.7
   451.4  963.73   468.4  952.79   471.8  951.67   502.4  949.27   512.6  946.96
   565.2  946.29  612.38946.9587   660.6  947.48   689.6  951.83     754  953.51
   781.5  955.99   868.1  957.12   889.4  958.91   910.7  963.96   945.4  979.06
   970.3  986.99   986.4  990.47  1013.6   994.5  1028.7  995.84  1037.1  995.54
#Mann= 3 ,-1,0
       0      .1       0   512.6    .045       0  612.38      .1       0
Bank Sta=512.6,612.38
XS Rating Curve= 0 ,0
Exp/Cntr(USF)=0,0
Exp/Cntr=0.3,0.1

Type RM Length L Ch R = 1 ,73844   ,630.2,652.3,670.4
XS GIS Cut Line= 2
1647726.63208061487603.5149890821647508.94148048488743.799084997
#Sta/Elev= 30
       0 1080.96    28.7 1070.78    45.4 1060.38    92.2 1040.42   190.4 1010.77
   319.1  990.17   476.3  978.51     493  972.52     523  970.59   529.8  964.16
   539.7  947.73   546.4  944.21   566.8  943.98  588.18947.7244   599.9  958.68
   609.9  962.27   639.2  961.63     660   948.7     670  946.87   800.3  947.37
     847  949.63   913.8  960.05   975.5   998.2  1007.3 1023.34  1027.4 1029.42
  1060.8 1045.06  1084.2 1051.14  1104.7  1061.4  1120.9 1066.55  1160.9 1087.84
#Mann= 5 ,-1,0
       0      .1       0     510     .06       0   539.7    .045       0
  588.18     .06       0     600      .1       0
#XS Ineff= 2 , 0
                          627.29          971.96
Permanent Ineff=
       F       F
Bank Sta=539.7,588.18
XS Rating Curve= 0 ,0
Exp/Cntr(USF)=0,0
Exp/Cntr=0.3,0.1

Type RM Length L Ch R = 1 ,73191   ,1060.2,1044.6,1010.3
XS GIS Cut Line= 5
1647509.52128416487428.5130524581647328.05224985487716.919196287
1647135.24140088487830.3373427361647038.09122533488304.737247261
 1647176.8422681488731.522373118
#Sta/Elev= 30
       0 1095.36    71.5 1073.56   116.7 1044.21   161.9 1019.38   193.6  1008.4
   238.1  980.47   297.5   961.3   333.4  958.49   371.5  947.94   442.8  947.44
   452.3  943.32   463.9  940.55   501.5  943.31   534.2   961.5   592.8  976.02
   803.7  991.46   810.5  989.23   823.8  971.02   837.2  960.55   867.4  959.45
   875.9  965.54   887.5  984.73   900.9  998.69   943.9  995.94   961.1 1005.96
  1091.5 1020.76  1182.7 1049.24  1217.2  1051.8  1341.4 1082.57  1497.5 1096.06
#Mann= 5 ,-1,0
       0      .1       0  410.75     .06       0   452.3    .045       0
   501.5     .06       0  814.44      .1       0
Bank Sta=452.3,501.5
XS Rating Curve= 0 ,0
Exp/Cntr(USF)=0,0
Exp/Cntr=0.3,0.1