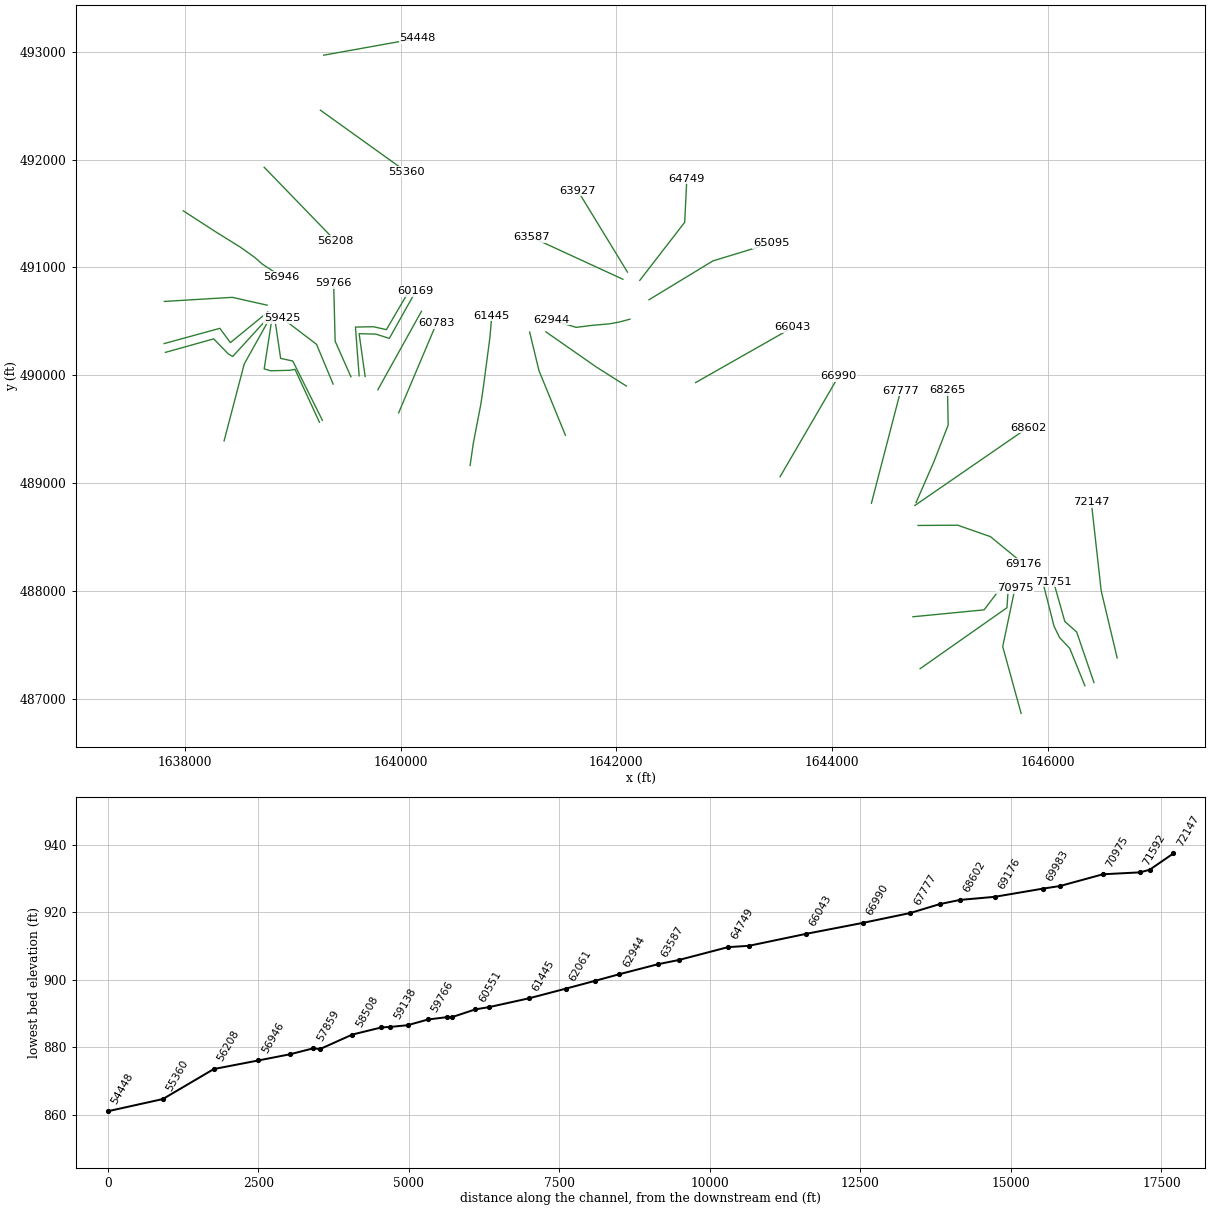
HEC-RAS study GraveCk1.prj: GraveCk1

--- GraveCk1.g01 (geometry) --- (continued)

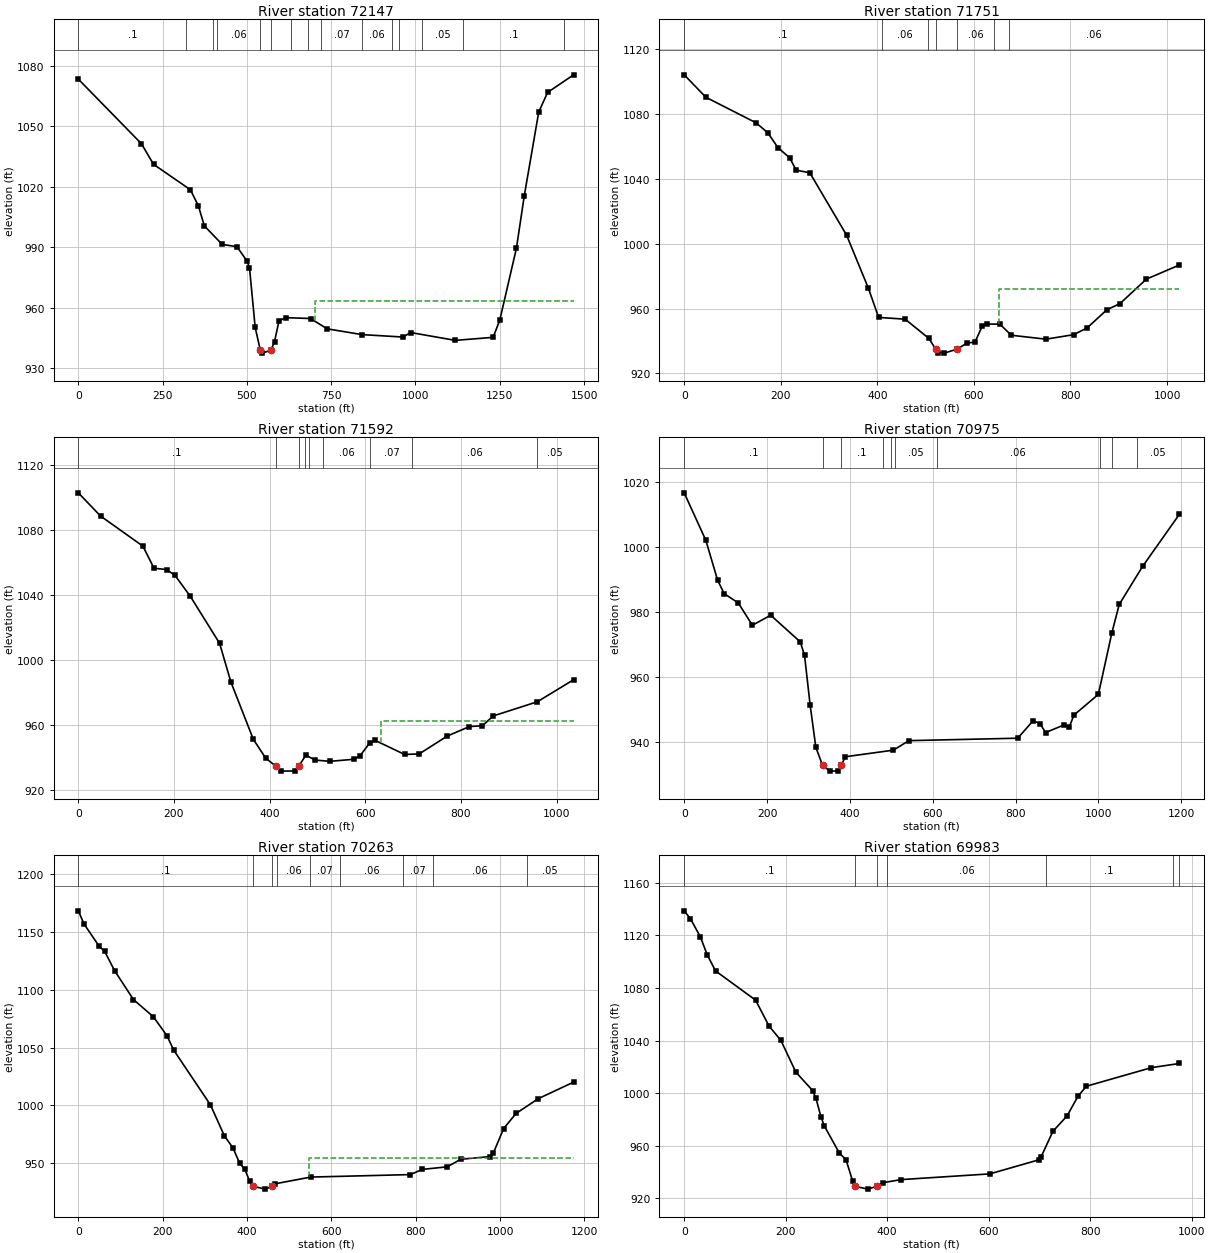
Type RM Length L Ch R = 1 ,72147   ,389.2,396.2,407.9
XS GIS Cut Line= 3
1646644.17301023487377.3132831971646496.00115518488000.183859063
1646404.33208882488823.750907749
#Sta/Elev= 30
       0 1073.32   187.3 1041.25   223.1 1031.04   332.3 1018.45   355.9 1010.55
   373.8  1000.5   426.7  991.32   470.6  990.17   500.9  982.91   507.7  979.74
   524.5  950.17   539.8938.8242   544.8  937.37   571.6  938.78   581.9  943.09
   595.4   953.5   615.6  954.97   688.7  954.54   737.9  949.43   840.6  946.57
   962.7  945.35   985.8  947.58  1117.9   943.7  1230.1   945.2  1249.9  953.69
  1299.4  989.47  1322.5 1015.32  1365.5    1057  1391.9 1066.74  1468.9 1075.45
#Mann= 15 ,-1,0
       0      .1       0     320     .06       0     400      .1       0
     410     .06       0   539.8    .045       0   571.6     .06       0
     630     .07       0  680.25     .06       0  720.25     .07       0
  840.25     .06       0  930.25     .05       0  950.25     .06       0
 1020.25     .05       0 1140.25      .1       0 1440.25     .05       0
#XS Ineff= 2 , 0
                          701.23          963.35
Permanent Ineff=
       F       F
Bank Sta=539.8,571.6
XS Rating Curve= 0 ,0
Exp/Cntr(USF)=0,0
Exp/Cntr=0.3,0.1

Type RM Length L Ch R = 1 ,71751   ,158.8,158.3,154
XS GIS Cut Line= 4
1646428.75582829487149.4771046691646268.73022484487617.551994777
1646158.71262246487715.5676768941646054.07833806488084.768399832
#Sta/Elev= 30
       0 1104.03      45 1090.19   149.1 1074.42   173.3 1068.27   194.1 1059.18
   218.4 1052.91   231.8 1045.33   260.2 1043.63   336.3 1005.26   381.6  972.44
   402.7  954.54   457.6  953.45   506.9  941.57   520.9  934.94   525.8   932.9
   538.3  932.53   565.1934.9567   586.6  938.88   602.1  939.19   617.4  949.31
   626.2  950.45   653.8  950.38   677.6  943.55   749.2  941.13   806.3  943.89
   834.5  948.05   875.4  959.25   902.7  963.07   957.2  978.13  1025.8  986.86
#Mann= 7 ,-1,0
       0      .1       0     410     .06       0  504.67      .1       0
   520.9    .045       0   565.1     .06       0  642.02     .07       0
  672.02     .06       0
#XS Ineff= 2 , 0
                          651.22          972.03
Permanent Ineff=
       F       F
Bank Sta=520.9,565.1
XS Rating Curve= 0 ,0
Exp/Cntr(USF)=0,0
Exp/Cntr=0.3,0.1

Type RM Length L Ch R = 1 ,71592   ,625,617,603.2
XS GIS Cut Line= 5
1646344.74238648487119.4723040211646204.71998346487465.527671494
1646110.70494143487565.543673654 1646058.6966203487671.560635944
1645958.53152104488065.855245847
#Sta/Elev= 30
       0 1102.92    46.5 1088.65     135 1070.14   158.3 1056.52   184.5 1055.75
     202 1052.19   234.1 1039.31   295.4 1010.36     319  986.57   365.9  951.33
     392  939.67   413.5934.6738   424.5  931.77     452  931.88   460.4 934.671
   475.9  941.55   495.1  938.58   525.8  937.79     577  939.08   588.9  941.19
   609.9  949.35   620.7  950.64   682.3  942.01   712.8  942.37   771.1  953.28
   817.7  959.18   844.8  959.67   867.3  965.68   959.7  974.43  1035.5  987.98
#Mann= 9 ,-1,0
       0      .1       0   413.5    .045       0   460.4      .1       0
  473.31     .07       0  483.31      .1       0  510.58     .06       0
  610.58     .07       0  698.66     .06       0  958.66     .05       0
#XS Ineff= 2 , 0
                          632.49          962.74
Permanent Ineff=
       F       F
Bank Sta=413.5,460.4
XS Rating Curve= 0 ,0
Exp/Cntr(USF)=0,0
Exp/Cntr=0.3,0.1

Type RM Length L Ch R = 1 ,70975   ,736.1,712.7,681.2
XS GIS Cut Line= 3
1645753.41320828486862.7892604521645583.01557497487482.641520753
1645696.61399717488023.468791692
#Sta/Elev= 30
       0 1016.67    52.3 1002.07    80.7  989.82    96.5  985.72   130.6  982.85
   164.6     976   208.8  979.09   280.3  970.87   290.5  966.72   304.1  951.39
   317.7  938.57   333.9  932.97   351.7   931.2   372.1  931.23   378.9  932.96
   389.1  935.62     505  937.64   542.3  940.56     805  941.31   842.1  946.65
   858.9  945.78   872.3  943.04     916  945.35   929.3  944.69   940.7  948.41
   999.7  954.77  1032.1  973.57    1050  982.38  1106.9  994.16  1195.5 1010.11
#Mann= 10 ,-1,0
       0      .1       0   333.9    .045       0   378.9      .1       0
     480     .05       0     500      .1       0     510     .05       0
     610     .06       0 1002.85     .05       0 1032.85     .06       0
 1092.85     .05       0
Bank Sta=333.9,378.9
XS Rating Curve= 0 ,0
Exp/Cntr(USF)=0,0
Exp/Cntr=0.3,0.1

Type RM Length L Ch R = 1 ,70263   ,289.9,279.9,267.3
XS GIS Cut Line= 3
1644817.46099053487277.6704545981645622.52806965487843.193034712
1645634.87572424488033.346915362
#Sta/Elev= 30
       0 1168.19    13.7 1156.78    49.8 1137.38    62.3 1133.34    85.9 1116.58
   130.8 1091.49   178.1 1076.63   210.2 1060.26   226.2 1047.86   313.4 1000.47
   346.5  973.66   366.6  963.44   382.6  950.13   394.6  944.95   406.6  934.37
   415.2930.1367   443.5  927.73   459.5930.1205   466.8  932.35     551  938.14
   787.4  940.29   815.6  944.78   874.5  946.99     907  953.53   975.5  955.82
   983.8   958.7  1008.6  980.11  1038.1  993.16  1090.8 1005.92  1174.4 1020.18
#Mann= 9 ,-1,0
       0      .1       0   415.2    .045       0   459.5      .1       0
     470     .06       0     550     .07       0     620     .06       0
     770     .07       0     840     .06       0 1063.84     .05       0
#XS Ineff= 2 , 0
                          546.71          954.89
Permanent Ineff=
       F       F
Bank Sta=415.2,459.5
XS Rating Curve= 0 ,0
Exp/Cntr(USF)=0,0
Exp/Cntr=0.3,0.1

Type RM Length L Ch R = 1 ,69983   ,812.9,806.6,794.3
XS GIS Cut Line= 3
1644750.78365576487759.2289835161645410.14841074487823.436787372
1645600.30229139488072.859410043
#Sta/Elev= 30
       0 1138.67    12.4 1132.65    32.1 1118.72    45.3 1105.25    61.8 1092.96
   140.8  1070.7   167.3 1050.94   190.4 1040.26     220 1016.01     253 1001.98
   259.6  996.24   269.5  981.99   276.1  975.11   305.7  954.44   318.9  949.36
   332.1  932.96     337929.1306   361.8  926.97     380929.1456   391.4  931.85
   427.7  934.22   602.4  938.57   698.4  949.19   703.1  951.28   726.7  970.96
   754.6  982.68   776.2   997.7   792.7 1005.25   920.8 1019.38   976.1 1022.54
#Mann= 7 ,-1,0
       0      .1       0     337    .045       0     380      .1       0
     400     .06       0  712.48      .1       0  962.48     .05       0
  976.12      .1       0
Bank Sta=337,380
XS Rating Curve= 0 ,0
Exp/Cntr(USF)=0,0
Exp/Cntr=0.3,0.1

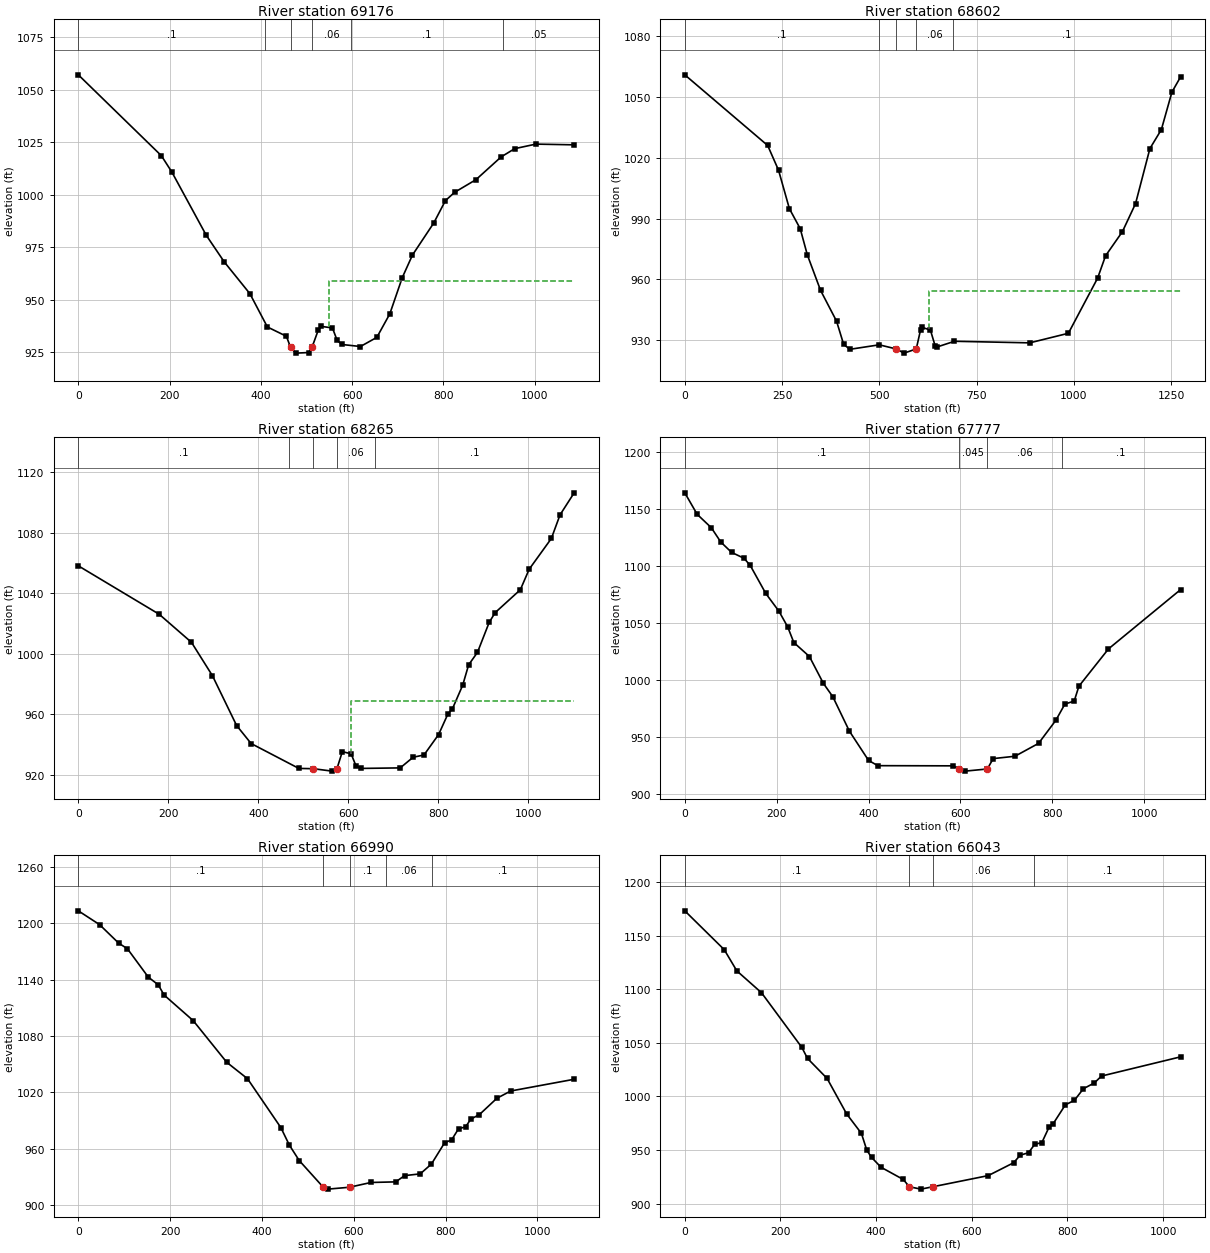
Type RM Length L Ch R = 1 ,69176   ,548.6,574.2,595
XS GIS Cut Line= 4
1644797.70474319488606.278088229 1645165.6648499488608.747619147
1645469.41715276488502.5577896931645775.63898654488250.665636105
#Sta/Elev= 30
       0 1057.12   181.9  1018.6   204.9  1010.8   280.3  980.66   319.7  967.99
   375.9  952.84   414.2  936.99   455.8  932.57     465927.2808   476.7  924.53
   504.5  924.81   511.9927.2553   525.4  935.36   532.3  937.28   556.7  936.53
   567.1  930.58   577.5  928.65     618  927.68     654  932.04   682.4  943.23
   709.7   960.5     732  971.25   778.7  986.54   804.3   997.2   824.4 1001.15
   871.2 1007.18   926.4 1018.03   956.1 1021.95  1002.4 1024.11  1086.3 1023.77
#Mann= 6 ,-1,0
       0      .1       0  407.97     .06       0     465    .045       0
   511.9     .06       0  597.97      .1       0  929.75     .05       0
#XS Ineff= 2 , 0
                          548.11          958.73
Permanent Ineff=
       F       F
Bank Sta=465,511.9
XS Rating Curve= 0 ,0
Exp/Cntr(USF)=0,0
Exp/Cntr=0.3,0.1

Type RM Length L Ch R = 1 ,68602   ,317,337.2,348.4
XS GIS Cut Line= 2
1644768.07037218488791.4929070441645817.62101213489515.065465881
#Sta/Elev= 30
       0 1060.92   213.1 1026.06     241 1013.87   268.9  994.89   296.8  984.99
     315  972.11     349   954.6   390.1  939.43   408.4  927.96   424.3   925.5
     500  927.72  544.05925.6596   563.5  923.62  595.09925.6638   606.1  935.05
   610.9   936.3   631.5  934.98   643.5   927.3   648.6  926.66   693.4  929.47
   886.8  928.69   986.2  933.41  1061.4  960.63  1081.8  971.64  1125.1  983.54
  1158.9  997.38  1195.8 1024.54  1225.3 1033.91  1252.4  1052.4  1274.8 1059.94
#Mann= 5 ,-1,0
       0      .1       0     500     .06       0  544.05    .045       0
  595.09     .06       0     690      .1       0
#XS Ineff= 2 , 0
                          626.79          954.11
Permanent Ineff=
       F       F
Bank Sta=544.05,595.09
XS Rating Curve= 0 ,0
Exp/Cntr(USF)=0,0
Exp/Cntr=0.3,0.1

Type RM Length L Ch R = 1 ,68265   ,480.3,487.3,485.6
XS GIS Cut Line= 4
1644779.51259842488818.5507172081644946.77825872489202.037840828
1645077.32706676489538.6089865591645071.20759139 489860.90135641
#Sta/Elev= 30
       0 1058.09   179.8 1026.04   251.4 1007.51     298  985.44   351.7  952.53
   383.9  940.63     490  924.17  522.08923.9847   563.8  922.38  574.66924.0123
   586.6  935.25   606.1  933.84   616.7     926   627.1  924.16   715.2  924.52
   743.9  931.56     768  933.05   800.5  946.55   821.3  960.25   831.1  963.49
   854.1  979.22   867.2  992.63   886.9  1000.9   913.1 1020.85   926.3 1027.18
   982.1 1042.28  1001.8 1055.86    1051 1076.15  1070.3 1091.77  1101.7 1106.34
#Mann= 5 ,-1,0
       0      .1       0  468.38     .06       0  522.08    .045       0
  574.66     .06       0  658.38      .1       0
#XS Ineff= 2 , 0
                          606.44          968.85
Permanent Ineff=
       F       F
Bank Sta=522.08,574.66
XS Rating Curve= 0 ,0
Exp/Cntr(USF)=0,0
Exp/Cntr=0.3,0.1

Type RM Length L Ch R = 1 ,67777   ,789,786.9,771.8
XS GIS Cut Line= 2
1644365.65575555488812.7505698841644637.07652972489857.149849876
#Sta/Elev= 30
       0 1164.15    26.9 1145.29    57.7 1133.51    78.4 1120.92   101.7 1111.89
   128.9 1106.67   142.4 1100.39   176.3 1075.75   204.9 1060.17   223.8 1046.53
   237.3 1032.69   271.2 1020.41   301.7  996.75   322.1  985.14   358.2  954.88
     400  929.13   420.1  924.56   584.3   924.4     596921.6389   610.2  919.76
   658.4921.6476   671.2  930.76   718.5  932.82   769.9  944.13   807.6  964.43
   827.2  978.64   847.5  981.29   857.7  994.34   922.1  1027.1  1079.1 1079.19
#Mann= 4 ,-1,0
       0      .1       0     596    .045       0   658.4     .06       0
     820      .1       0
Bank Sta=596,658.4
XS Rating Curve= 0 ,0
Exp/Cntr(USF)=0,0
Exp/Cntr=0.3,0.1

Type RM Length L Ch R = 1 ,66990   ,943.9,947.4,913.5
XS GIS Cut Line= 2
1643518.48772791489058.2022461381644061.78452977489991.684932964
#Sta/Elev= 30
       0 1213.28    46.3 1198.56    87.7 1178.95     107 1172.83   152.3 1142.74
   174.1 1134.45   186.8  1123.6   250.2 1096.33   323.4 1051.89   368.5 1034.45
   441.1  982.44   459.6  963.82   481.2  947.28   533.6918.8544   543.6  916.84
   590.8 918.853   637.2  923.92   691.6  924.58   710.6  931.22   744.8   933.1
   769.2  943.56     798   966.3   813.1  969.24   828.3  981.18   843.5  983.11
   854.9  991.35   873.8  996.28   911.8 1013.63   941.9 1021.37  1080.1 1033.86
#Mann= 5 ,-1,0
       0      .1       0   533.6    .045       0   590.8      .1       0
     670     .06       0     770      .1       0
Bank Sta=533.6,590.8
XS Rating Curve= 0 ,0
Exp/Cntr(USF)=0,0
Exp/Cntr=0.3,0.1

Type RM Length L Ch R = 1 ,66043   ,935,947.6,934.9
XS GIS Cut Line= 2
 1642736.0821891 489932.29323924 1643637.2119094490444.355633607
#Sta/Elev= 30
       0 1173.15    82.4 1136.95   108.8 1117.14   160.3 1096.77   244.7 1045.74
   256.5  1035.5   297.5  1016.8   338.3  983.75   369.2  965.57   380.5  949.86
   390.3  943.21   410.2  933.98   456.7  922.58   469.5  915.76   493.7  913.58
     518915.7433   634.3  926.19   687.2  938.13   701.3  945.25   718.5  947.53
   731.4  955.31   746.5  957.06   761.6  971.51   769.7  974.32   795.5  992.17
   814.5  996.42   833.3 1007.25     856 1012.59   871.1 1019.04  1036.5 1036.97
#Mann= 4 ,-1,0
       0      .1       0   469.5    .045       0     518     .06       0
     730      .1       0
Bank Sta=469.5,518
XS Rating Curve= 0 ,0
Exp/Cntr(USF)=0,0
Exp/Cntr=0.3,0.1

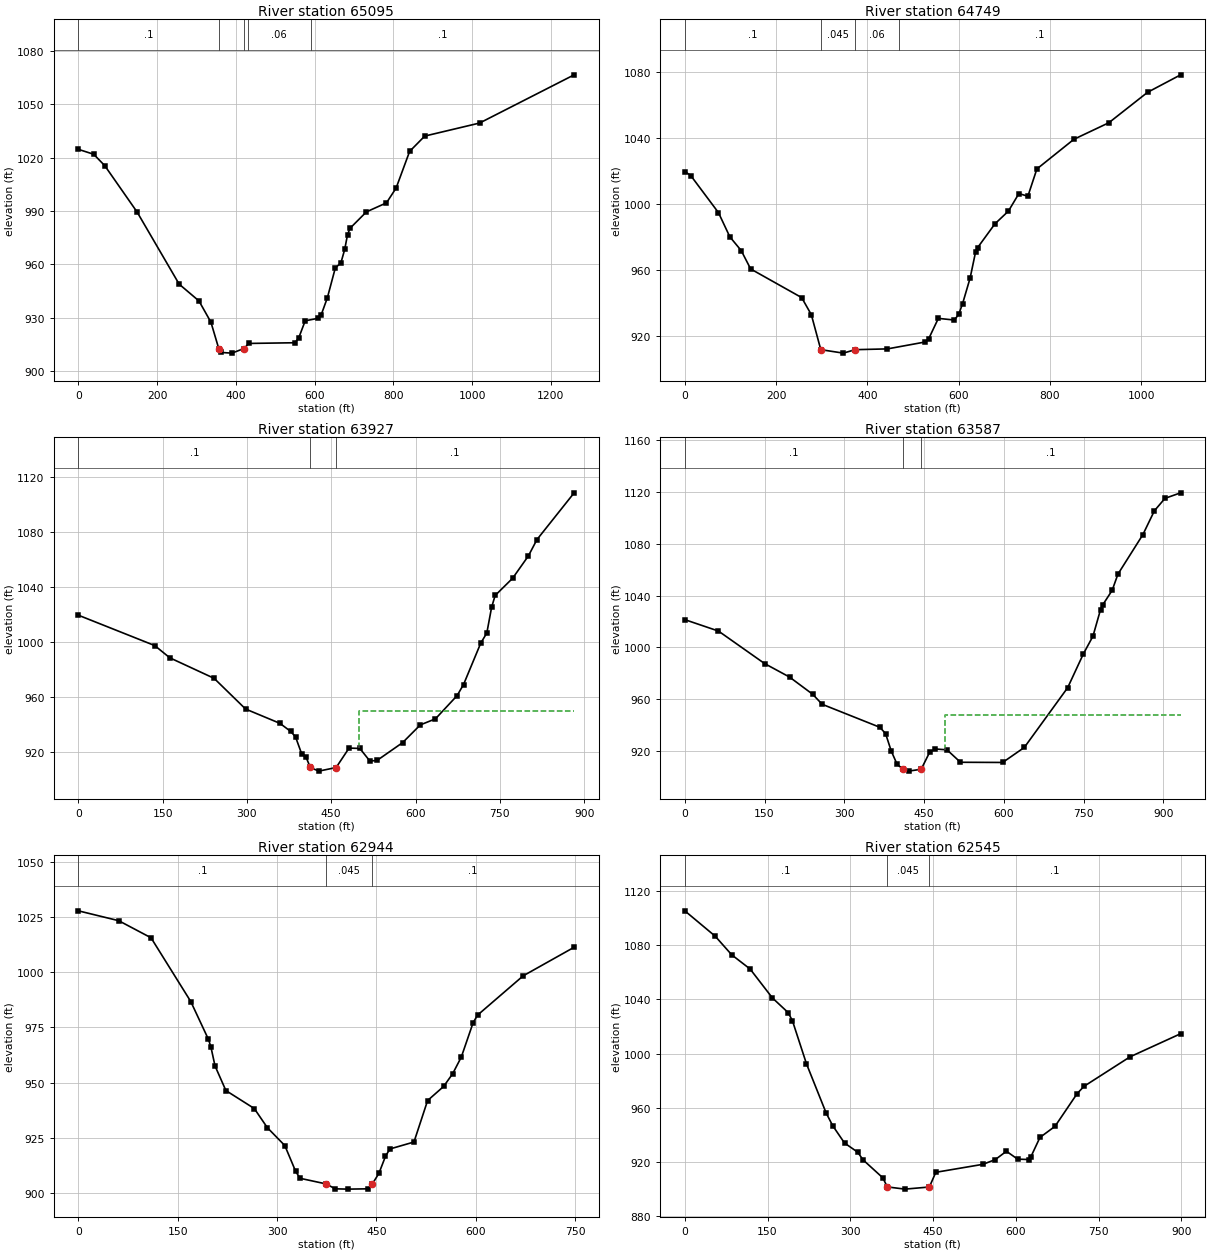
Type RM Length L Ch R = 1 ,65095   ,319.3,346.5,342.5
XS GIS Cut Line= 3
1642303.47851649490700.4403062961642896.16593669491060.991820255
1643437.16427039491225.796341555
#Sta/Elev= 30
       0 1024.68      39  1021.9    67.2 1015.47   149.2  989.43   256.1  948.84
   306.4   939.4   336.8  927.43   356.6  912.62   363.6  910.41     390  910.05
   420.8912.6396     433   915.5     550  915.89   559.6  918.52   576.2  928.22
   609.7  929.67   617.1  931.75   632.5  941.18   652.6   957.9     667  960.93
   676.5  968.34   683.7  976.68   690.1  980.28   731.6  989.49   782.6  994.57
   807.1  1002.9   841.4 1023.51   879.8 1032.13  1019.1 1039.46  1259.3 1066.58
#Mann= 5 ,-1,0
       0      .1       0   356.6    .045       0   420.8      .1       0
     430     .06       0     590      .1       0
Bank Sta=356.6,420.8
XS Rating Curve= 0 ,0
Exp/Cntr(USF)=0,0
Exp/Cntr=0.3,0.1

Type RM Length L Ch R = 1 ,64749   ,777.3,821.6,838
XS GIS Cut Line= 3
1642218.02322896490880.3333455271642634.48582858 491419.56396221
1642654.16785868491824.223920703
#Sta/Elev= 30
       0 1019.74      13  1017.3    73.8   994.8    98.7  980.14   123.6  971.83
   144.3  960.68   256.1  943.32   277.3  932.94  297.97911.7665   347.4  909.66
   373.2  911.75   444.1  912.23   525.7  916.36   534.6  918.45   555.6  930.73
   590.7  929.71   600.1  933.13   608.6  939.55   625.2  955.16   637.3  971.13
   641.7  973.62   679.6  988.02   709.1  995.73   732.1 1006.36   751.8 1004.76
   771.5 1021.28   852.7 1039.28   929.2 1049.29  1014.1 1067.75  1086.5 1078.34
#Mann= 4 ,-1,0
       0      .1       0  297.97    .045       0   373.2     .06       0
     470      .1       0
Bank Sta=297.97,373.2
XS Rating Curve= 0 ,0
Exp/Cntr(USF)=0,0
Exp/Cntr=0.3,0.1

Type RM Length L Ch R = 1 ,63927   ,325.8,340.6,350.3
XS GIS Cut Line= 2
1642103.44651217490957.2715217191641644.11376151491710.478451566
#Sta/Elev= 30
       0 1019.56   135.9  997.41   162.8  988.47   241.6  973.51   297.6  951.12
   358.7  940.69     378  934.74   386.5  930.75   397.2  918.63   405.1  916.05
   412.8908.4879   427.9  905.84   458.7908.4733   481.7  922.65   500.9  922.38
   518.8  913.16   531.6  913.67   576.9   926.6   608.5  939.56   635.4  943.97
   673.9   960.9   685.4  969.01   716.1  999.28   726.8 1006.56   735.3 1025.29
   741.6 1033.92   772.7 1046.49   800.7 1062.74     816 1074.69   882.2 1108.79
#Mann= 3 ,-1,0
       0      .1       0   412.8    .045       0   458.7      .1       0
#XS Ineff= 2 , 0
                          499.72          949.49
Permanent Ineff=
       F       F
Bank Sta=412.8,458.7
XS Rating Curve= 0 ,0
Exp/Cntr(USF)=0,0
Exp/Cntr=0.3,0.1

Type RM Length L Ch R = 1 ,63587   ,625.9,642.4,644.2
XS GIS Cut Line= 2
1642061.46448657490890.5941869461641214.41538186491280.780071915
#Sta/Elev= 30
       0 1021.47    63.3 1012.66     150  987.61     197  977.18   240.4  963.95
   258.4  956.17   366.8  938.45   377.6  933.59   388.4  920.02   399.3  909.93
   410.3906.0964     421  904.62   444.6 906.074   460.7  919.31   471.5   921.7
   493.2  921.04   518.5  911.45   597.9  911.31   638.6  922.89   720.2  969.01
   749.7  995.08   767.7 1008.69     782 1029.28   785.8 1032.71   803.8 1044.02
   814.7 1056.57   861.6 1087.04   883.3 1105.46   903.2 1115.03   932.6 1119.28
#Mann= 3 ,-1,0
       0      .1       0   410.3    .045       0   444.6      .1       0
#XS Ineff= 2 , 0
                          490.11          947.59
Permanent Ineff=
       F       F
Bank Sta=410.3,444.6
XS Rating Curve= 0 ,0
Exp/Cntr(USF)=0,0
Exp/Cntr=0.3,0.1

Type RM Length L Ch R = 1 ,62944   ,409.4,399.6,350.7
XS GIS Cut Line= 6
1642126.43346284490520.1150580051642030.61311643490494.374295846
1641937.16087551490477.0387005961641774.87707934 490462.77068451
1641627.98277931490444.2913423421641395.55653182490515.735531952
#Sta/Elev= 30
       0  1027.9    60.9 1023.43   109.7 1015.68   169.7  986.76   196.4  969.59
   200.1  966.17   206.3  957.57   222.7  946.38   265.6  938.22   285.3  929.54
   311.7  921.41   328.1  909.66   334.7  906.57   374.3     904   387.6   901.8
   406.7  901.66   437.2   901.8   443.5903.8785   453.7  908.82   463.6  916.53
   470.2  919.87   506.6  923.03   527.2  941.85   551.3  948.22     565  953.99
   578.1   961.6   595.9  977.17   602.7  980.62   671.4   998.4   748.4 1011.38
#Mann= 3 ,-1,0
       0      .1       0   374.3    .045       0   443.5      .1       0
Bank Sta=374.3,443.5
XS Rating Curve= 0 ,0
Exp/Cntr(USF)=0,0
Exp/Cntr=0.3,0.1

Type RM Length L Ch R = 1 ,62545   ,493.7,483.6,451.9
XS GIS Cut Line= 3
1642093.10759202489899.9731606431641812.22367222490078.417062634
1641347.93907537490402.259699581
#Sta/Elev= 30
       0 1105.55    55.1 1086.79    85.1    1073   118.4 1062.51   158.8 1041.13
   187.3  1030.3   195.1 1024.27   220.6  992.37   256.2  956.05   268.1  946.64
   289.5  933.84   313.3  927.08   323.3  921.31     359  908.06  367.08901.3628
     399  899.72  443.34901.2878     455  912.16   540.6  918.08     563  921.61
     583  927.74   603.3   921.9   623.1  921.62   627.1   923.4   643.8  937.95
   671.1  946.16   711.1   970.3   723.5  975.71   807.1  997.57   898.8 1014.66
#Mann= 3 ,-1,0
       0      .1       0  367.08    .045       0  443.34      .1       0
Bank Sta=367.08,443.34
XS Rating Curve= 0 ,0
Exp/Cntr(USF)=0,0
Exp/Cntr=0.3,0.1

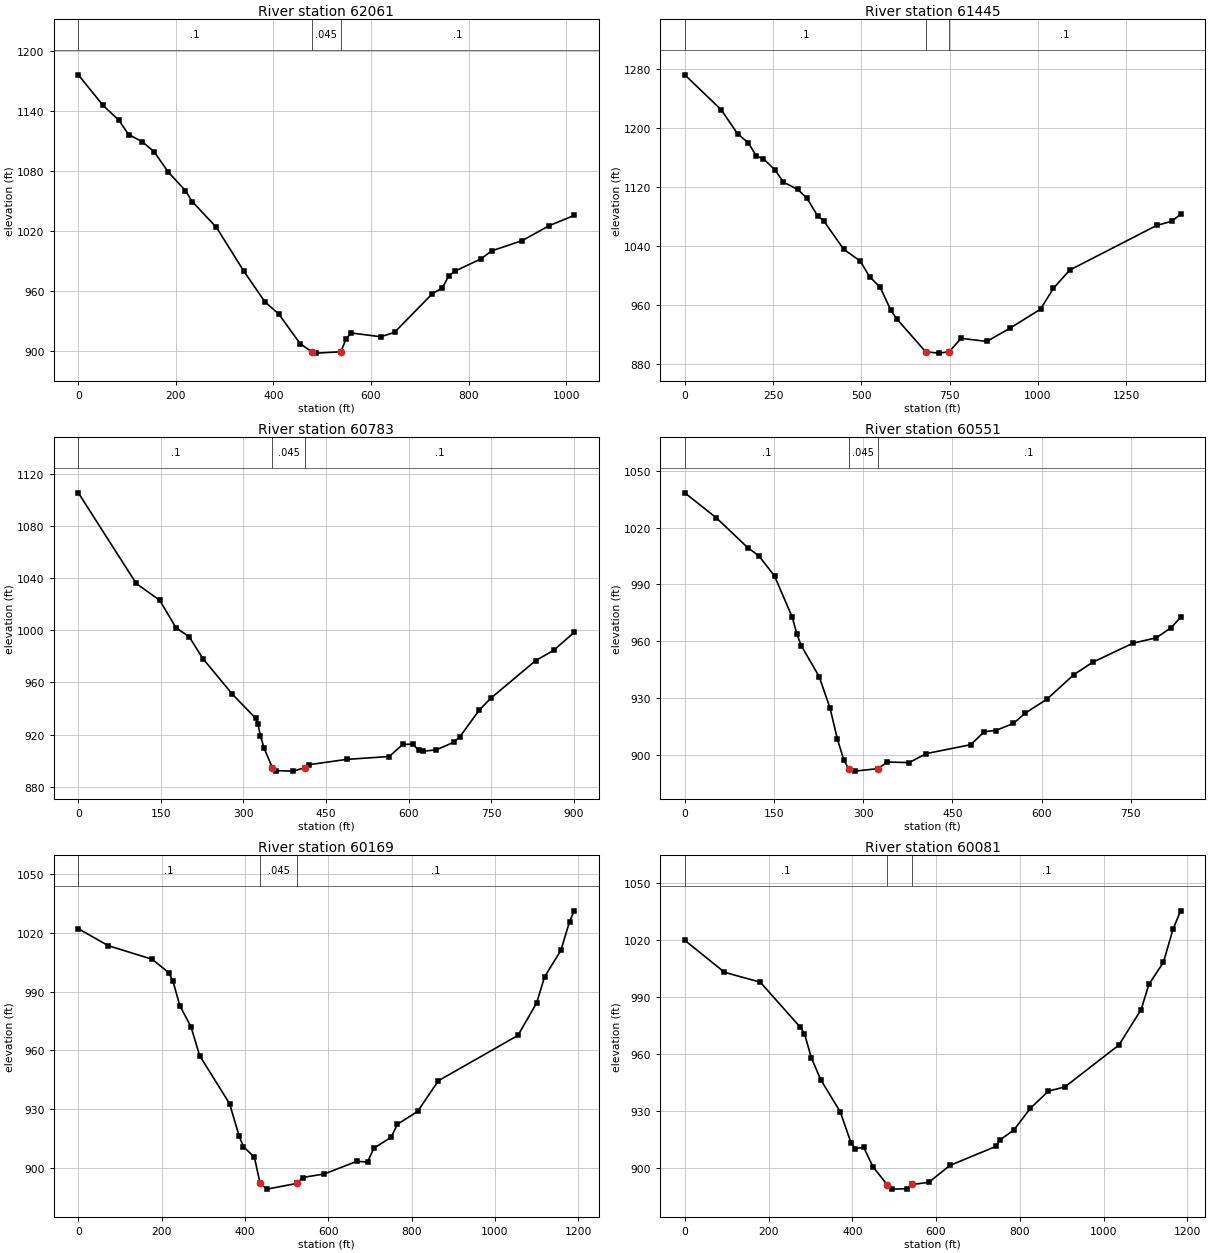
Type RM Length L Ch R = 1 ,62061   ,619.3,616.2,586.9
XS GIS Cut Line= 3
1641528.52090618489443.0839759251641283.50099965490042.067378895
1641196.70255299 490401.06744793
#Sta/Elev= 30
       0 1176.47    50.3 1145.99      83 1130.97   103.1 1116.57   130.8 1109.47
   155.6 1099.29   183.9 1079.24   219.4 1060.47   233.5 1049.35   283.2 1023.46
   338.8  979.94   382.6  948.77   410.8  936.71   454.6  906.99   478.1  898.87
     488  897.42   538.3   898.8     549  911.93   559.7  917.61   619.9  913.84
   648.2  918.21   725.9  957.08   746.1  962.67   759.6  975.11   773.1  979.87
   824.8  991.76   847.6  999.97   910.1 1010.24   964.4 1025.02  1016.5 1035.49
#Mann= 3 ,-1,0
       0      .1       0   478.1    .045       0   538.3      .1       0
Bank Sta=478.1,538.3
XS Rating Curve= 0 ,0
Exp/Cntr(USF)=0,0
Exp/Cntr=0.3,0.1

Type RM Length L Ch R = 1 ,61445   ,667.1,661.9,651.6
XS GIS Cut Line= 6
1640644.80158359489163.113506928 1640673.0610415489361.286995083
1640744.52185659489732.7688636781640769.75474575489905.954540923
1640828.79268542490353.8493144211640845.58005342490552.560531169
#Sta/Elev= 30
       0 1271.63   103.3  1224.2   149.9 1191.53   179.7 1179.71   202.9 1161.51
   222.9 1157.74   255.5 1142.81   279.5  1126.2   319.5 1116.51   345.8 1104.63
   376.3  1080.5     393 1074.23   449.9 1035.38   496.9 1019.35   523.6  998.02
   553.7  983.63   583.8   952.6   600.1  941.18   682.4896.3127   719.7  894.54
     749896.3464   782.7   914.6   855.5  910.37   921.8  928.48  1007.8  954.09
  1044.2  982.28  1090.5 1007.07  1336.8 1067.56  1379.6 1073.21  1404.7 1082.69
#Mann= 3 ,-1,0
       0      .1       0   682.4    .045       0     749      .1       0
Bank Sta=682.4,749
XS Rating Curve= 0 ,0
Exp/Cntr(USF)=0,0
Exp/Cntr=0.3,0.1

Type RM Length L Ch R = 1 ,60783   ,236.4,232.4,229.4
XS GIS Cut Line= 2
1639982.11945401489650.889666345 1640332.7928443490480.652054635
#Sta/Elev= 30
       0 1105.33   105.2 1035.83     148 1022.86   177.3 1001.94   201.4  994.96
   226.3  978.21   279.9  950.91   322.5  932.32   326.1  928.39   330.8  919.15
   337.5  909.54   352.4 894.582     360   892.3   390.1  891.94   412.1894.5771
   418.7  896.85   487.7  900.95   564.7  903.14   589.6  912.45   607.9  912.62
   618.1  907.86   625.3  907.12   650.5   908.3   682.2  914.09   693.2  918.27
   728.5  938.84   749.9  948.03   830.7  976.63   863.3  984.49   900.8  998.32
#Mann= 3 ,-1,0
       0      .1       0   352.4    .045       0   412.1      .1       0
Bank Sta=352.4,412.1
XS Rating Curve= 0 ,0
Exp/Cntr(USF)=0,0
Exp/Cntr=0.3,0.1

Type RM Length L Ch R = 1 ,60551   ,398.1,381.2,315.8
XS GIS Cut Line= 2
1639789.25404349489865.3380617141640194.05733967490593.983994843
#Sta/Elev= 30
       0 1038.49    53.2 1025.21   105.8 1009.47   124.5 1005.16   150.8   994.5
   180.8  972.58   188.3  963.87   195.8  957.57   225.9  941.25   244.2  924.56
   256.3  908.43   267.2  897.25   275.2892.5478   285.9  891.25   324.4892.5615
   340.7  896.07   376.9  895.76     406  900.53   480.7  905.24   503.6  912.17
   522.4   912.7   552.4  916.48   572.3  921.95   608.7  929.29   653.7  942.21
   685.7  948.85   753.3  958.93   792.6  961.79   817.7   967.2   833.5   972.6
#Mann= 3 ,-1,0
       0      .1       0   275.2    .045       0   324.4      .1       0
Bank Sta=275.2,324.4
XS Rating Curve= 0 ,0
Exp/Cntr(USF)=0,0
Exp/Cntr=0.3,0.1

Type RM Length L Ch R = 1 ,60169   ,81.1,88.9,100
XS GIS Cut Line= 5
1639671.28013726 489988.574290831639615.76519509490385.447068885
1639770.49833177490381.903561939 1639895.7022439 490341.74381654
1640141.38539222490781.138677959
#Sta/Elev= 30
       0 1022.13    71.6 1013.46   177.6 1006.48   217.4  999.58   227.3  995.22
   243.9  982.64   270.4  972.04   291.2  957.25   363.1   932.7   386.3  915.91
   396.3  910.78   422.8  905.24   436.4  891.92     453     889   525.4891.9547
   538.3  894.94   590.6  896.76   668.4  903.18   694.4  902.88   709.4  909.91
     751   915.5   765.8  922.09   814.7  928.74   864.4  944.41  1055.3  967.55
  1100.4  984.19  1119.2  997.44  1158.5 1011.05  1179.3 1025.74  1190.4 1031.26
#Mann= 3 ,-1,0
       0      .1       0   436.4    .045       0   525.4      .1       0
Bank Sta=436.4,525.4
XS Rating Curve= 0 ,0
Exp/Cntr(USF)=0,0
Exp/Cntr=0.3,0.1

Type RM Length L Ch R = 1 ,60081   ,292.5,314.1,367.1
XS GIS Cut Line= 5
1639615.76519509489994.480135741 1639581.5112946490446.867855966
1639746.87495212490450.411362912 1639868.5353573490423.244476319
1640090.59512598490803.580888623
#Sta/Elev= 30
       0 1019.89    94.8 1003.08   180.4  997.85   275.8  974.16   285.7  970.86
   302.1  958.17   325.1  946.37   371.2  929.67   397.5  912.99   407.4  910.25
   427.1  911.02   449.3  900.75  483.18891.3537   494.2  888.96   530.3  889.17
  543.82891.4001   582.8  892.55   633.1  901.41   743.8  911.53   751.8  914.73
     786   920.1   825.3  931.48   868.5  940.56   907.6  942.73  1036.8  964.78
    1090  983.49  1108.3  996.72  1143.1 1008.31  1165.9 1025.69  1184.2 1035.42
#Mann= 3 ,-1,0
       0      .1       0  483.18    .045       0  543.82      .1       0
Bank Sta=483.18,543.82
XS Rating Curve= 0 ,0
Exp/Cntr(USF)=0,0
Exp/Cntr=0.3,0.1

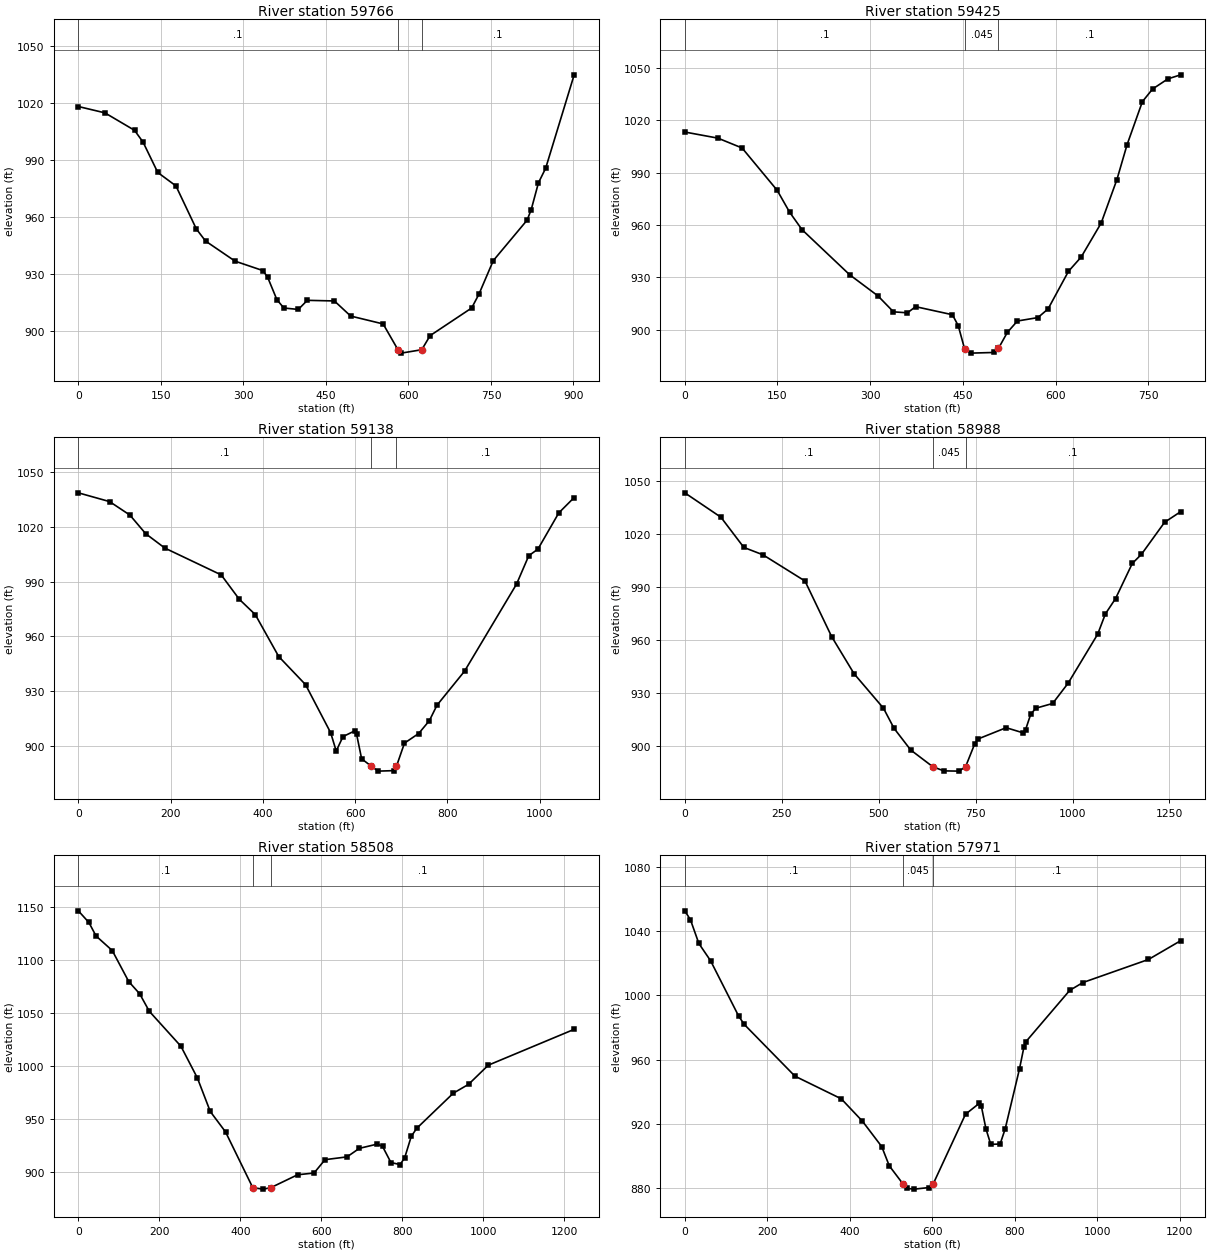
Type RM Length L Ch R = 1 ,59766   ,327.1,341,365.9
XS GIS Cut Line= 3
1639539.43080189489985.8499349431639393.40743874490315.902742072
1639379.40519844490855.989153736
#Sta/Elev= 30
       0 1018.31    48.3 1014.97   102.1 1005.77   117.6  999.56   144.4  983.52
   177.4  976.45   214.5  953.74   231.2  947.38     285  936.75   335.3  931.81
   343.9  928.41   360.9  916.46   373.5  912.06   399.8  911.31   416.2  916.11
   465.4  915.78     495  907.82     554  903.66  580.85890.1033   586.9  888.27
   624.2890.0695   639.4   897.5   714.9  912.07     728  919.27   754.2  937.05
   815.7   958.4   823.2     964   836.3  978.09   849.4  985.75   901.2 1035.02
#Mann= 3 ,-1,0
       0      .1       0  580.85    .045       0   624.2      .1       0
Bank Sta=580.85,624.2
XS Rating Curve= 0 ,0
Exp/Cntr(USF)=0,0
Exp/Cntr=0.3,0.1

Type RM Length L Ch R = 1 ,59425   ,273.9,287.8,297.8
XS GIS Cut Line= 3
1639374.53719719 489918.210328971639220.87717048490286.663941414
1638900.33905024490531.198177476
#Sta/Elev= 30
       0 1013.19    53.6 1009.69    92.7 1004.05   149.5  979.81   169.6   967.3
   189.7  957.28   266.8  931.46   312.6  919.34   337.7  910.22   360.3  909.65
   373.5  913.18   433.1  908.56   442.5  902.29  452.71889.1262   462.8  886.57
   500.7  886.95  507.52889.2295     522  898.46   538.3  904.97   571.4  906.92
   587.9  911.88   620.9  933.42   641.5  941.62   673.8  961.06   699.3  985.97
   715.8 1006.01   740.5 1030.58     757 1037.83   781.8 1043.63   802.4 1045.95
#Mann= 3 ,-1,0
       0      .1       0  452.71    .045       0  507.52      .1       0
Bank Sta=452.71,507.52
XS Rating Curve= 0 ,0
Exp/Cntr(USF)=0,0
Exp/Cntr=0.3,0.1

Type RM Length L Ch R = 1 ,59138   ,110,149.3,143
XS GIS Cut Line= 4
 1639275.0669757489582.2322201281639000.43612725490132.169617181
1638888.06548085490156.3705647341638837.59698225490498.002739746
#Sta/Elev= 30
       0 1038.68    67.8 1033.87   111.8 1026.48     146 1016.28   187.6 1008.38
   309.8  993.67     349   980.3   383.6  971.92   434.5   948.9   492.6   933.5
   547.1  907.11   559.1  897.09   573.8  905.01   599.5  908.17   603.2  906.42
   614.2  892.83   635.6888.6814     650  886.07   683.6  886.34   689.7888.7043
   707.1  901.43   737.9   906.7   761.1  913.75   777.6  922.22   837.3  940.86
   950.1  988.63   976.6  1004.2   996.5 1007.83  1041.7 1027.68    1075  1036.1
#Mann= 3 ,-1,0
       0      .1       0   635.6    .045       0   689.7      .1       0
Bank Sta=635.6,689.7
XS Rating Curve= 0 ,0
Exp/Cntr(USF)=0,0
Exp/Cntr=0.3,0.1

Type RM Length L Ch R = 1 ,58988   ,556.9,480.1,447.2
XS GIS Cut Line= 6
1639247.36054278489564.733420391 1639021.3343795490054.699813052
1638973.21268022490045.9504131831638795.30821621490041.575713249
1638735.52065044490059.0745129871638804.05761608490503.835672992
#Sta/Elev= 30
       0  1043.3    93.2 1029.49   152.3 1012.42   201.6 1008.25     310  993.42
   378.7     962   436.6  940.98   512.4  921.49   539.6  910.14   582.6  897.87
   639.7888.3823     668  886.05   707.3  885.91   724.1  888.37   747.8  901.36
   756.6  904.12   828.8  910.47   872.9  907.54     879   909.4   892.3  918.15
   905.5  921.49   948.7  924.17   988.5   935.6  1064.9  963.36  1084.8  974.85
  1110.9  983.47  1154.1 1003.35  1177.7 1008.51  1237.5 1026.65  1278.8 1032.63
#Mann= 3 ,-1,0
       0      .1       0   639.7    .045       0   724.1      .1       0
Bank Sta=639.7,724.1
XS Rating Curve= 0 ,0
Exp/Cntr(USF)=0,0
Exp/Cntr=0.3,0.1

Type RM Length L Ch R = 1 ,58508   ,595.5,537.5,484.5
XS GIS Cut Line= 3
1638363.67115601489391.2036563231638550.32501988490104.279745643
1638788.01704966490530.083872599
#Sta/Elev= 30
       0 1145.93    26.1 1134.96    43.7 1122.27    83.8 1108.52   124.5 1079.32
   151.6 1067.74   175.3 1051.32   253.4 1018.39     294  988.57   325.9  956.93
   363.6  937.72     431885.1279   456.8  883.81     475885.1109   541.6  897.33
   582.3  898.99   609.4  911.56   663.7  914.18   694.2  922.21   738.4  926.22
   751.4   924.1   772.2  908.83   794.8  906.97   806.1  913.25   822.4  933.48
   835.8  941.04   926.3  974.19   963.9  982.49  1012.7 1000.55  1224.8 1034.31
#Mann= 3 ,-1,0
       0      .1       0     431    .045       0     475      .1       0
Bank Sta=431,475
XS Rating Curve= 0 ,0
Exp/Cntr(USF)=0,0
Exp/Cntr=0.3,0.1

Type RM Length L Ch R = 1 ,57971   ,114.2,111.5,121.7
XS GIS Cut Line= 5
1637819.75013083490212.1890106931638267.42775745490337.597075482
1638401.58522211 490199.064910891638443.87398814490174.274944594
1638777.80941648490540.291505779
#Sta/Elev= 30
       0 1052.61    13.7 1047.05    34.1 1032.29    62.5 1021.57   130.7  987.08
   144.3  981.93     267  949.79   379.4  935.69   430.7  921.77   477.5  905.96
   495.8  894.01   528.3882.9959   538.4  879.95   556.9  879.52   591.8   880.5
   602.7     883   680.6   926.1   714.1  932.89   718.7  931.51   730.3  916.88
   741.9  907.33   764.6  907.61   776.8  916.98   811.6  954.43   822.3  967.93
   826.8  971.14   933.3 1003.14   965.3 1008.01  1124.3 1022.37  1202.2 1034.01
#Mann= 3 ,-1,0
       0      .1       0   528.3    .045       0   602.7      .1       0
Bank Sta=528.3,602.7
XS Rating Curve= 0 ,0
Exp/Cntr(USF)=0,0
Exp/Cntr=0.3,0.1

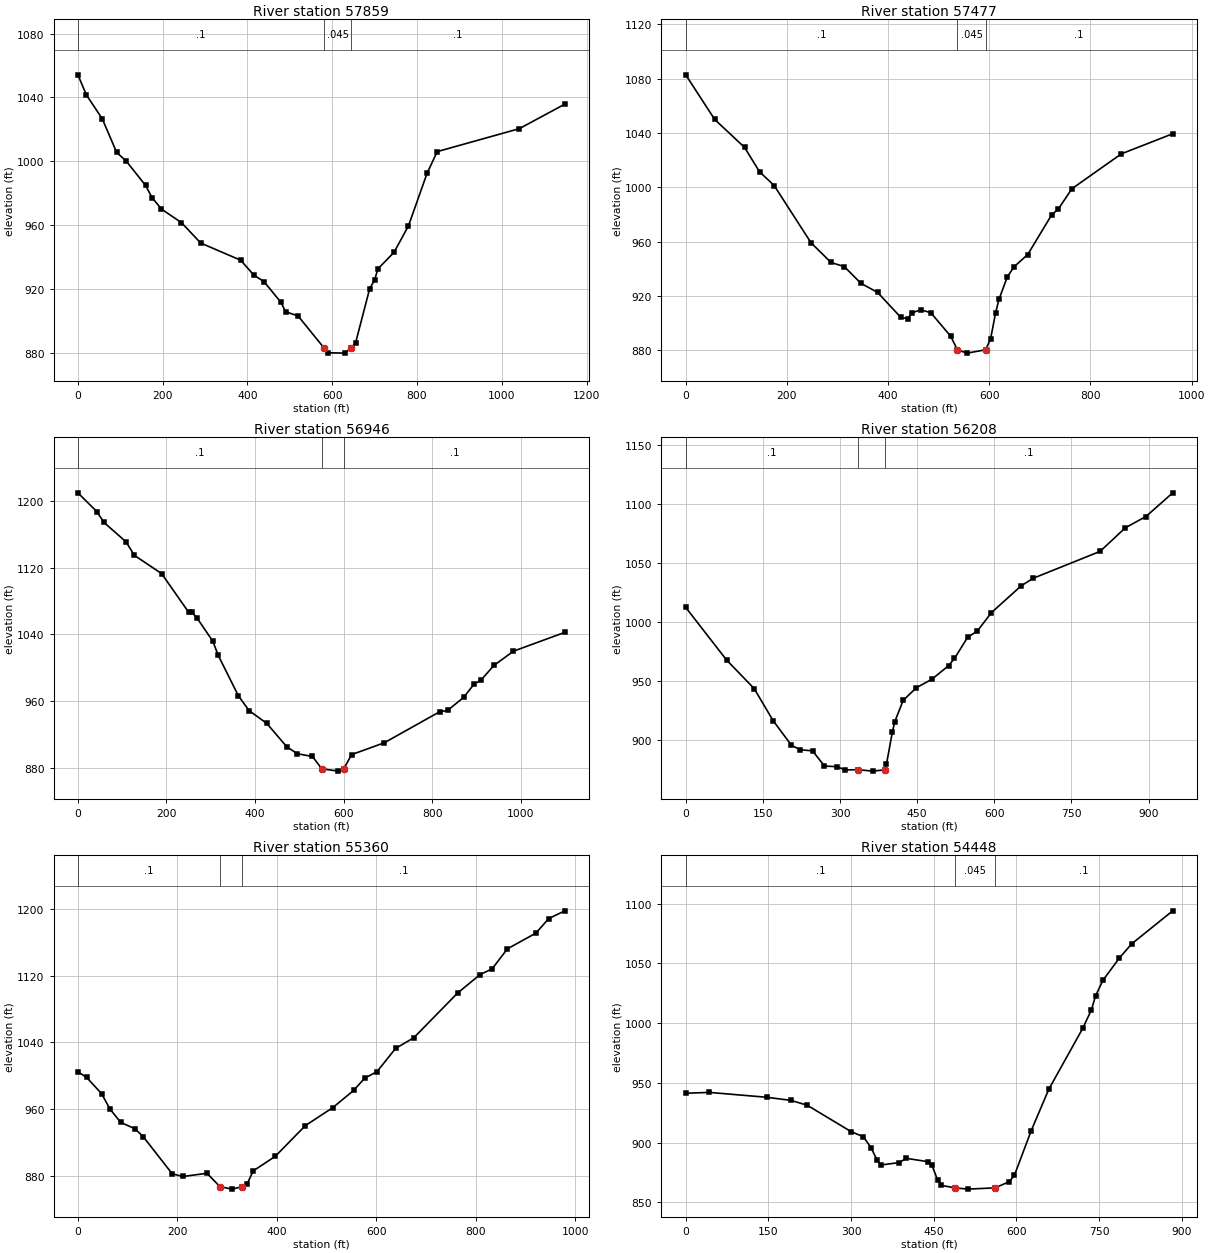
Type RM Length L Ch R = 1 ,57859   ,321.7,382.1,380
XS GIS Cut Line= 4
1637808.08426433490293.850076137 1638324.2988566490435.298707352
1638422.00048847490302.5994760061638769.06001661490586.954971747
#Sta/Elev= 30
       0  1054.2    20.1 1041.58    57.5 1026.62    91.5 1005.51   113.4 1000.32
   159.6  984.89   174.8  977.28     197  970.06   244.3  961.54   289.6  948.77
   384.1  937.96   414.7  928.73   439.2  924.51   479.2  911.49   489.9   905.7
   519.3  903.06   580.7882.9465   590.4  879.97   629.4  879.74   645.1882.9439
   655.2  886.33     688  919.92     700  925.76   707.6  932.51   745.8  942.98
   779.7  959.49   823.8  992.61   847.6 1006.07  1041.2 1020.45  1148.7 1035.85
#Mann= 3 ,-1,0
       0      .1       0   580.7    .045       0   645.1      .1       0
Bank Sta=580.7,645.1
XS Rating Curve= 0 ,0
Exp/Cntr(USF)=0,0
Exp/Cntr=0.3,0.1

Type RM Length L Ch R = 1 ,57477   ,539.6,531.2,507.5
XS GIS Cut Line= 3
1637809.84853807 490684.858204191638439.35897009490722.860146281
1638763.20160704490650.160778803
#Sta/Elev= 30
       0 1082.89    57.1  1050.1   116.3 1029.43   145.8 1011.53   174.8 1001.38
   247.7  959.22   287.2  944.73   313.5  941.67   346.3   929.4   379.2  922.69
   425.2   904.3   438.4  903.42   448.2  907.85   464.7  909.88   484.4  907.75
   523.8   890.4     537  880.41   556.1     878   592.8  880.45   602.7  888.75
   612.6   907.9   619.1  917.58   635.7  934.18     649  941.58     676  950.61
   723.1  979.68   736.6  984.21   763.5  999.08     861 1024.71   962.6 1039.51
#Mann= 3 ,-1,0
       0      .1       0     537    .045       0   592.8      .1       0
Bank Sta=537,592.8
XS Rating Curve= 0 ,0
Exp/Cntr(USF)=0,0
Exp/Cntr=0.3,0.1

Type RM Length L Ch R = 1 ,56946   ,717.2,738.2,710.2
XS GIS Cut Line= 6
 1637985.3321547491525.401115478 1638292.2452651491326.520597428
1638515.31207617491188.1278295821638647.61496118491093.361286834
1638718.79362459491030.6448768381638897.60997197 490913.18927509
#Sta/Elev= 30
       0 1209.53    42.8 1187.01    58.9 1174.02   108.7 1150.87   127.6  1134.6
   189.1  1112.8     250  1066.6   257.8 1066.32   269.7 1059.08   304.7  1031.8
   317.1 1014.67   362.3  966.56   386.5  948.68   426.4  933.46   471.6  905.42
   495.5     897   529.7  893.69   550.9 878.937   588.5  876.15   600.5  878.89
   618.1  895.92   691.9  910.09   816.9  947.23   834.8  948.83   871.1  964.39
     895  980.47   910.4  985.17   939.7  1002.8   983.8 1019.84  1099.9 1042.42
#Mann= 3 ,-1,0
       0      .1       0   550.9    .045       0   600.5      .1       0
Bank Sta=550.9,600.5
XS Rating Curve= 0 ,0
Exp/Cntr(USF)=0,0
Exp/Cntr=0.3,0.1

Type RM Length L Ch R = 1 ,56208   ,825.7,847.7,829.5
XS GIS Cut Line= 2
1638735.54467349491929.627368716 1639394.0862515491249.134404774
#Sta/Elev= 30
       0 1012.25    79.4  967.73   133.1   943.5   169.9  916.41   205.5  895.53
   222.7  891.69   246.6  890.81   269.7  877.93   293.5   877.4   310.6  874.66
   334.7  874.82   364.3  873.62  386.73874.7275   390.3  879.46   401.9  906.95
   406.4  915.42   422.8  933.49   448.3  944.24   478.5  951.37     511   962.9
   522.6  969.02   548.1  986.89   567.1   992.3   594.5 1007.86   652.1 1030.48
   675.6 1036.94   805.7 1059.71   854.9 1079.72   894.9 1089.24     947 1109.31
#Mann= 3 ,-1,0
       0      .1       0   334.7    .045       0  386.73      .1       0
Bank Sta=334.7,386.73
XS Rating Curve= 0 ,0
Exp/Cntr(USF)=0,0
Exp/Cntr=0.3,0.1

Type RM Length L Ch R = 1 ,55360   ,876.2,912.5,906
XS GIS Cut Line= 2
1639256.89008941492459.2045543641640052.62782951 491888.46852009
#Sta/Elev= 30
       0 1004.93    17.4  998.35    47.5  978.94    64.4  960.57      86  944.55
   114.3  937.03   131.1  927.64   189.8  882.96   211.2  879.84   259.6  883.66
   285.6867.7504   309.7  864.74   330.9  867.72   340.3  870.87   352.5   886.5
   396.9  903.92   457.5  940.71   512.2  961.99   554.4  982.63   576.6  997.31
   601.3 1005.07   638.9 1032.92   675.5 1045.67   763.5 1099.06   808.7 1121.19
   832.9 1127.97   863.7 1151.93     921 1170.74   946.9 1188.15   979.3 1197.37
#Mann= 3 ,-1,0
       0      .1       0   285.6    .045       0   330.9      .1       0
Bank Sta=285.6,330.9
XS Rating Curve= 0 ,0
Exp/Cntr(USF)=0,0
Exp/Cntr=0.3,0.1

Type RM Length L Ch R = 1 ,54448   ,866.5,910,938.9
XS GIS Cut Line= 2
1639287.07324507 492969.574277321640156.89691269493125.977902097
#Sta/Elev= 30
       0  941.36    42.7  942.08     147     938   190.4  935.44   220.4  931.37
   299.8  909.33   322.4  904.94   336.5  895.66     347  885.64   353.7   881.3
     387  883.31   400.4  886.89   440.4  884.05   446.7  881.19     457  868.89
   463.7  864.25     489862.2212   511.7  861.14   561.5862.2147     587  867.35
   596.5  872.74     627  910.09   658.8  944.62   720.4  995.63   736.1 1011.06
   743.7  1022.7     757 1035.85     787 1054.51   809.2 1066.36   883.8 1094.02
#Mann= 3 ,-1,0
       0      .1       0     489    .045       0   561.5      .1       0
Bank Sta=489,561.5
XS Rating Curve= 0 ,0
Exp/Cntr(USF)=0,0
Exp/Cntr=0.3,0.1