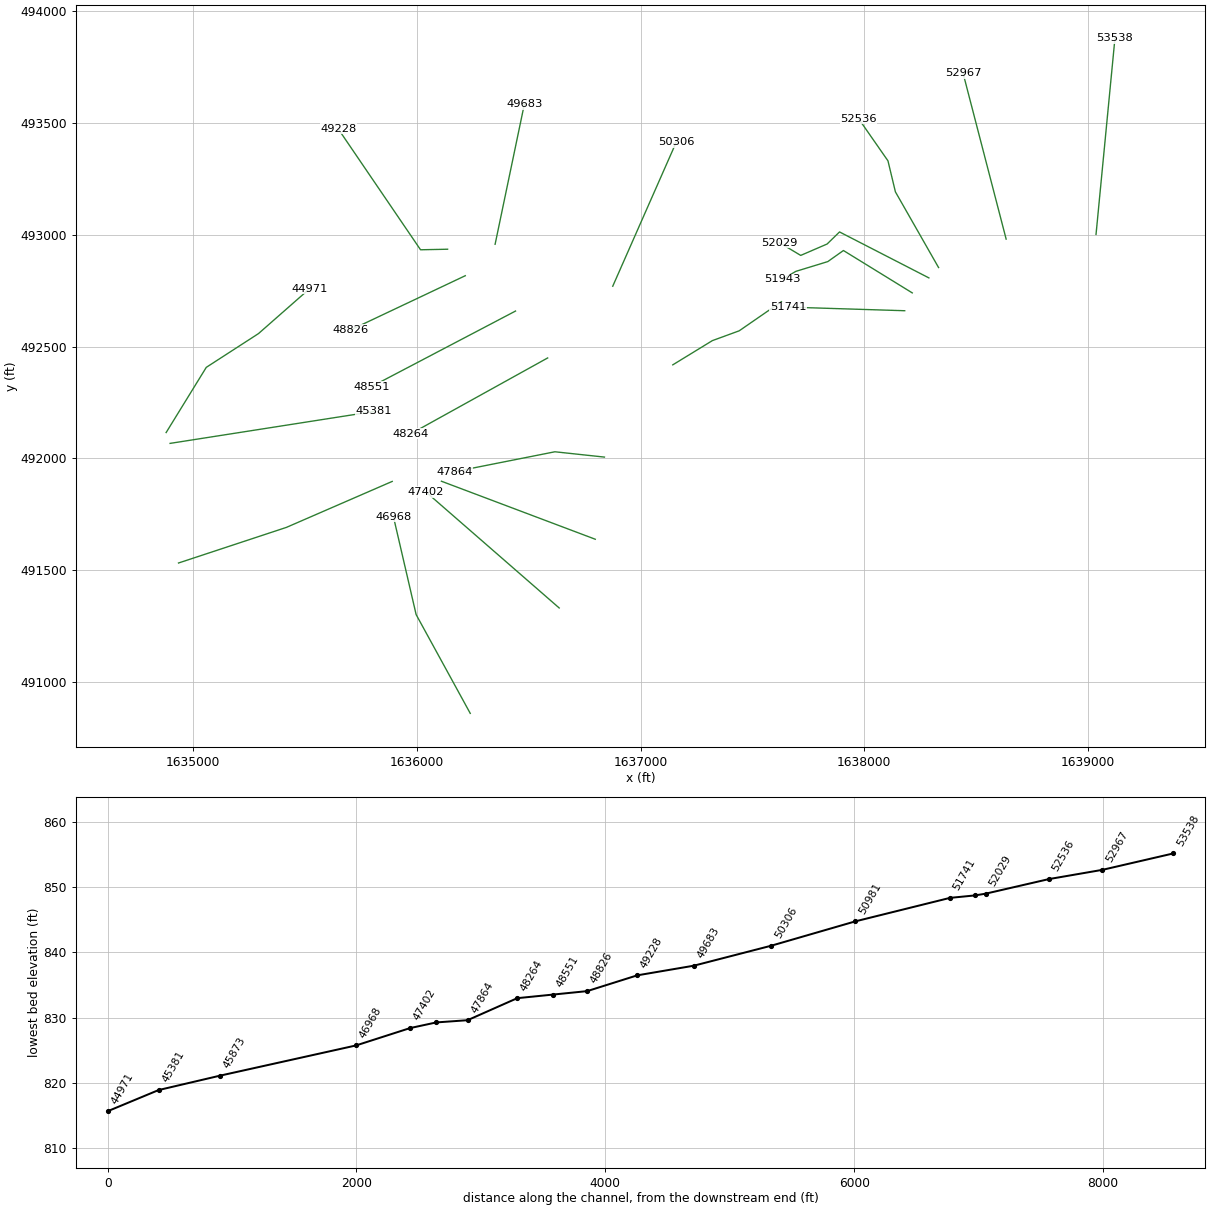
HEC-RAS study GraveCk1.prj: GraveCk1

--- GraveCk1.g01 (geometry) --- (continued)

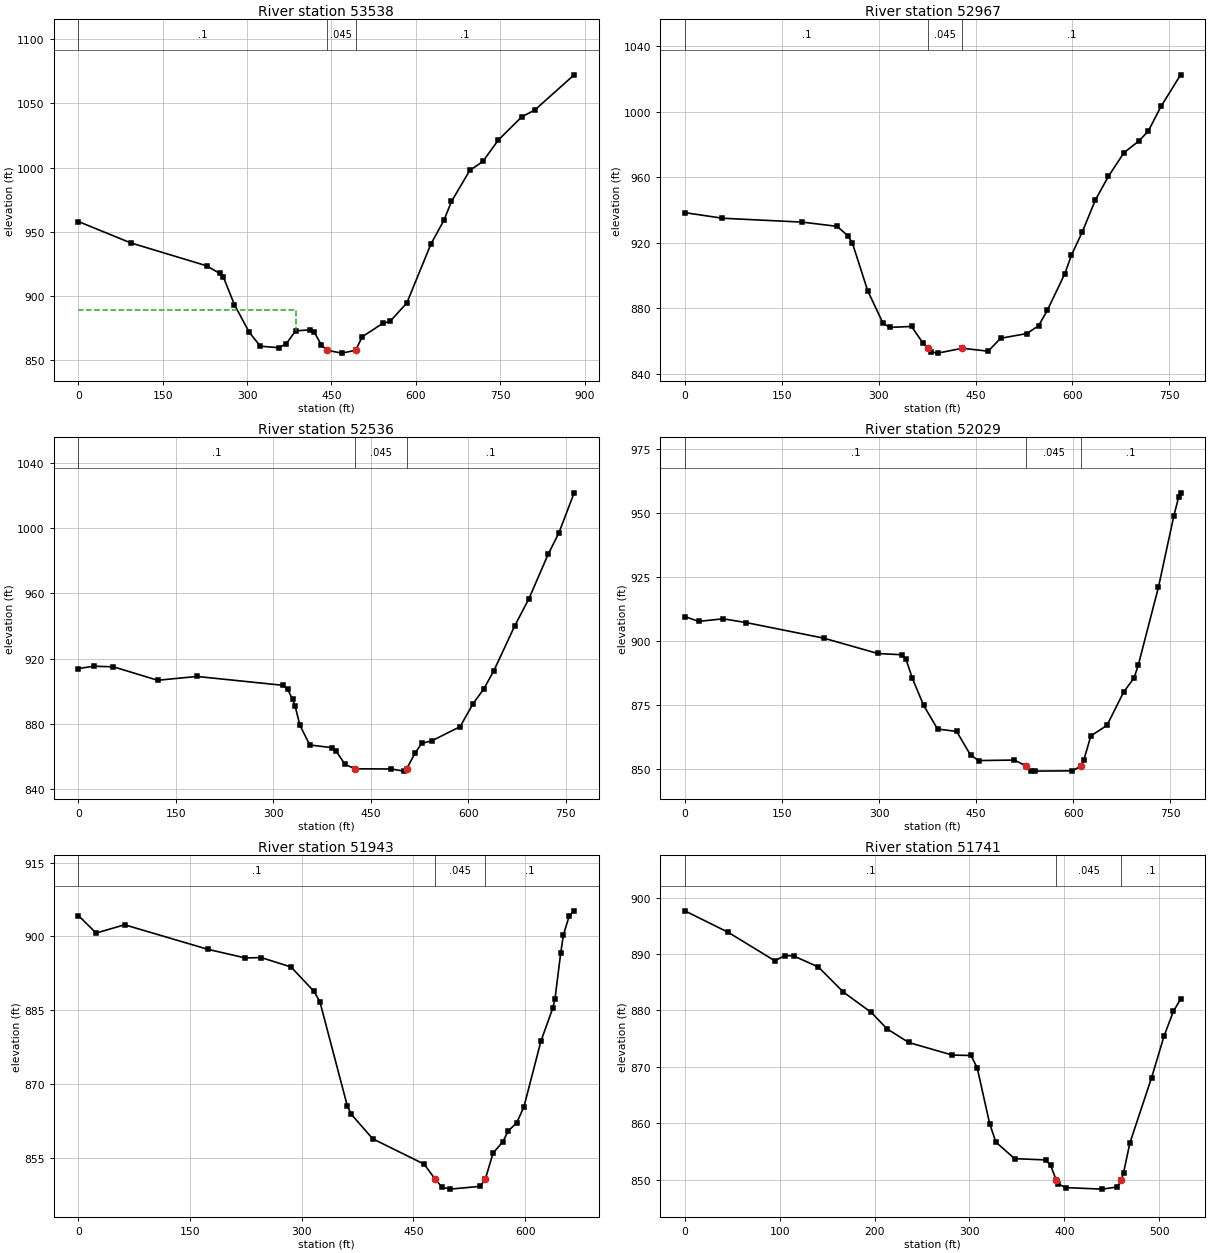
Type RM Length L Ch R = 1 ,53538   ,562.4,570.7,578
XS GIS Cut Line= 2
1639036.75193698493001.8204734981639121.35327389 493879.27388898
#Sta/Elev= 30
       0  957.88    92.9  941.25     228  923.33   251.1  917.42   257.7  914.69
   277.4  893.11   303.8  871.43   323.6  860.57   356.5   859.4   369.7  862.52
   386.2  872.53   412.6  873.36   419.2  871.78   432.3  861.32   442.2  857.36
   468.6  855.17  492.95857.3934   504.9  868.01   541.1  878.36   554.3     880
     584   894.3     627  940.45   649.9  958.76   663.4  973.54     696  997.77
   719.1 1004.72   746.9 1021.56   788.3 1039.56   811.4 1044.85   881.5 1072.36
#Mann= 3 ,-1,0
       0      .1       0   442.2    .045       0  492.95      .1       0
#XS Ineff= 2 , 0
             387  888.76
Permanent Ineff=
       F       F
Bank Sta=442.2,492.95
XS Rating Curve= 0 ,0
Exp/Cntr(USF)=0,0
Exp/Cntr=0.3,0.1

Type RM Length L Ch R = 1 ,52967   ,430.6,430.6,427.3
XS GIS Cut Line= 2
1638634.86811708492980.9585500021638442.14870293493723.731292039
#Sta/Elev= 30
       0  938.46    58.2  935.04     182  932.66   235.7  930.07   252.6  924.26
   259.4  919.85   283.1  890.71   306.8   870.9     317  868.36   350.9  868.94
   368.1  859.09  376.74855.5851   381.4  853.28   391.6  852.65   429.6  855.64
   469.5  853.82   488.8  861.72   529.2  864.59   547.5  869.35   561.1  878.77
   588.2  901.19   598.3  912.34   615.3  926.77   635.6  946.31   655.6  960.58
   679.7  975.07   703.4  982.37   717.5  988.39   737.3 1003.51   767.4 1022.62
#Mann= 3 ,-1,0
       0      .1       0  376.74    .045       0   429.6      .1       0
Bank Sta=376.74,429.6
XS Rating Curve= 0 ,0
Exp/Cntr(USF)=0,0
Exp/Cntr=0.3,0.1

Type RM Length L Ch R = 1 ,52536   ,440.1,506.8,558.4
XS GIS Cut Line= 4
1638332.67710906492853.6988195871638139.68628906493192.414573861
1638106.50375326493331.0132908661637974.74501808493520.492761429
#Sta/Elev= 30
       0  914.01    23.9  915.39    54.1  915.03     122  906.82   182.5  909.14
   314.6  903.74   322.2  901.21   329.7  895.29   333.5  891.21     341  879.33
   356.1  867.24   390.5  865.58   396.8   863.5   410.3  855.43   425.9  852.63
   481.2  852.55   501.4  851.23   505.1852.4969   518.4  862.34   528.4  868.21
   543.9  869.73   587.6  878.44   607.5   892.5   623.6  901.23   639.6  912.72
   671.5  939.98   693.6   956.8     723  983.83   739.4  996.78   763.1 1021.48
#Mann= 3 ,-1,0
       0      .1       0   425.9    .045       0   505.1      .1       0
Bank Sta=425.9,505.1
XS Rating Curve= 0 ,0
Exp/Cntr(USF)=0,0
Exp/Cntr=0.3,0.1

Type RM Length L Ch R = 1 ,52029   ,95.4,86,75.2
XS GIS Cut Line= 5
1638289.41609869492807.3464726761637889.86017134493012.957369596
 1637834.4473055492959.0027370711637716.33040727492907.964571169
1637621.54524202492964.835670317
#Sta/Elev= 30
       0  909.57    21.4  907.65    59.1  908.67    95.2  907.17     215  901.07
   298.1  895.08     335  894.59   341.7  892.81   351.4  885.45   368.9  874.77
   390.4   865.5   419.9  864.55   441.5  855.23     454  853.14     509  853.33
   527.2  851.04   534.3  849.13   541.4     849   598.6  849.12  612.34 851.007
   616.5  853.44   627.2  862.78   652.2  866.96   677.8  879.93   694.1  885.57
   700.6  890.65   731.7  921.11   755.3  948.86   762.7  956.22   765.9  958.02
#Mann= 3 ,-1,0
       0      .1       0   527.2    .045       0  612.34      .1       0
Bank Sta=527.2,612.34
XS Rating Curve= 0 ,0
Exp/Cntr(USF)=0,0
Exp/Cntr=0.3,0.1

Type RM Length L Ch R = 1 ,51943   ,203.7,202,178.6
XS GIS Cut Line= 5
 1638215.0461998492740.2677403471637907.35897107492929.838070841
1637837.36377212 492880.25813825 1637694.4569076492836.511138905
1637634.66934182 492801.51353943
#Sta/Elev= 30
       0  904.26    23.9   900.7    62.1  902.38   173.9   897.4   224.2  895.65
   245.7  895.72   285.7  893.81   316.5  888.86   324.4  886.77   361.4  865.53
   366.8  863.88   395.3  858.95   464.4   853.8  478.99850.8033   488.4  849.13
   499.2  848.73   539.9   849.3   546.7  850.82     557  856.05   570.1  858.34
   577.6   860.6   588.5  862.12   598.4  865.41   621.2  878.73   637.2  885.47
   640.2  887.37   647.8  896.63   651.5  900.33   659.2  904.15   665.9  905.21
#Mann= 3 ,-1,0
       0      .1       0  478.99    .045       0   546.7      .1       0
Bank Sta=478.99,546.7
XS Rating Curve= 0 ,0
Exp/Cntr(USF)=0,0
Exp/Cntr=0.3,0.1

Type RM Length L Ch R = 1 ,51741   ,821.6,760.3,622.4
XS GIS Cut Line= 2
 1638181.4663598492660.4255807461637659.14192024492676.740800945
#Sta/Elev= 30
       0  897.64    45.6  893.85    94.9  888.79   105.5  889.72   114.6  889.66
   140.8  887.69   167.1  883.25   196.6  879.64     213  876.76     236  874.32
     282  872.09   301.7  872.02   308.2  869.82   321.3  859.96   327.9  856.67
   347.6  853.75   380.4  853.52   385.6  852.56  391.23850.0545   393.6  849.27
   401.5  848.62   439.7  848.35   455.9  848.73  460.24849.9865   462.5  851.28
   469.1  856.51     492   868.1   505.2  875.49     515  879.85   522.6  882.01
#Mann= 3 ,-1,0
       0      .1       0  391.23    .045       0  460.24      .1       0
Bank Sta=391.23,460.24
XS Rating Curve= 0 ,0
Exp/Cntr(USF)=0,0
Exp/Cntr=0.3,0.1

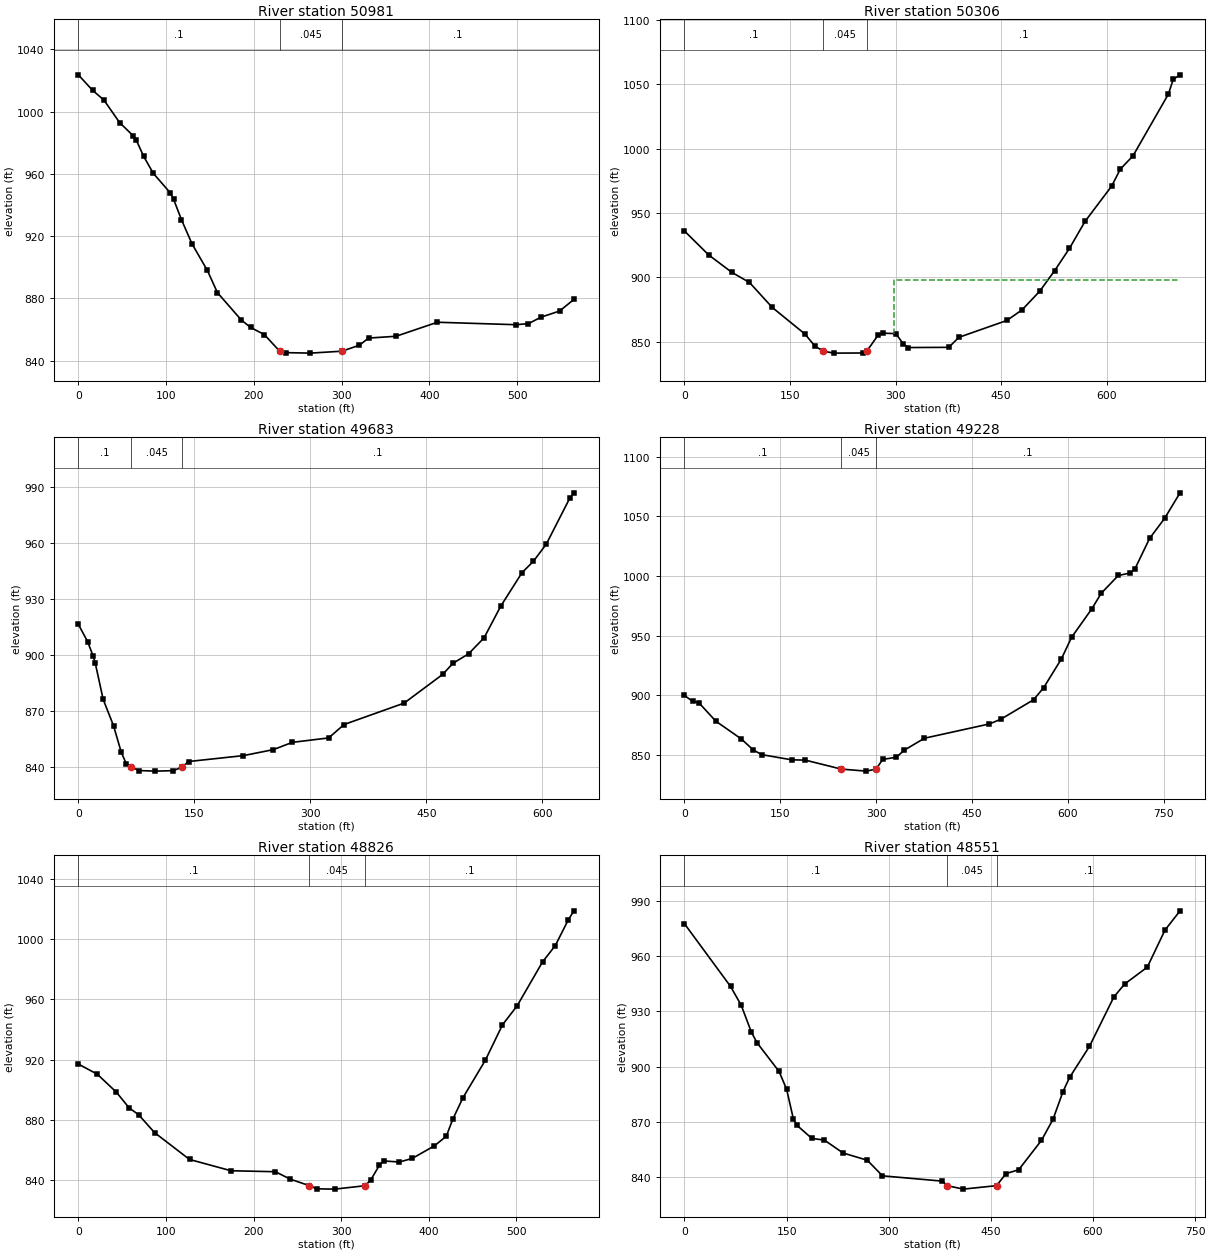
Type RM Length L Ch R = 1 ,50981   ,642.1,675.2,696.7
XS GIS Cut Line= 4
1637144.38689211492418.2885714391637321.32683715492526.667737754
1637441.33080735 492570.57162929 1637629.9843681492700.914330598
#Sta/Elev= 30
       0 1023.71    16.2 1013.78    29.2 1007.47      47  993.03    62.6  984.48
    66.2  981.51    74.5  971.22    85.4  960.39   104.7  947.86   108.5  943.73
   117.5  930.59   129.4  915.18     147  897.93   158.5  883.64   185.5  866.16
   196.2  861.29   211.9  856.69   229.4  846.01   236.3  845.07   264.3  844.75
   300.4845.9994   320.2  849.83   330.7  854.44     362  855.59   409.1  864.61
   498.7  863.02   512.9  863.73     527  867.84   548.3  871.81   564.6  879.26
#Mann= 3 ,-1,0
       0      .1       0   229.4    .045       0   300.4      .1       0
Bank Sta=229.4,300.4
XS Rating Curve= 0 ,0
Exp/Cntr(USF)=0,0
Exp/Cntr=0.3,0.1

Type RM Length L Ch R = 1 ,50306   ,606.8,623.2,620.7
XS GIS Cut Line= 2
1636875.88998313492770.1723165641637159.88603864 493414.71988604
#Sta/Elev= 30
       0  935.97    34.4  917.36    67.3  903.83    92.4  895.95   124.7  876.57
   171.3  855.81   185.6  846.36   197.5 842.565   211.9  841.02   253.8  841.13
   259.1842.5461   275.3   855.1   282.4  856.55   300.4  856.17   311.1  848.13
   318.1  845.36   375.6  845.52     390  853.31   458.1   866.4   479.9  874.72
   504.7  889.03   526.2  905.24   547.1  922.43   569.2  943.39   607.2  970.96
   619.4   984.1   637.4  994.39   687.6 1042.29   694.7 1053.97   704.3 1057.43
#Mann= 3 ,-1,0
       0      .1       0   197.5    .045       0   259.1      .1       0
#XS Ineff= 2 , 0
                          298.02          898.22
Permanent Ineff=
       F       F
Bank Sta=197.5,259.1
XS Rating Curve= 0 ,0
Exp/Cntr(USF)=0,0
Exp/Cntr=0.3,0.1

Type RM Length L Ch R = 1 ,49683   ,433.8,454.9,478.9
XS GIS Cut Line= 2
1636349.87989769492957.8566662961636480.76503632493585.117519349
#Sta/Elev= 30
       0  916.44      12  907.21    19.3  899.29      22  895.52    32.1  876.34
    45.5  862.25    55.5  848.08    62.2  841.73    68.4840.0478      79  838.25
    99.7  837.95   122.6   838.2   133.9840.0516   142.7  843.09   213.4  846.24
   252.2  849.44   276.7  853.33   323.7   855.7   343.7  862.87   421.3  874.31
   471.1  889.64   484.5  895.61   504.6  900.65   524.7  909.22   546.1  926.04
   573.8  944.08   588.4  950.07   605.2  959.35   635.3   983.7   640.8  986.72
#Mann= 3 ,-1,0
       0      .1       0    68.4    .045       0   133.9      .1       0
Bank Sta=68.4,133.9
XS Rating Curve= 0 ,0
Exp/Cntr(USF)=0,0
Exp/Cntr=0.3,0.1

Type RM Length L Ch R = 1 ,49228   ,365.4,402.3,444.6
XS GIS Cut Line= 3
1636137.50023879492935.6308880391636016.49322383492933.161357121
1635648.53311712 493473.98862806
#Sta/Elev= 30
       0  899.83    12.8  894.93    22.6   893.7    48.9  878.37    88.6  863.53
   107.9  854.09     121  850.27   167.7  845.94   188.9   845.7   245.1838.1955
   284.1  836.47   299.7838.1744   310.2  846.31   331.5  848.08   343.6  853.95
   375.4  864.03   476.9     876   494.4   879.8     546  896.24   561.9  906.39
   589.7  930.57   605.5  948.53   637.3  972.51   651.8  985.38   678.6 1000.35
   696.8 1002.38   704.6 1005.85   727.6 1031.43     751 1048.14   775.2  1069.6
#Mann= 3 ,-1,0
       0      .1       0   245.1    .045       0   299.7      .1       0
Bank Sta=245.1,299.7
XS Rating Curve= 0 ,0
Exp/Cntr(USF)=0,0
Exp/Cntr=0.3,0.1

Type RM Length L Ch R = 1 ,48826   ,259.2,275,265.7
XS GIS Cut Line= 2
1636216.52522815492817.0934039971635705.33232822492575.079374079
#Sta/Elev= 30
       0   917.1    21.7  910.34    43.5  898.37      58  887.99    68.9   883.4
      87  871.59   126.9  853.76   174.2  846.26     225   845.6   241.7  840.71
   263.8836.3292   272.2  834.25   292.7  834.05   327.4 836.325   333.9  840.27
   343.7  849.95   348.4  852.76   366.5  852.06   381.1  854.42   406.5  862.83
     420  869.18   427.4  880.48   439.1  894.83   464.6  919.66   484.1  943.12
   500.8  955.71   529.9  984.96   544.4  995.74   558.9 1012.47   565.6 1018.82
#Mann= 3 ,-1,0
       0      .1       0   263.8    .045       0   327.4      .1       0
Bank Sta=263.8,327.4
XS Rating Curve= 0 ,0
Exp/Cntr(USF)=0,0
Exp/Cntr=0.3,0.1

Type RM Length L Ch R = 1 ,48551   ,265.5,286.9,272.1
XS GIS Cut Line= 2
1636441.25254164492659.0434252751635796.70497217492320.717689574
#Sta/Elev= 30
       0  977.43    67.6  943.48    83.3  933.27    98.1  918.79   106.5  912.94
   138.9  897.35     150   887.7   159.9  871.68   164.8  868.25     187  861.05
   205.6  860.08   232.8  853.14   268.5  849.19   290.8  840.73   378.6  837.86
   386.2835.3925   409.3  833.52   458.4835.4031   472.3  841.95   490.9  844.02
   524.4  859.99   541.4  871.45     556  886.45   565.7   894.1   594.9  910.98
   630.7  937.74   646.5  944.74   679.8   953.9   705.8  974.01   727.9  984.45
#Mann= 3 ,-1,0
       0      .1       0   386.2    .045       0   458.4      .1       0
Bank Sta=386.2,458.4
XS Rating Curve= 0 ,0
Exp/Cntr(USF)=0,0
Exp/Cntr=0.3,0.1

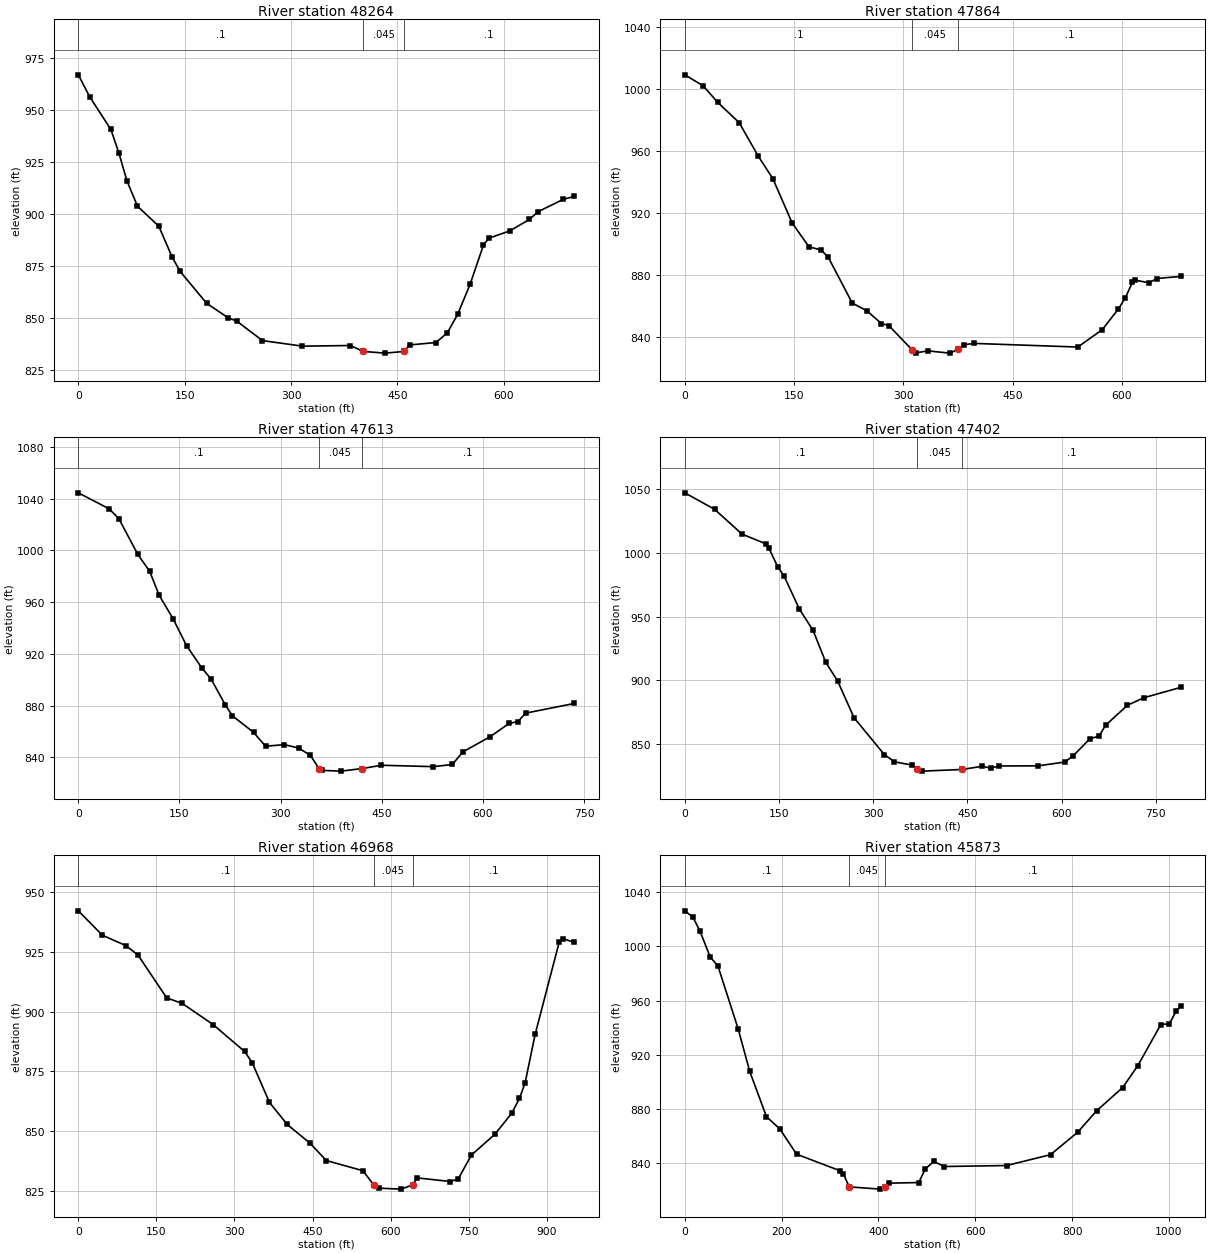
Type RM Length L Ch R = 1 ,48264   ,393,399.7,369.1
XS GIS Cut Line= 2
1636584.84586273492449.1521663841635973.38900578492110.077634272
#Sta/Elev= 30
       0  966.96    15.9  956.45    45.9  940.65    57.2   929.3    68.4  916.04
    83.4  903.72   113.5  894.05   132.2  879.29   143.5  872.34     181  856.92
     211  850.05   223.5  848.35   259.7     839     316  836.33   383.6  836.63
   401.7  833.79   432.3  832.97   459.1  833.76   467.2  836.91   504.2  838.07
   520.3  842.71   534.8  851.58   552.4  866.06   571.1   884.8   578.6  888.27
   608.7  891.86   636.2  897.35   648.2  901.05   683.7  906.98   699.2  908.43
#Mann= 3 ,-1,0
       0      .1       0   401.7    .045       0   459.1      .1       0
Bank Sta=401.7,459.1
XS Rating Curve= 0 ,0
Exp/Cntr(USF)=0,0
Exp/Cntr=0.3,0.1

Type RM Length L Ch R = 1 ,47864   ,259.3,251.2,224.3
XS GIS Cut Line= 3
1636838.77882086492005.5011400371636617.21097589492029.293660303
1636168.12715588491940.071709307
#Sta/Elev= 30
       0 1008.97    25.2  1001.9      45  991.32    74.7  978.12   101.1  956.34
   120.9  942.03   147.3  913.55   170.4  898.14   186.9  896.08   196.8  891.53
   229.9  861.86     250  856.88     270  848.62   280.1  847.37   311.6831.9167
   316.9  829.72   333.6  831.05   363.7  829.59  375.29  831.96   383.8  835.04
   397.3  835.85   539.6  833.51   573.1  844.72   595.4   858.1   604.5  865.04
   614.6  875.24   617.9  876.68   637.3  874.92     648  877.69   680.7  879.03
#Mann= 3 ,-1,0
       0      .1       0   311.6    .045       0  375.29      .1       0
Bank Sta=311.6,375.29
XS Rating Curve= 0 ,0
Exp/Cntr(USF)=0,0
Exp/Cntr=0.3,0.1

Type RM Length L Ch R = 1 ,47613   ,220.9,211.1,196.6
XS GIS Cut Line= 2
1636797.79903006491637.935550367  1636109.971396491897.456331447
#Sta/Elev= 30
       0 1044.52    45.4 1032.22    60.1 1024.56    88.2  996.83   105.7   983.9
   119.8  965.32   140.8  946.85   160.5  926.28   182.9   909.2   196.9  900.42
   217.9   880.5   228.5  872.05   259.8  859.25   277.6  848.52   305.6  849.72
   326.6  847.13   344.2   841.4   356.9831.1594   361.6  829.79   389.8  829.25
   420.2  831.21   449.4  833.79   526.5  832.71   554.6  834.39   570.2  844.15
   610.7  855.88   638.7  866.15   651.9  867.62   663.3  874.11   735.2  881.58
#Mann= 3 ,-1,0
       0      .1       0   356.9    .045       0   420.2      .1       0
Bank Sta=356.9,420.2
XS Rating Curve= 0 ,0
Exp/Cntr(USF)=0,0
Exp/Cntr=0.3,0.1

Type RM Length L Ch R = 1 ,47402   ,448.4,433.7,402.9
XS GIS Cut Line= 2
1636636.34548413491330.435791644  1636041.188533491849.037284325
#Sta/Elev= 30
       0 1047.31    47.6 1034.28    91.1 1014.83   129.2 1007.16   133.8 1003.91
   147.8  989.26   157.9  981.99   182.5  955.81   204.3  939.01   224.5  913.93
   243.4  899.21   269.5  870.34   317.7  841.41   333.8  835.69   361.7  833.13
   369.3829.6967   378.3  828.38   441.7   829.7   473.3  832.17   487.1  830.78
   500.2  832.44   562.4  832.54   604.6  835.48   617.7  840.13   645.4  854.02
   659.4   855.8   669.9  864.45   704.7  880.17   730.8  886.11   789.4  894.23
#Mann= 3 ,-1,0
       0      .1       0   369.3    .045       0   441.7      .1       0
Bank Sta=369.3,441.7
XS Rating Curve= 0 ,0
Exp/Cntr(USF)=0,0
Exp/Cntr=0.3,0.1

Type RM Length L Ch R = 1 ,46968   ,1095,1094.7,992.3
XS GIS Cut Line= 3
1636238.75100641490858.7553863961635996.73697649491300.801420634
1635895.48620887491737.908393036
#Sta/Elev= 30
       0  942.27    46.3  932.03    91.2  927.73   114.5  923.78   169.8   905.8
   199.7  903.49     259  894.62   319.4  883.38   333.9  878.74   367.2  862.04
   401.4  852.79   445.1  844.95   476.5  837.69   546.6  833.44   567.7827.4857
   576.9  826.12   620.5  825.72   642.3827.5074     651  830.42   714.9  828.91
   729.9  830.04   755.3  840.01   800.5  848.74   832.8  857.54   847.5  863.71
   858.4  870.26   877.6   890.5   923.7  929.03   930.5  930.68   952.6  929.04
#Mann= 3 ,-1,0
       0      .1       0   567.7    .045       0   642.3      .1       0
Bank Sta=567.7,642.3
XS Rating Curve= 0 ,0
Exp/Cntr(USF)=0,0
Exp/Cntr=0.3,0.1

Type RM Length L Ch R = 1 ,45873   ,488.1,492,472.1
XS GIS Cut Line= 3
1634934.37660528491531.6073472861635416.62440771491690.915689207
1635889.94458149491896.736273997
#Sta/Elev= 30
       0 1026.19    16.7 1021.52    31.5 1011.17    52.3  992.23    68.5  985.49
     110   939.4   134.1  907.83   168.7  874.46   196.3  865.43   230.9  846.81
   320.7  834.61   327.6   832.3   339.5822.7366   403.7  821.08   412.9822.7106
   421.1  825.48   483.1  825.92   496.9  836.09   514.4  841.47   535.9  837.75
   664.7  838.47   755.4  846.49   811.4     863   850.7  878.89   904.4  895.97
   935.7  912.14     983  942.33    1001  943.04  1015.3  952.67    1024   955.7
#Mann= 3 ,-1,0
       0      .1       0   339.5    .045       0   412.9      .1       0
Bank Sta=339.5,412.9
XS Rating Curve= 0 ,0
Exp/Cntr(USF)=0,0
Exp/Cntr=0.3,0.1

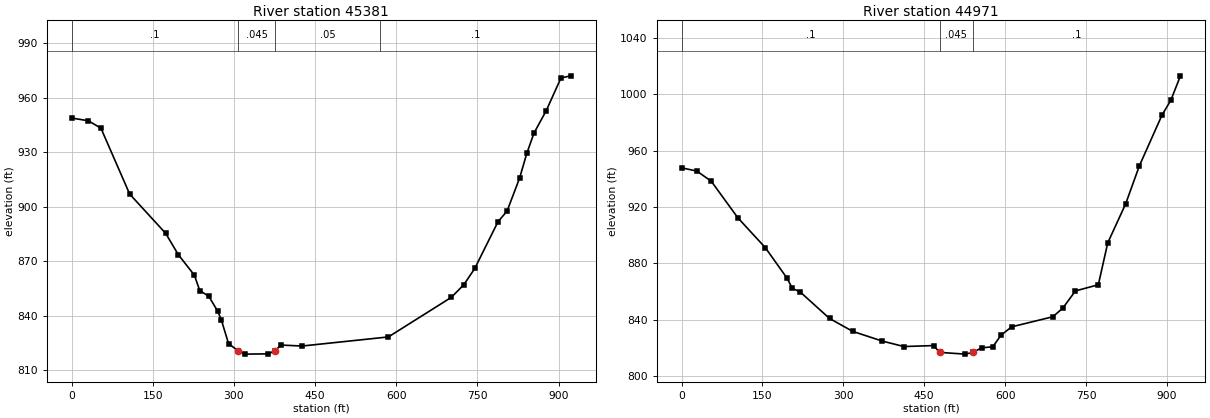
Type RM Length L Ch R = 1 ,45381   ,391.5,409.9,403.8
XS GIS Cut Line= 2
1634896.64436799492066.8595149831635807.62688424492209.543523551
#Sta/Elev= 30
       0  948.86      31  947.34    54.2  943.26   107.3  906.99   173.8  885.39
     197  873.71   226.9  862.34   236.8  853.88   253.5  850.73   270.1  842.44
   276.7  837.72     290   824.7   307.5820.7255   319.9  818.88     363  819.03
   376.5  820.69   386.3  823.88   425.9  823.34   585.5  828.35   701.8  850.15
   724.9  857.12     745  866.02   788.1  891.83   804.7   897.6     828  915.89
   841.2  929.39   854.5  940.58   877.1  952.89   904.3  970.88   922.1  972.09
#Mann= 4 ,-1,0
       0      .1       0   307.5    .045       0   376.5     .05       0
     570      .1       0
Bank Sta=307.5,376.5
XS Rating Curve= 0 ,0
Exp/Cntr(USF)=0,0
Exp/Cntr=0.3,0.1

Type RM Length L Ch R = 1 ,44971   ,645.4,660.8,666.6
XS GIS Cut Line= 4
1634878.95659979492115.3458198551635058.53583925492407.105996954
 1635291.7693148492558.0217752471635520.64482097492759.201592027
#Sta/Elev= 30
       0  947.81    28.4  945.49    55.1   938.3   104.6  912.27   155.5  891.09
   195.8  869.43   205.6  862.19   219.6  859.88   274.4  840.93   317.4  831.77
   372.1   824.9   412.4  821.01   467.6   821.7   478.4816.8729   526.2  815.63
   540.3816.8799   556.6  820.13     577  820.81   592.7  829.19   612.2     835
   688.6  842.15   707.1  848.35   730.4  860.48   772.8  864.84   790.3  894.59
   823.4  922.16     849  949.29   890.9  985.24   907.1  995.59   925.1 1013.05
#Mann= 3 ,-1,0
       0      .1       0   478.4    .045       0   540.3      .1       0
Bank Sta=478.4,540.3
XS Rating Curve= 0 ,0
Exp/Cntr(USF)=0,0
Exp/Cntr=0.3,0.1