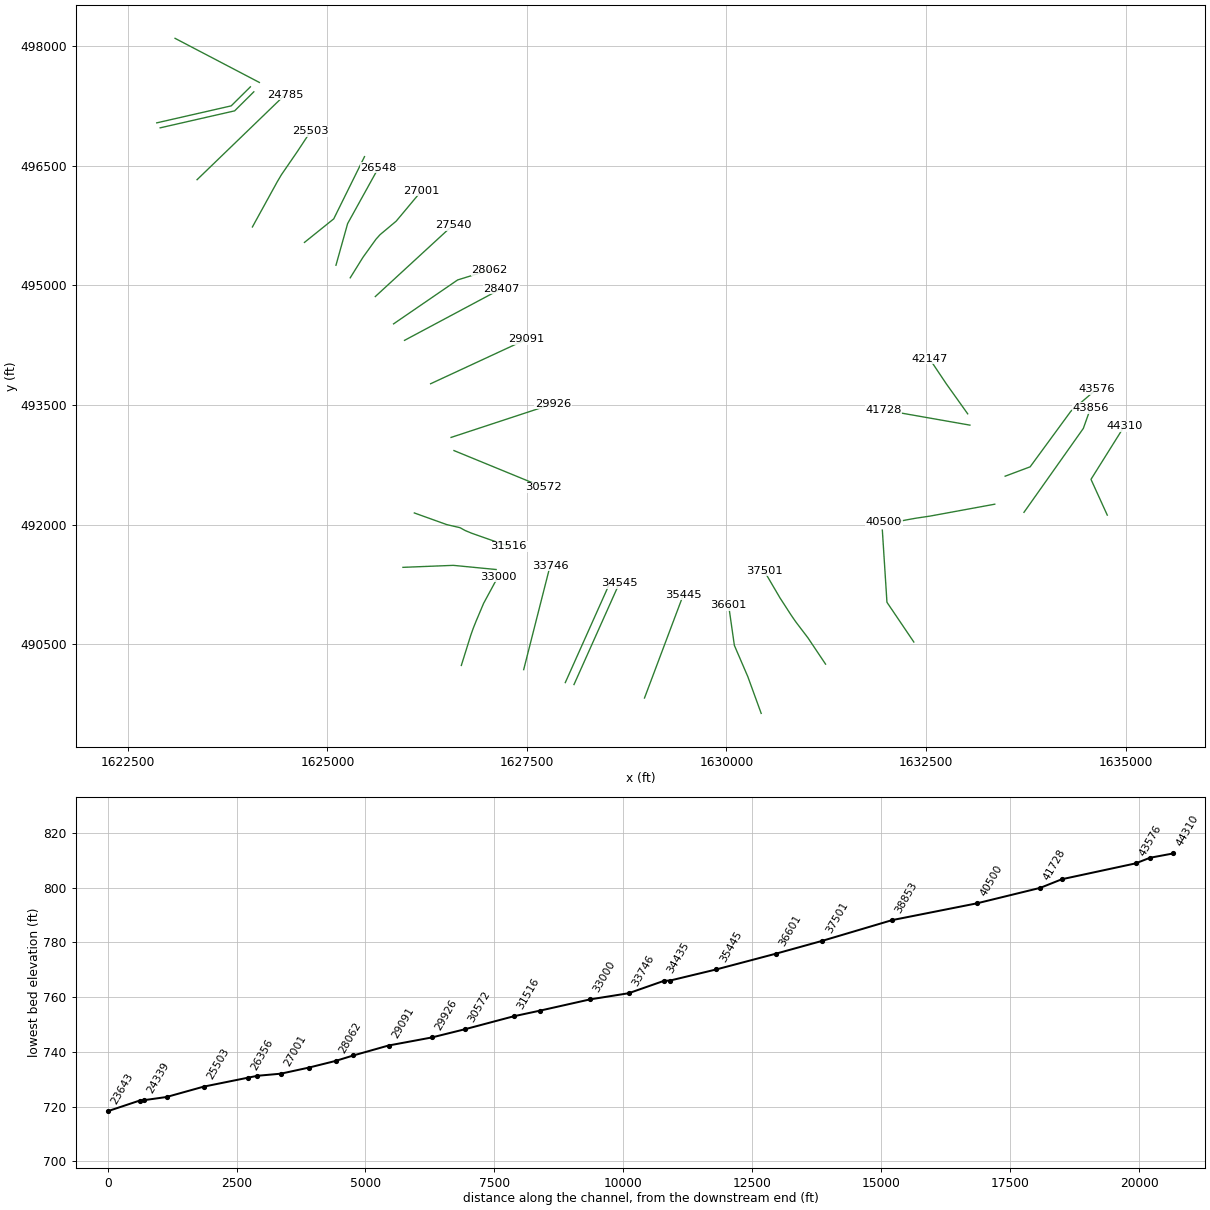
HEC-RAS study GraveCk1.prj: GraveCk1

--- GraveCk1.g01 (geometry) --- (continued)

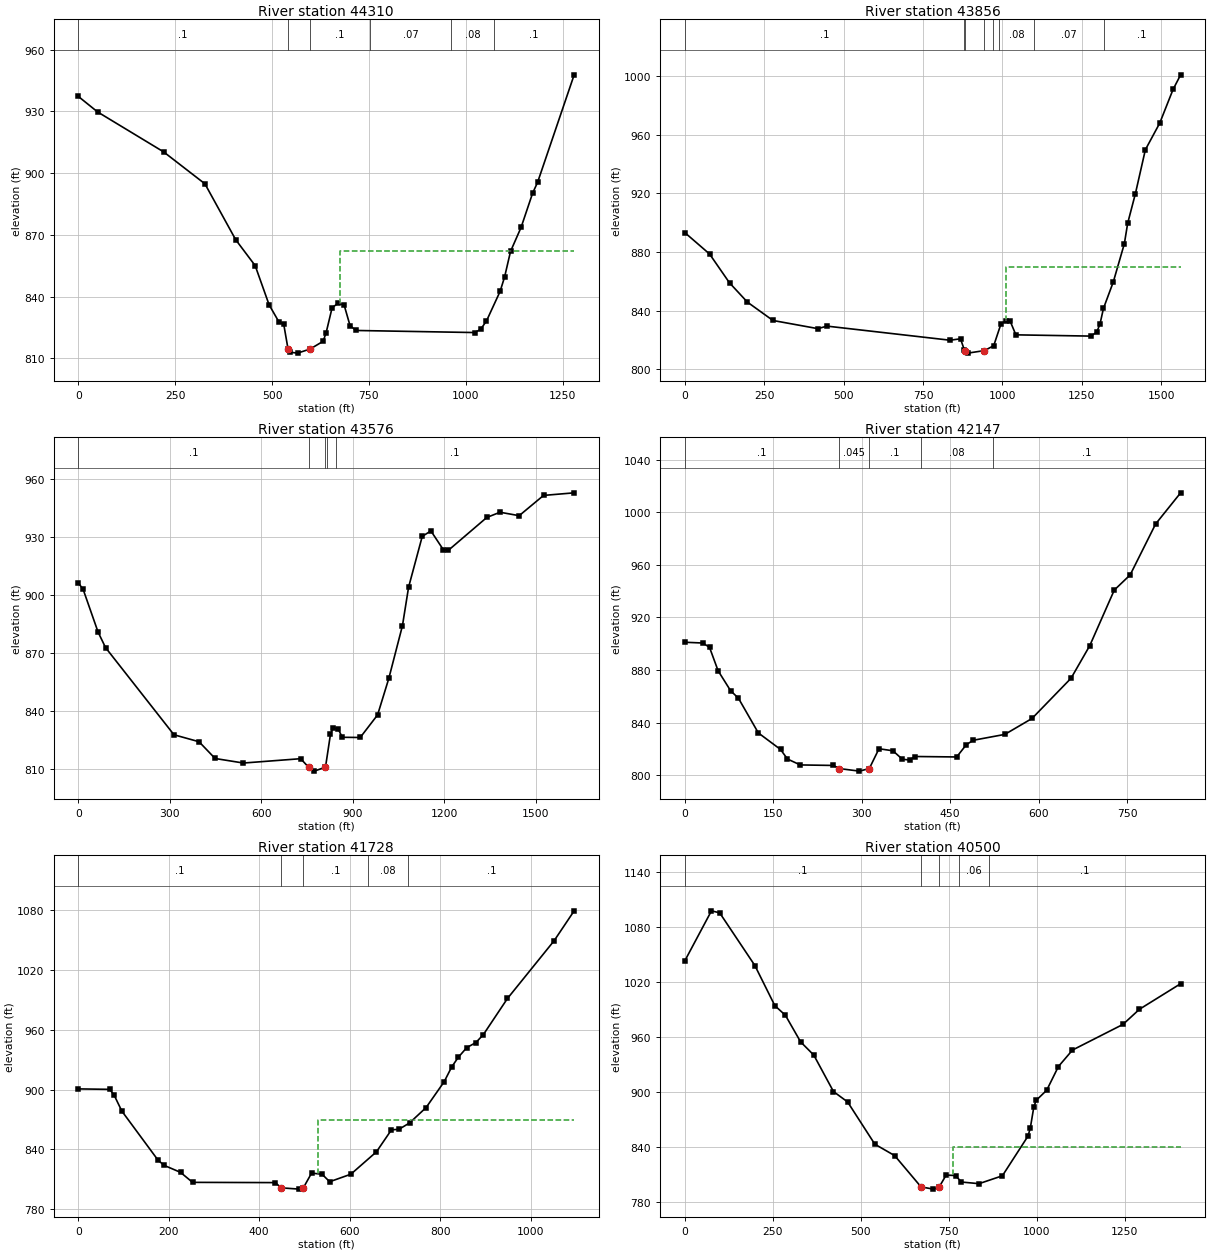
Type RM Length L Ch R = 1 ,44310   ,450.3,454.4,445.8
XS GIS Cut Line= 3
1634770.97602195 492120.975309811634566.99350939492569.233176926
1634985.03174501493236.583372352
#Sta/Elev= 30
       0  937.31    49.6  929.79   220.2  910.36   326.8  894.84   406.3  867.66
   456.5  855.09   492.5  836.03   518.3  827.57   530.2  826.66  541.26 814.664
   546.8     813   565.9  812.56   598.5 814.559     632  818.32   639.7  822.49
   655.2  834.66   670.5  836.78   686.2  835.92   701.5  825.88   717.1  823.57
    1023  822.56  1038.4  824.08  1053.7  828.21  1088.8  842.56  1100.4  849.55
  1115.7  861.97    1143  873.67  1172.8  890.33  1185.6  895.56    1280  947.81
#Mann= 6 ,-1,0
       0      .1       0  541.26    .045       0   598.5      .1       0
  752.49     .07       0  962.49     .08       0 1072.49      .1       0
#XS Ineff= 2 , 0
                          676.65          862.13
Permanent Ineff=
       F       F
Bank Sta=541.26,598.5
XS Rating Curve= 0 ,0
Exp/Cntr(USF)=0,0
Exp/Cntr=0.3,0.1

Type RM Length L Ch R = 1 ,43856   ,274.2,279.6,271
XS GIS Cut Line= 3
1633727.42932283492155.8130041311634471.33626553 493208.33158353
1634562.50965994493464.502050553
#Sta/Elev= 30
       0  893.24    77.9  878.64   140.8  858.92     197   845.8   277.4  833.26
     419  827.67   447.4  829.41     835  819.78   867.9  820.75     880  813.11
  880.94812.7273   890.8  810.97   943.3  812.71   972.4  816.03   995.1  830.81
  1010.1  833.09  1024.6  832.57  1042.2  823.45  1277.7  822.59  1296.6  825.24
  1307.1  830.95  1317.8  841.43  1348.9  859.58  1383.7  885.68  1394.1  899.59
  1418.5  919.87  1449.8  949.78  1495.1  967.99  1536.9   990.9  1560.8 1000.91
#Mann= 8 ,-1,0
       0      .1       0     880     .06       0  880.94    .045       0
   943.3     .06       0     970      .1       0     990     .08       0
    1100     .07       0 1318.87      .1       0
#XS Ineff= 2 , 0
                          1012.1          869.48
Permanent Ineff=
       F       F
Bank Sta=880.94,943.3
XS Rating Curve= 0 ,0
Exp/Cntr(USF)=0,0
Exp/Cntr=0.3,0.1

Type RM Length L Ch R = 1 ,43576   ,1385.4,1429.3,1449.3
XS GIS Cut Line= 4
1633491.99439306492609.0243415761633804.82541282492726.476909118
1634315.10565222493423.6162162781634639.18311304493702.157624307
#Sta/Elev= 30
       0  906.38    15.7  903.06    64.7  880.92    89.3  872.86   313.5  827.74
   395.7  824.13   448.4  815.45   541.2   813.1   728.9  815.35  754.58  810.97
   773.6  808.91   810.2  810.96   826.5  827.95   834.6  831.12   851.1  830.98
   865.2  826.43   924.1  826.33     981  838.02  1017.8  856.92  1062.5  884.23
  1082.6  904.14  1127.4  930.48  1155.8  933.31  1196.2  923.64  1212.5  923.19
    1339  940.27  1382.3  942.98  1445.1  941.19  1525.1  951.69  1625.4  953.03
#Mann= 5 ,-1,0
       0      .1       0  754.58    .045       0   810.2      .1       0
  814.15     .06       0  844.15      .1       0
Bank Sta=754.58,810.2
XS Rating Curve= 0 ,0
Exp/Cntr(USF)=0,0
Exp/Cntr=0.3,0.1

Type RM Length L Ch R = 1 ,42147   ,390.7,418.8,429.6
XS GIS Cut Line= 3
1633022.43536642493390.8515155811632754.03104869493767.401296234
1632543.70953811    494081.99189
#Sta/Elev= 30
       0  901.11    30.6  900.53    41.9  897.26    56.5  879.41    77.6  864.32
      91  858.52   124.7  832.17   162.3  819.61   174.1  812.33   195.8  807.83
   251.7  807.44  262.07805.0469   296.2  803.12   312.9  805.09   329.3  820.14
   352.9  818.59     369  812.14   381.1   811.6   390.5  814.24     461  813.89
   477.6  823.31   489.3   826.6   542.7  831.05   588.8  843.16     655  873.76
   686.7   898.5   728.3  940.79   755.2  952.31   798.4  991.04   840.8 1014.73
#Mann= 5 ,-1,0
       0      .1       0  262.07    .045       0   312.9      .1       0
     400     .08       0  522.42      .1       0
Bank Sta=262.07,312.9
XS Rating Curve= 0 ,0
Exp/Cntr(USF)=0,0
Exp/Cntr=0.3,0.1

Type RM Length L Ch R = 1 ,41728   ,1211.9,1228.3,1231.1
XS GIS Cut Line= 2
1633050.10317661493249.1115719341631970.30561507493439.228809608
#Sta/Elev= 30
       0  900.66    69.4  900.21    79.4  894.18    96.1  878.44     176  829.22
   189.4   823.9     226  816.82   252.6  806.77   435.2  806.52   449.2  801.22
     489  799.97   497.5 801.195   515.8  816.09   539.1  814.89   555.8   807.4
   602.6  814.96   659.1  837.41   692.4  859.54     709  860.07   732.4  866.46
     769  881.92     809  907.91   825.6  922.71   840.2  932.43   858.9  942.14
   878.9  947.15   895.6  955.19   948.9  991.49  1052.2 1049.58  1096.4 1079.56
#Mann= 5 ,-1,0
       0      .1       0   449.2    .045       0   497.5      .1       0
     640     .08       0     730      .1       0
#XS Ineff= 2 , 0
                          529.11          869.04
Permanent Ineff=
       F       F
Bank Sta=449.2,497.5
XS Rating Curve= 0 ,0
Exp/Cntr(USF)=0,0
Exp/Cntr=0.3,0.1

Type RM Length L Ch R = 1 ,40500   ,1704.4,1646.8,1609.9
XS GIS Cut Line= 6
1633361.37783025 492257.800230921632549.59730159492108.526907429
1632370.14720118492081.7352943421632274.34555551492064.406260759
1632078.92009334492027.6238540111631972.86092226   492036.391553
#Sta/Elev= 30
       0 1043.19    75.8 1097.76    99.1 1095.58   199.2 1038.13   255.9  994.41
     286  983.86   329.3  954.85   366.7  940.46   422.7  900.69   462.8  889.39
   540.2  843.31   596.6  830.85  671.47796.7859   706.3  794.31   723.3  796.76
     743  809.65   769.7   809.1   786.3  802.05   836.4  800.26   902.8  808.86
   975.6  852.09   982.3  861.15   992.2  883.98   998.8  891.09  1028.8  902.14
  1062.1  928.01  1102.1  945.96  1245.7  973.94  1292.4  990.41  1409.5 1018.29
#Mann= 5 ,-1,0
       0      .1       0  671.47    .045       0   723.3      .1       0
  780.39     .06       0  865.39      .1       0
#XS Ineff= 2 , 0
                          762.46          840.61
Permanent Ineff=
       F       F
Bank Sta=671.47,723.3
XS Rating Curve= 0 ,0
Exp/Cntr(USF)=0,0
Exp/Cntr=0.3,0.1

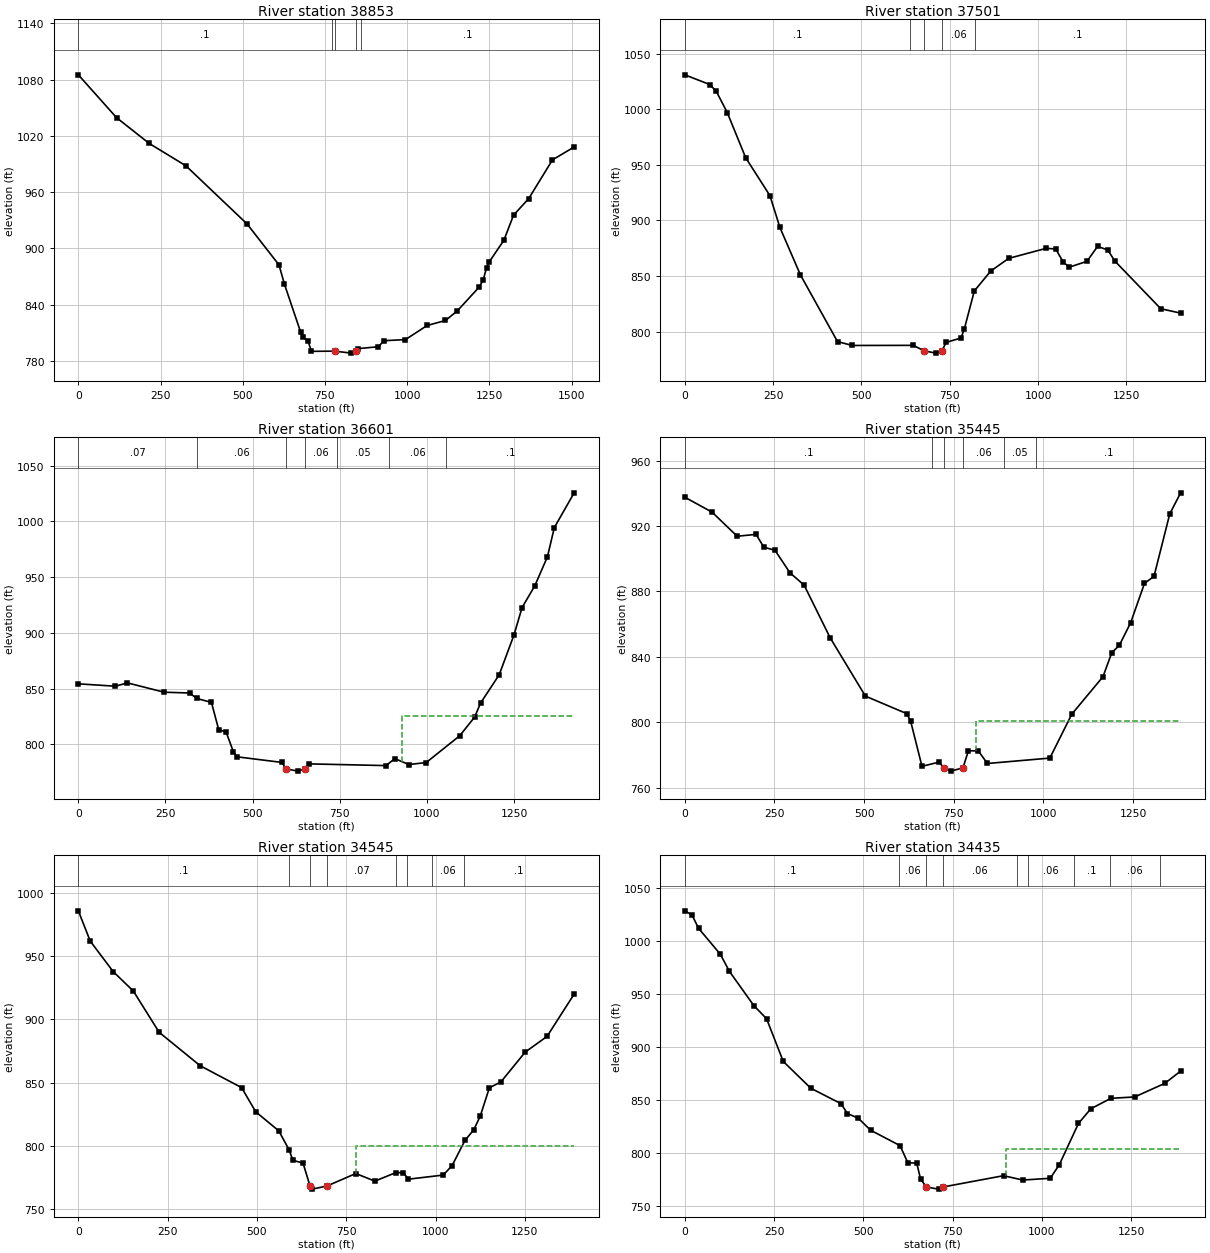
Type RM Length L Ch R = 1 ,38853   ,1298.8,1351.9,1339.8
XS GIS Cut Line= 3
1632347.19115787490529.9860545471632010.62344098491027.983862809
1631952.82496692491932.932446513
#Sta/Elev= 30
       0    1085   116.2 1039.33   215.5 1011.84   327.1  987.98   513.2  925.94
   610.3  882.22   626.7  861.86     676  810.65   682.6   805.5   698.7     801
   708.9  790.07  779.81790.2772   830.5  788.16  843.48 790.214   850.3  792.97
   912.7  794.97   929.2  801.39   994.9  802.61  1060.9  817.66  1116.6  822.97
  1152.7  833.28    1219  858.56  1231.6  866.47  1241.5  879.38  1249.4  885.36
  1294.1   908.5  1323.6  935.35  1369.7     953    1442  994.33  1507.9 1008.01
#Mann= 5 ,-1,0
       0      .1       0  771.07     .06       0  779.81    .045       0
  843.48     .06       0  861.07      .1       0
Bank Sta=779.81,843.48
XS Rating Curve= 0 ,0
Exp/Cntr(USF)=0,0
Exp/Cntr=0.3,0.1

Type RM Length L Ch R = 1 ,37501   ,893.2,899.9,885.5
XS GIS Cut Line= 6
1631241.31350084490252.5001076761631021.39202468490581.157258749
1630865.89003909490785.7063903361630809.37112325490868.243954927
1630670.16372451491083.3839445861630470.47842833491424.198879749
#Sta/Elev= 30
       0 1030.88    71.1 1022.12    89.4 1015.89   120.2  996.95   172.3  956.38
     241  922.24   269.3  893.58   327.4  850.91   432.4  790.93   474.5  787.49
   646.9  787.59   677.8782.6427   710.7   780.6   727.9782.6717     740  790.31
   781.8  794.15   791.3   802.3   819.7  836.55   866.4  854.49     917  865.81
  1023.7   874.9  1050.2  874.19  1071.7   862.3  1088.9  857.95  1138.4  863.14
  1168.8  876.63  1197.6  873.32  1217.2  863.48  1347.5  820.53  1403.7  816.57
#Mann= 5 ,-1,0
       0      .1       0  637.22     .06       0   677.8    .045       0
   727.9     .06       0  822.47      .1       0
Bank Sta=677.8,727.9
XS Rating Curve= 0 ,0
Exp/Cntr(USF)=0,0
Exp/Cntr=0.3,0.1

Type RM Length L Ch R = 1 ,36601   ,1170.4,1156.2,1127.6
XS GIS Cut Line= 4
  1630434.827395489635.0128709561630266.89929261490096.815152534
1630098.97119022490487.0010375041630027.35479361490988.315813762
#Sta/Elev= 30
       0  854.23   106.1   852.1     141  855.07     246  846.73     319  846.01
     340  841.08   381.9  837.58   402.8  813.02   423.8  811.19   444.7  793.38
   455.2  788.75   584.1  783.71   595.4778.0786   629.1   775.9   650.6778.0527
   661.6  782.41   882.9  780.86     908  787.15   948.3  781.81     998  783.59
  1094.1  807.59  1137.2  824.44    1154  836.95  1207.6  862.43  1249.9  898.06
  1273.1  922.67  1309.6  942.14    1346   968.3  1365.7  994.44  1422.6 1025.63
#Mann= 7 ,-1,0
       0     .07       0     340     .06       0   595.4    .045       0
   650.6     .06       0  741.39     .05       0  891.39     .06       0
 1056.18      .1       0
#XS Ineff= 2 , 0
                          927.98             825
Permanent Ineff=
       F       F
Bank Sta=595.4,650.6
XS Rating Curve= 0 ,0
Exp/Cntr(USF)=0,0
Exp/Cntr=0.3,0.1

Type RM Length L Ch R = 1 ,35445   ,900.1,899.9,898.4
XS GIS Cut Line= 2
1628972.86509182489827.6362825231629459.36268258491121.670483309
#Sta/Elev= 30
       0  937.59      76  928.47   146.1  913.73   198.6  914.88   220.6     907
   251.4  905.19   293.3  891.35   332.7  883.86   405.4  851.61   503.6  815.99
   619.2  805.25   629.8   800.6   661.3  773.09   707.8  775.57   724.1772.1467
   741.9  770.14   775.4772.1421     791  782.63   818.7  782.46   843.6  774.81
  1017.9  778.11    1079  804.95    1166  827.87  1190.6  842.58  1211.5     847
  1243.1  860.84  1281.7  884.91  1308.3  889.25  1352.2   927.4  1382.5  940.28
#Mann= 6 ,-1,0
       0      .1       0     690     .06       0   724.1    .045       0
   775.4     .06       0     890     .05       0     980      .1       0
#XS Ineff= 2 , 0
                          812.78          800.61
Permanent Ineff=
       F       F
Bank Sta=724.1,775.4
XS Rating Curve= 0 ,0
Exp/Cntr(USF)=0,0
Exp/Cntr=0.3,0.1

Type RM Length L Ch R = 1 ,34545   ,109.8,110.1,109.7
XS GIS Cut Line= 2
1628089.56416509489996.5562390481628655.97399264491263.911422393
#Sta/Elev= 30
       0  985.64    33.4  961.72    97.7  937.65     154  922.37   226.3  889.79
   341.1  863.43   457.1  846.15   496.6   827.1   561.3  812.02     590  797.11
   600.8  788.79   629.2  786.57   648.7 768.526   654.7  766.06   696.1768.5282
   776.9  778.37   830.3  772.36   888.3  779.04   909.8  779.07   924.2  773.91
  1021.6  777.15  1046.5  784.63  1082.3  804.44  1107.5  813.01  1125.5  823.85
  1150.7  845.95  1183.2   850.7  1251.2  874.19  1312.2  886.53  1388.2  919.96
#Mann= 8 ,-1,0
       0      .1       0     590     .07       0   648.7    .045       0
   696.1     .07       0     890     .06       0     920     .07       0
     990     .06       0    1080      .1       0
#XS Ineff= 2 , 0
                          778.75          799.81
Permanent Ineff=
       F       F
Bank Sta=648.7,696.1
XS Rating Curve= 0 ,0
Exp/Cntr(USF)=0,0
Exp/Cntr=0.3,0.1

Type RM Length L Ch R = 1 ,34435   ,683.2,689.2,691.4
XS GIS Cut Line= 2
1627980.49817209490021.0471585091628546.90799964491288.402341854
#Sta/Elev= 30
       0 1028.45    20.2  1024.5    38.5 1011.96    99.6  987.48   124.5  971.58
   193.1  939.14     229  926.65   275.7  886.39     353  861.11   437.4  846.57
   455.4  837.24   485.6  832.93   520.1  821.57   602.7  807.02   624.3   790.9
   649.4   790.5   660.2  775.38   676.7767.9507   710.5     766   721.9767.9424
   892.3  778.67   946.5  774.57  1023.2  776.22  1048.4  788.92  1102.2  827.97
  1136.9  841.84  1193.2  851.64  1259.5  852.92  1343.9  865.75  1388.2   877.3
#Mann= 9 ,-1,0
       0      .1       0     600     .06       0   676.7    .045       0
   721.9     .06       0     930     .07       0     960     .06       0
    1090      .1       0    1190     .06       0    1330      .1       0
#XS Ineff= 2 , 0
                          900.62          803.68
Permanent Ineff=
       F       F
Bank Sta=676.7,721.9
XS Rating Curve= 0 ,0
Exp/Cntr(USF)=0,0
Exp/Cntr=0.3,0.1

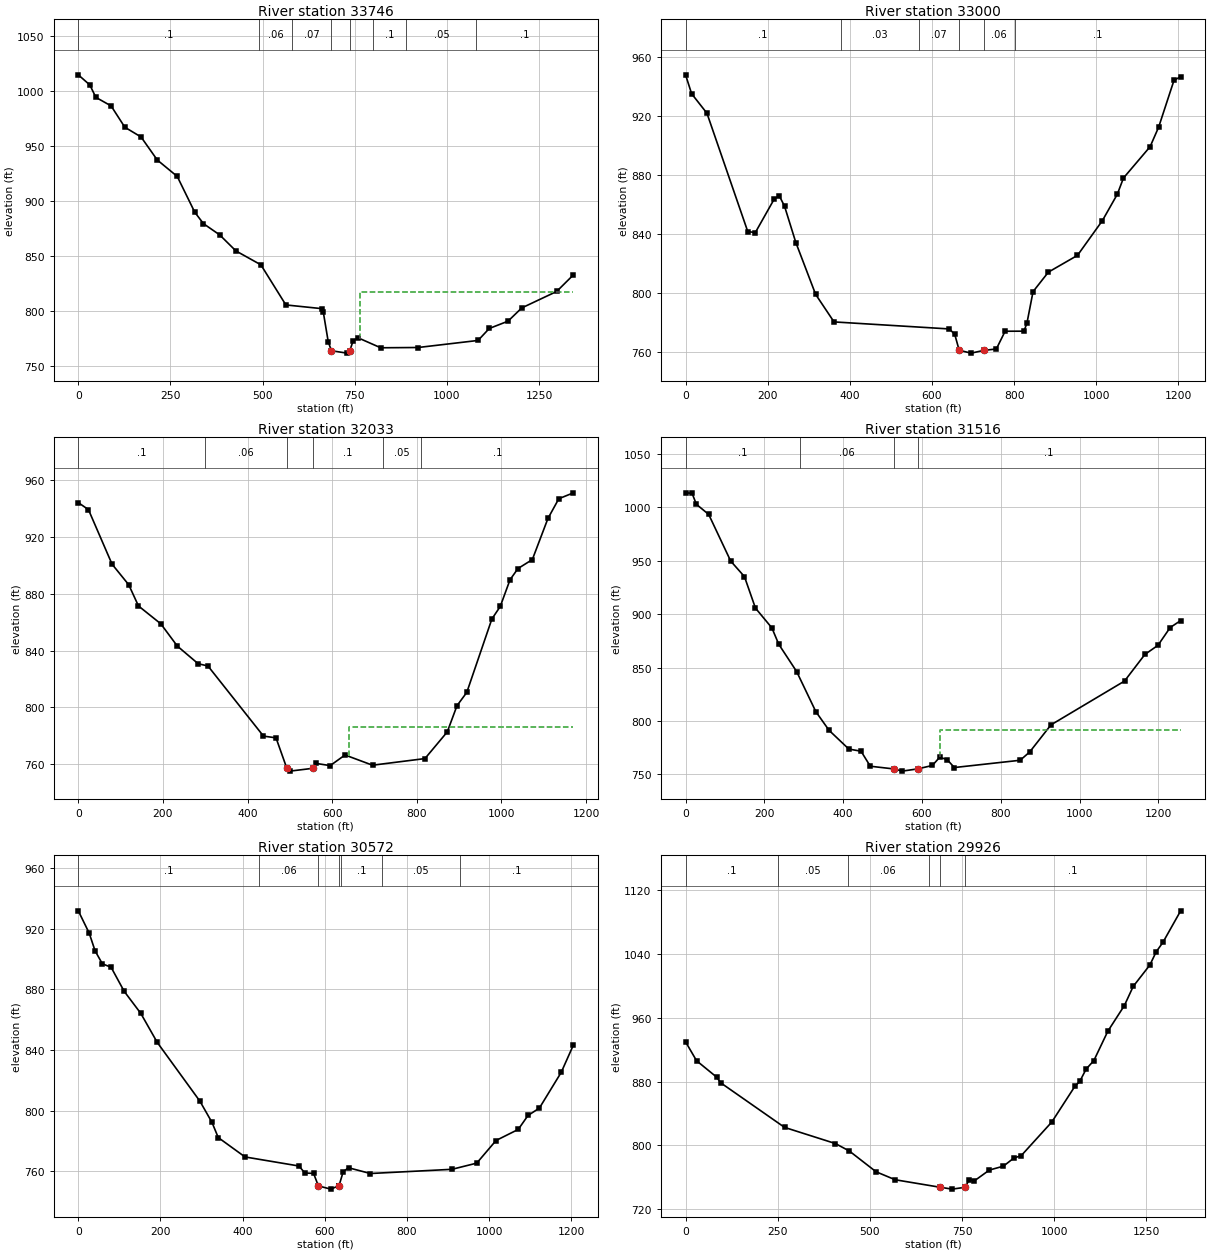
Type RM Length L Ch R = 1 ,33746   ,750.9,746,738.8
XS GIS Cut Line= 2
1627459.04263938490183.2487346471627789.95978233491484.691528186
#Sta/Elev= 30
       0 1014.74    31.4 1005.48    47.5  994.27      89  986.44   126.2  967.05
   170.2  958.18   214.2  937.23   268.4  922.25   315.8  889.74   339.5  879.27
   383.5  869.06   427.5  854.47   495.2  841.83     563   805.3   661.1  801.91
   664.5  798.83     678  771.61   686.7763.5897   728.8  761.44   736.3763.5822
   745.7  772.91   759.2  775.33   820.2  766.31   921.7  766.56  1084.2  772.98
  1114.7  783.88  1165.5  790.51  1202.7  802.56  1297.5  817.57  1342.9  832.68
#Mann= 8 ,-1,0
       0      .1       0     490     .06       0     580     .07       0
   686.7    .045       0   736.3     .06       0     800      .1       0
     890     .05       0    1080      .1       0
#XS Ineff= 2 , 0
                           764.5          817.39
Permanent Ineff=
       F       F
Bank Sta=686.7,736.3
XS Rating Curve= 0 ,0
Exp/Cntr(USF)=0,0
Exp/Cntr=0.3,0.1

Type RM Length L Ch R = 1 ,33000   ,993.8,967.3,925.9
XS GIS Cut Line= 6
1626677.89185342490236.0099831671626795.67212968490613.068612263
1626826.99227701490701.6051805911626859.39050618490782.917353928
1626956.39621767491013.335200176 1627136.6040317491346.733565906
#Sta/Elev= 30
       0  947.85    14.8  935.03    52.1  921.81   151.5  841.59   169.9  840.93
   216.4  863.89   228.5  865.69     241   858.8   268.5  834.19   316.7  799.04
   361.5  780.36   642.5  775.59   655.5  771.84  666.28761.1082   695.4   759.2
  725.95761.0368   756.7  762.02   778.1  774.04   823.9  774.08   831.2   779.5
   846.1  800.88   883.4   814.1   954.3  825.48  1014.9  849.01  1051.3  866.92
  1066.2  877.89  1131.1  899.14    1152  912.47  1189.2  944.07  1205.5  946.64
#Mann= 6 ,-1,0
       0      .1       0     378     .03       0  568.95     .07       0
  666.28    .045       0  725.95     .06       0  801.48      .1       0
Bank Sta=666.28,725.95
XS Rating Curve= 0 ,0
Exp/Cntr(USF)=0,0
Exp/Cntr=0.3,0.1

Type RM Length L Ch R = 1 ,32033   ,523,516.8,505.2
XS GIS Cut Line= 3
1625946.67320809491466.0391399791626576.75252468491490.970335959
1627113.90647443491438.841471637
#Sta/Elev= 30
       0  944.26      24  939.32    79.8  900.88   119.2   886.4   142.2  871.47
     195  858.88   234.1  843.18   283.4  830.74   306.4  829.19   437.7  779.77
   467.3  778.55  492.75757.1846   500.1   755.1  554.64757.0869   562.5  760.52
   595.3  758.97   630.4  766.48   695.4  759.27   819.3  763.94   872.1  782.75
   895.1  801.23   918.2  810.57   977.5  862.29   997.3  871.11  1020.4  889.92
  1039.2  897.83  1073.1  904.13    1110   933.1  1135.7  947.01  1170.2  951.16
#Mann= 6 ,-1,0
       0      .1       0     300     .06       0  492.75    .045       0
  554.64      .1       0  720.57     .05       0  810.57      .1       0
#XS Ineff= 2 , 0
                          639.68          786.17
Permanent Ineff=
       F       F
Bank Sta=492.75,554.64
XS Rating Curve= 0 ,0
Exp/Cntr(USF)=0,0
Exp/Cntr=0.3,0.1

Type RM Length L Ch R = 1 ,31516   ,937.9,943.6,924.2
XS GIS Cut Line= 6
1626089.17149949492147.8835410181626497.08696705492001.331338269
  1626660.772137491963.5685359241626726.53709733491927.431141004
1626808.07925709491893.4797653411627272.04880159491730.306207165
#Sta/Elev= 30
       0 1013.71    16.5 1013.33    27.5 1002.97    58.8  993.45   114.6  949.77
   149.5  935.23   177.4  905.73   219.1   887.2   236.6  871.82   281.9  846.33
   330.7  808.72   364.3   791.2   414.4  773.69   445.4  771.66   468.9   757.6
   530.3  754.99   549.7  753.01   588.8755.0838   626.3   758.3     645  765.99
   663.8  763.85   682.2  756.37   849.3  763.19   873.6  771.02   927.4  796.34
  1114.1  837.37  1165.8  862.31    1199  870.87  1229.9  887.49  1256.6  894.05
#Mann= 4 ,-1,0
       0      .1       0     290     .06       0   530.3    .045       0
   588.8      .1       0
#XS Ineff= 2 , 0
                          646.58           791.5
Permanent Ineff=
       F       F
Bank Sta=530.3,588.8
XS Rating Curve= 0 ,0
Exp/Cntr(USF)=0,0
Exp/Cntr=0.3,0.1

Type RM Length L Ch R = 1 ,30572   ,618,645.9,663.2
XS GIS Cut Line= 2
1626585.81841412492930.1802857151627700.92281614492472.352868627
#Sta/Elev= 30
       0  931.85    26.6  917.09    40.8   905.5    58.5  896.91    79.8  894.64
   111.7  878.76   152.1  864.22   192.3  845.02   296.1  806.28   325.6  792.23
   340.7   782.3   405.9  769.51   537.3  763.53   551.5  758.91   572.8  758.66
   584.5   750.4   614.7  748.28   634.8  750.52   634.8  750.53   644.9  759.77
   657.9  762.38   711.1  758.58   909.7  761.35     970  765.42    1017  780.35
  1071.1  787.67  1094.9  796.87  1122.6  801.75  1175.7   825.3  1205.4  843.36
#Mann= 7 ,-1,0
       0      .1       0     440     .06       0   584.5    .045       0
   634.8     .06       0     640      .1       0     740     .05       0
     930      .1       0
Bank Sta=584.5,634.8
XS Rating Curve= 0 ,0
Exp/Cntr(USF)=0,0
Exp/Cntr=0.3,0.1

Type RM Length L Ch R = 1 ,29926   ,825.1,835.8,835
XS GIS Cut Line= 2
 1626549.2252646493094.9978353321627824.95653904493515.221415186
#Sta/Elev= 30
       0  929.89    29.9  906.15    84.2  885.67    95.5  878.45   268.7  822.61
   406.6  802.37   444.4     793   516.9     767   568.7  757.01   689.4747.7004
   723.4  745.26   759.4747.6328   769.1  757.29   782.9  755.42   824.3  769.17
   862.3  774.03   890.5  784.17   910.7  787.24   993.7  829.42    1056  873.91
  1069.6  880.37  1086.9  895.81  1107.6  906.26  1145.6  943.13  1190.5  975.31
  1214.5  999.32  1259.6 1026.06  1276.8 1042.64  1295.1 1054.51  1343.2 1094.01
#Mann= 6 ,-1,0
       0      .1       0     250     .05       0     440     .06       0
     660      .1       0   689.4    .045       0   759.4      .1       0
Bank Sta=689.4,759.4
XS Rating Curve= 0 ,0
Exp/Cntr(USF)=0,0
Exp/Cntr=0.3,0.1

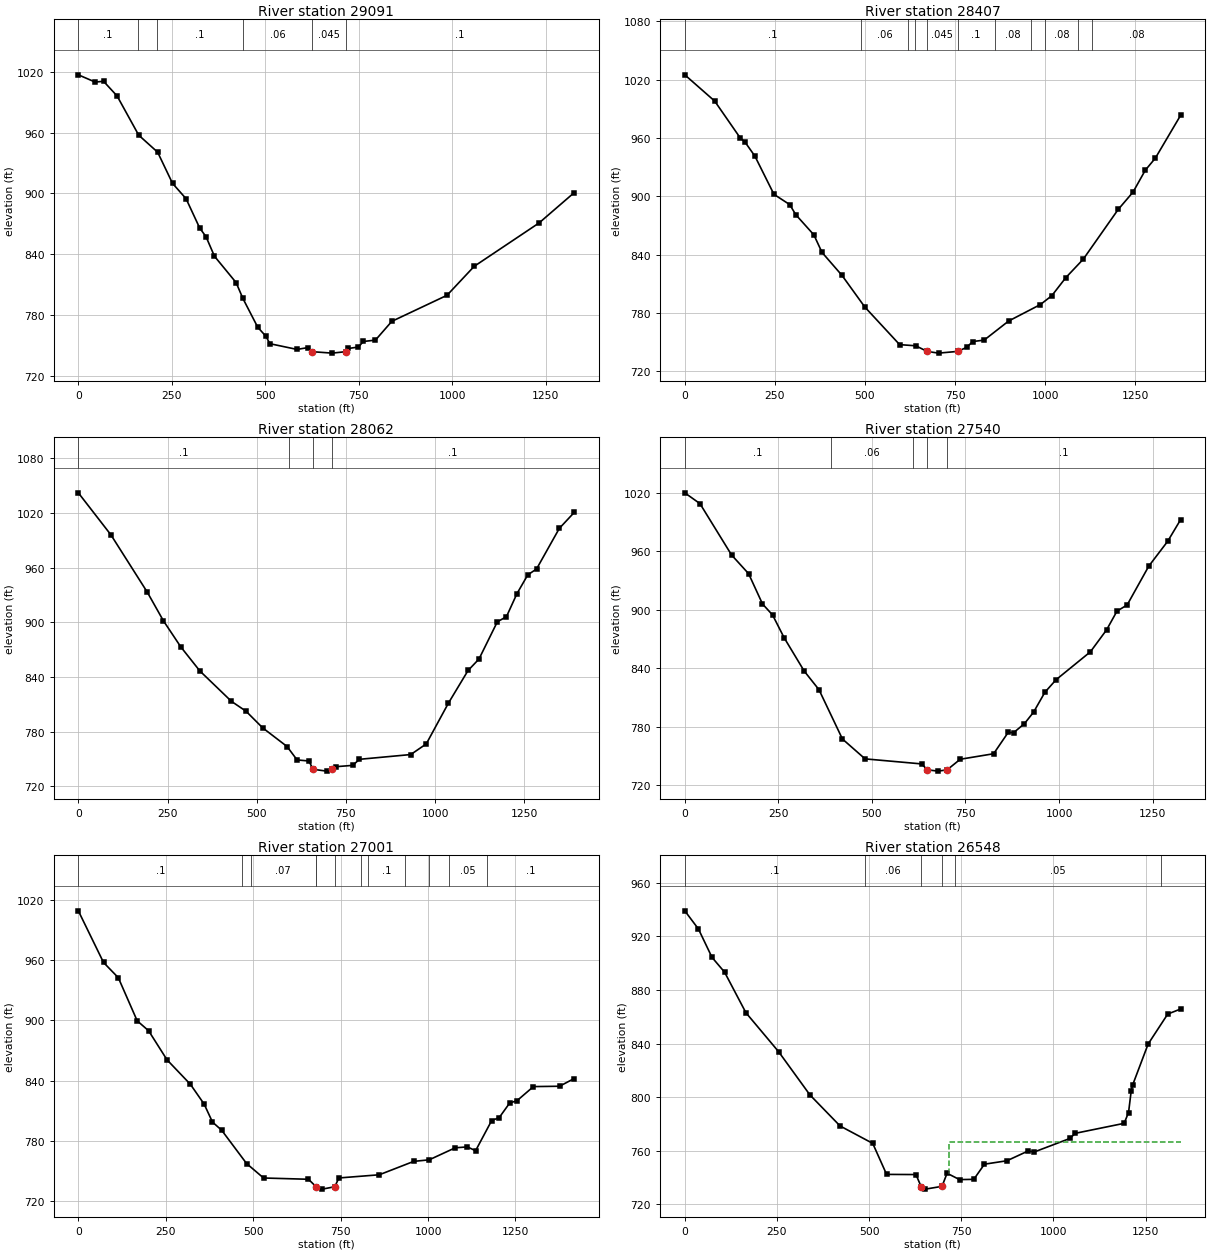
Type RM Length L Ch R = 1 ,29091   ,677.8,683.5,682.7
XS GIS Cut Line= 2
1626293.31428938 493768.236584471627495.97584621494326.350571832
#Sta/Elev= 30
       0 1017.08      45 1009.94    67.5 1010.69   103.6  996.23   161.5  957.49
   212.1   940.7   251.9  909.92   288.1  894.77   324.5  865.87   341.5  857.24
     364     838   421.9  811.97     440  796.35   479.8  767.86   501.5  759.01
   512.3  751.64   584.7  745.99   613.6  747.77   624.2743.7908   678.7  742.33
     715743.7636   722.1  746.92   749.1  748.35   761.9  753.81   794.5  755.18
   838.3  773.71   985.9  799.43  1058.5  827.99  1232.1  870.85  1325.9  900.74
#Mann= 6 ,-1,0
       0      .1       0     160     .05       0     210      .1       0
     440     .06       0   624.2    .045       0     715      .1       0
Bank Sta=624.2,715
XS Rating Curve= 0 ,0
Exp/Cntr(USF)=0,0
Exp/Cntr=0.3,0.1

Type RM Length L Ch R = 1 ,28407   ,334.6,345.5,348.3
XS GIS Cut Line= 2
1625966.38212159494312.2944815011627180.07407147494960.503685812
#Sta/Elev= 30
       0 1025.09      83  998.05   153.6  960.26   167.4  955.71   194.5  941.45
   247.4  902.11   291.2  891.53     308  881.14   358.2  860.39   380.7  842.37
   436.3  818.65   499.5  786.16   596.2  747.42   640.9  746.25   672.6740.4335
   704.1  738.69   756.8740.4514   782.2   744.6     799  750.63   830.6  752.05
   898.6  771.72   986.9  788.71  1018.4  797.79  1057.4  816.42  1105.7  835.35
  1202.6  886.53  1243.9  904.43  1277.8  926.89  1305.8  939.38  1375.9  983.44
#Mann= 11 ,-1,0
       0      .1       0     490     .06       0     620     .07       0
     640     .06       0   672.6    .045       0   756.8      .1       0
     860     .08       0     960      .1       0    1000     .08       0
    1090      .1       0    1130     .08       0
Bank Sta=672.6,756.8
XS Rating Curve= 0 ,0
Exp/Cntr(USF)=0,0
Exp/Cntr=0.3,0.1

Type RM Length L Ch R = 1 ,28062   ,513.5,521.9,522.4
XS GIS Cut Line= 3
1625829.04247688494518.9739833991626631.64002508495069.679378009
 1627029.2345028495193.155923885
#Sta/Elev= 30
       0 1042.08    91.3  995.98   193.3  933.05   238.1   901.9   287.1  873.06
   340.6  846.62   429.2  813.23   470.2  802.37   516.5  784.23     585  763.69
   613.1  748.98   646.3  747.79  657.81738.7004   695.9  736.68  711.52738.7122
   721.8  741.55     769  742.99   787.9  749.65   931.7  754.87   975.2  766.55
  1037.3  811.32  1092.4  847.17  1122.9  859.67  1174.4  900.55  1199.9  906.15
  1229.4  931.47  1259.6  951.97  1284.4  958.58  1348.1 1003.06  1389.7  1020.5
#Mann= 4 ,-1,0
       0      .1       0     590     .06       0  657.81    .045       0
  711.52      .1       0
Bank Sta=657.81,711.52
XS Rating Curve= 0 ,0
Exp/Cntr(USF)=0,0
Exp/Cntr=0.3,0.1

Type RM Length L Ch R = 1 ,27540   ,541.4,538.3,533.2
XS GIS Cut Line= 2
1625599.90293673494861.214737986 1626574.4817141495758.744610464
#Sta/Elev= 30
       0 1020.09    40.5 1008.99   124.9   956.3   170.5  937.03   207.6  905.96
   234.5  894.64   265.7  871.06   319.1  836.99   358.6  817.84   421.2  767.23
   481.7  746.82   633.4  741.62647.5743735.5918   676.6  734.23700.8909 735.535
     736  746.42   825.2  752.09   864.1     774   878.6  773.71   907.7  783.08
   932.1  794.87   962.2  815.22   992.1  828.12  1083.8  856.79  1127.1  879.36
  1154.9   898.6    1182   904.9  1239.9  944.85  1290.3  970.29  1324.9  992.55
#Mann= 5 ,-1,0
       0      .1       0     390     .06       0     610      .1       0
647.5743    .045       0700.8909      .1       0
Bank Sta=647.5743,700.8909
XS Rating Curve= 0 ,0
Exp/Cntr(USF)=0,0
Exp/Cntr=0.3,0.1

Type RM Length L Ch R = 1 ,27001   ,437,453.3,460.4
XS GIS Cut Line= 6
1625285.93991293495096.2899607571625444.39727317495351.751720175
1625608.60954317495580.3966040911625659.44736801495637.160598174
1625862.08147718495807.1084210131626178.88235275496186.309762344
#Sta/Elev= 30
       0 1009.07      72  957.69   114.3  942.51   168.3  899.58     201  889.68
   253.6  860.76   320.5  836.36   359.8  816.65   383.6  798.78   409.9  790.66
   481.2  757.49   529.7  743.11     658  741.84     680734.4338   697.9  732.03
   733.4734.4374     745  743.14   860.6  746.31   959.2  759.66  1003.3  761.19
  1077.8  773.18  1112.7  774.06    1136  770.24    1182  800.29  1203.5  803.21
  1233.8  817.88  1254.1  819.95  1301.4   834.1  1376.1  834.45  1417.9  842.11
#Mann= 12 ,-1,0
       0      .1       0   468.6     .06       0  493.47     .07       0
  678.41      .1       0     680    .045       0   733.4      .1       0
  809.15     .05       0  829.15      .1       0  933.77     .05       0
 1003.77      .1       0 1059.27     .05       0 1167.65      .1       0
Bank Sta=680,733.4
XS Rating Curve= 0 ,0
Exp/Cntr(USF)=0,0
Exp/Cntr=0.3,0.1

Type RM Length L Ch R = 1 ,26548   ,190.8,192.6,192.9
XS GIS Cut Line= 3
1625107.18060161495254.0746601041625253.30433413495776.389278466
1625641.93128232496479.026800788
#Sta/Elev= 30
       0  939.18    36.9  925.65    73.8  904.42   107.9  893.36   165.8  863.07
   254.4  833.99   339.6  801.61   421.3  778.45   509.9  765.44   547.5  742.27
   627.2  742.14  641.11733.2034   652.9  731.26   697.9  733.34   711.6  743.13
   745.4  738.38   784.1  738.56     813  749.89   874.1  752.46   931.3  759.74
   948.2  759.02  1044.8  769.11  1059.3  772.95    1192  780.41    1204   788.5
  1211.3  804.83  1215.2  809.12  1257.2  839.69  1310.3  862.05  1345.3  865.83
#Mann= 6 ,-1,0
       0      .1       0     490     .06       0  641.11    .045       0
   697.9     .06       0  732.37     .05       0 1292.37      .1       0
#XS Ineff= 2 , 0
                          716.22          766.62
Permanent Ineff=
       F       F
Bank Sta=641.11,697.9
XS Rating Curve= 0 ,0
Exp/Cntr(USF)=0,0
Exp/Cntr=0.3,0.1

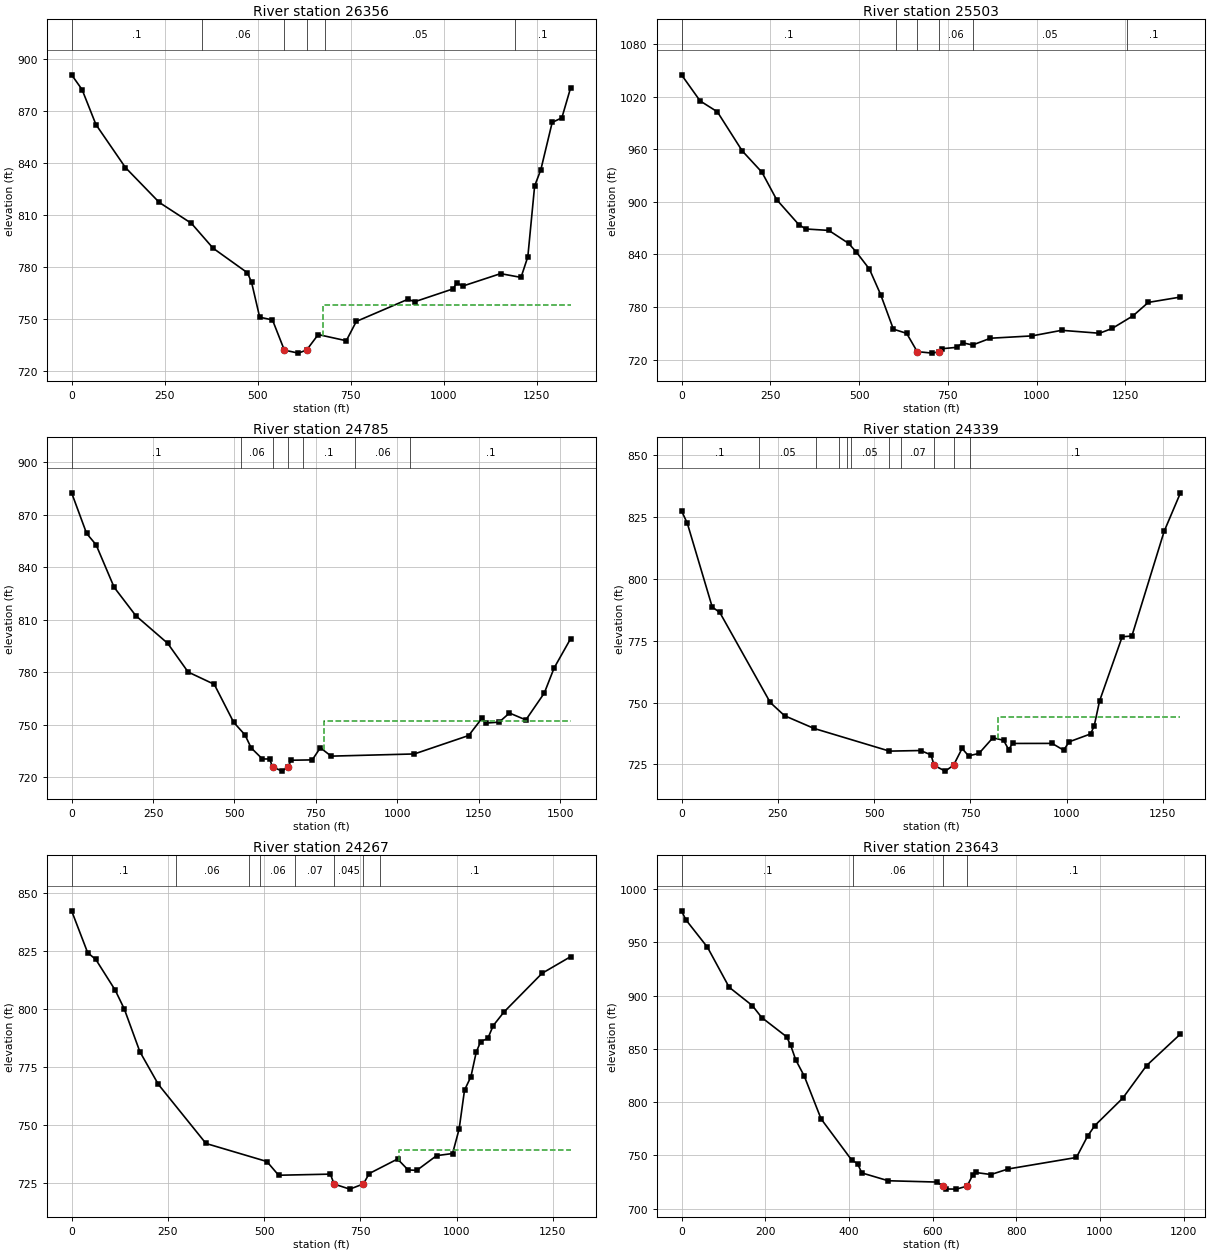
Type RM Length L Ch R = 1 ,26356   ,851.6,852.8,848.2
XS GIS Cut Line= 3
1624712.33562225495540.1040939691625079.19946134495835.460574591
1625464.71739394496615.823486549
#Sta/Elev= 30
       0  891.08    28.1  882.57    65.4  862.39   144.7  837.59   235.7  817.46
   322.1   805.4   380.4  791.05   472.7  776.87   483.7  771.48   505.6  751.26
     540  749.68   571.9  732.27   609.6  730.53   631.9  732.34     663  741.24
   738.4  737.68   765.4  748.81   904.5  761.63   922.1  760.15    1025  767.56
  1036.2  771.13  1050.9  769.16  1153.3  776.39  1208.2  774.22  1226.5  786.13
  1244.8  826.95  1261.5  836.37    1292  863.63    1318  866.27  1341.4  883.48
#Mann= 6 ,-1,0
       0      .1       0     350     .06       0   571.9    .045       0
   631.9     .06       0  680.98     .05       0 1190.98      .1       0
#XS Ineff= 2 , 0
                          676.65          758.38
Permanent Ineff=
       F       F
Bank Sta=571.9,631.9
XS Rating Curve= 0 ,0
Exp/Cntr(USF)=0,0
Exp/Cntr=0.3,0.1

Type RM Length L Ch R = 1 ,25503   ,724.2,718.2,710.2
XS GIS Cut Line= 6
1624060.22615701495733.8378982541624373.26358867496303.797388256
  1624424.493145496389.8615205881624625.70862184496683.177206919
1624735.18248425496849.421625093 1624788.8998965496934.129132837
#Sta/Elev= 30
       0 1044.74    52.5 1014.93   100.9 1002.59   170.9  958.03   226.5  933.63
   267.9  902.41   330.4  873.87   349.9   868.9     415  867.25   470.5  852.52
     492   842.8   529.4  823.07   560.9  794.11   596.8  754.62   634.2  749.83
   663.9  728.98   706.5  727.28   726.5  728.94   733.1   732.3   775.3  733.87
   792.1  739.07   819.9  736.55   870.2  744.28   987.2  746.93  1070.8   753.3
  1177.3  749.96  1212.9  755.38    1272   769.9  1314.8  785.13  1405.5  791.24
#Mann= 6 ,-1,0
       0      .1       0  605.27     .06       0   663.9    .045       0
   726.5     .06       0  820.42     .05       0  1255.2      .1       0
Bank Sta=663.9,726.5
XS Rating Curve= 0 ,0
Exp/Cntr(USF)=0,0
Exp/Cntr=0.3,0.1

Type RM Length L Ch R = 1 ,24785   ,459.2,445.3,432.4
XS GIS Cut Line= 2
 1623366.9201521496326.6706150311624468.33094132497391.038440487
#Sta/Elev= 30
       0  882.42      46  859.24    75.1  852.76   130.6  828.46   197.1  812.25
   294.9  796.48   357.6   780.1   437.9  773.07   497.4  751.41   532.2   744.2
   551.2  736.76   585.6  730.46   607.8  730.43   616.8725.9391   645.9   723.5
   664.5725.9234   673.7  729.72   738.7  729.92   763.6  736.86   796.7  732.06
  1052.2  733.31    1219  743.84  1259.3  753.61  1272.3  750.94  1312.3  751.47
  1344.2  756.68  1394.4  752.73    1451  768.06  1481.2   782.4  1531.7  799.07
#Mann= 7 ,-1,0
       0      .1       0     520     .06       0   616.8    .045       0
   664.5     .06       0     710      .1       0     870     .06       0
    1040      .1       0
#XS Ineff= 2 , 0
                          773.32          751.98
Permanent Ineff=
       F       F
Bank Sta=616.8,664.5
XS Rating Curve= 0 ,0
Exp/Cntr(USF)=0,0
Exp/Cntr=0.3,0.1

Type RM Length L Ch R = 1 ,24339   ,70.5,72.2,74.5
XS GIS Cut Line= 3
1622904.68251733 496976.775646521623837.54557754497189.791620899
1624078.10672102497428.516419772
#Sta/Elev= 30
       0  827.58    15.2  822.45    79.8  788.64    99.3  786.49   230.4  750.08
   267.6  744.72   344.2  739.58     540  730.41     621  730.65   647.9  728.88
  656.12724.6264   684.9  722.32   706.5724.7042   728.6  731.48   745.5   728.5
   772.4  729.46   808.5  735.78   836.3   734.8   849.6  731.05   859.9  733.51
   962.3  733.53   992.6  730.78  1006.5  734.16  1062.4  737.36  1071.7  740.58
  1085.7  750.69  1144.4  776.64  1169.6  776.94  1253.5   819.3  1295.8  834.83
#Mann= 11 ,-1,0
       0      .1       0     200     .05       0     350     .06       0
     410     .05       0     430     .06       0     440     .05       0
     540     .06       0     570     .07       0  656.12    .045       0
   706.5     .07       0     750      .1       0
#XS Ineff= 2 , 0
                          821.81           744.3
Permanent Ineff=
       F       F
Bank Sta=656.12,706.5
XS Rating Curve= 0 ,0
Exp/Cntr(USF)=0,0
Exp/Cntr=0.3,0.1

Type RM Length L Ch R = 1 ,24267   ,648,623.9,599.6
XS GIS Cut Line= 3
1622861.52841907497039.2113631481623794.39147928497252.227337527
1624034.95262276  497490.9521364
#Sta/Elev= 30
       0  842.28    41.7  824.21    62.8  821.31   113.3  808.03   136.9   799.9
   177.3  781.49   225.3   767.4   348.9  741.92   507.1  734.13   537.6  728.21
     672  728.69   681.7724.4068   722.4  722.22   757.7724.4548   772.9  728.94
   846.5  735.21   873.9  730.49   896.5  730.32   947.9  736.67   989.3  737.57
  1006.4  748.13  1020.4  764.94    1037  770.72  1050.9  781.36  1062.3  785.88
  1080.9  787.22  1094.9  792.75  1122.8  798.62  1221.9  815.34  1295.8  822.49
#Mann= 8 ,-1,0
       0      .1       0     270     .06       0     460     .05       0
     490     .06       0     580     .07       0   681.7    .045       0
   757.7     .06       0     800      .1       0
#XS Ineff= 2 , 0
                          850.69          739.22
Permanent Ineff=
       F       F
Bank Sta=681.7,757.7
XS Rating Curve= 0 ,0
Exp/Cntr(USF)=0,0
Exp/Cntr=0.3,0.1

Type RM Length L Ch R = 1 ,23643   ,458.8,460,459.6
XS GIS Cut Line= 2
 1623091.0021941498099.0326036391624147.31799146497546.029176784
#Sta/Elev= 30
       0  979.61    10.1  971.35      62  945.41   113.8  907.88   169.3   890.6
   191.6  879.44     251  861.39   260.6  853.62     273  839.62   293.4  824.38
   333.5  784.25   406.3  745.78   420.7  742.21   430.7  733.54   493.9  726.17
   610.6  724.93   624.2721.0637   632.5  718.44   656.8   718.3   682.5  721.16
   695.7  731.45   702.6  733.95   739.4     732   780.4  737.22   943.6  748.02
   970.3  768.01   987.8  778.03  1054.4  803.74  1111.3  834.32  1192.3  863.95
#Mann= 4 ,-1,0
       0      .1       0     410     .06       0   624.2    .045       0
   682.5      .1       0
Bank Sta=624.2,682.5
XS Rating Curve= 0 ,0
Exp/Cntr(USF)=0,0
Exp/Cntr=0.3,0.1