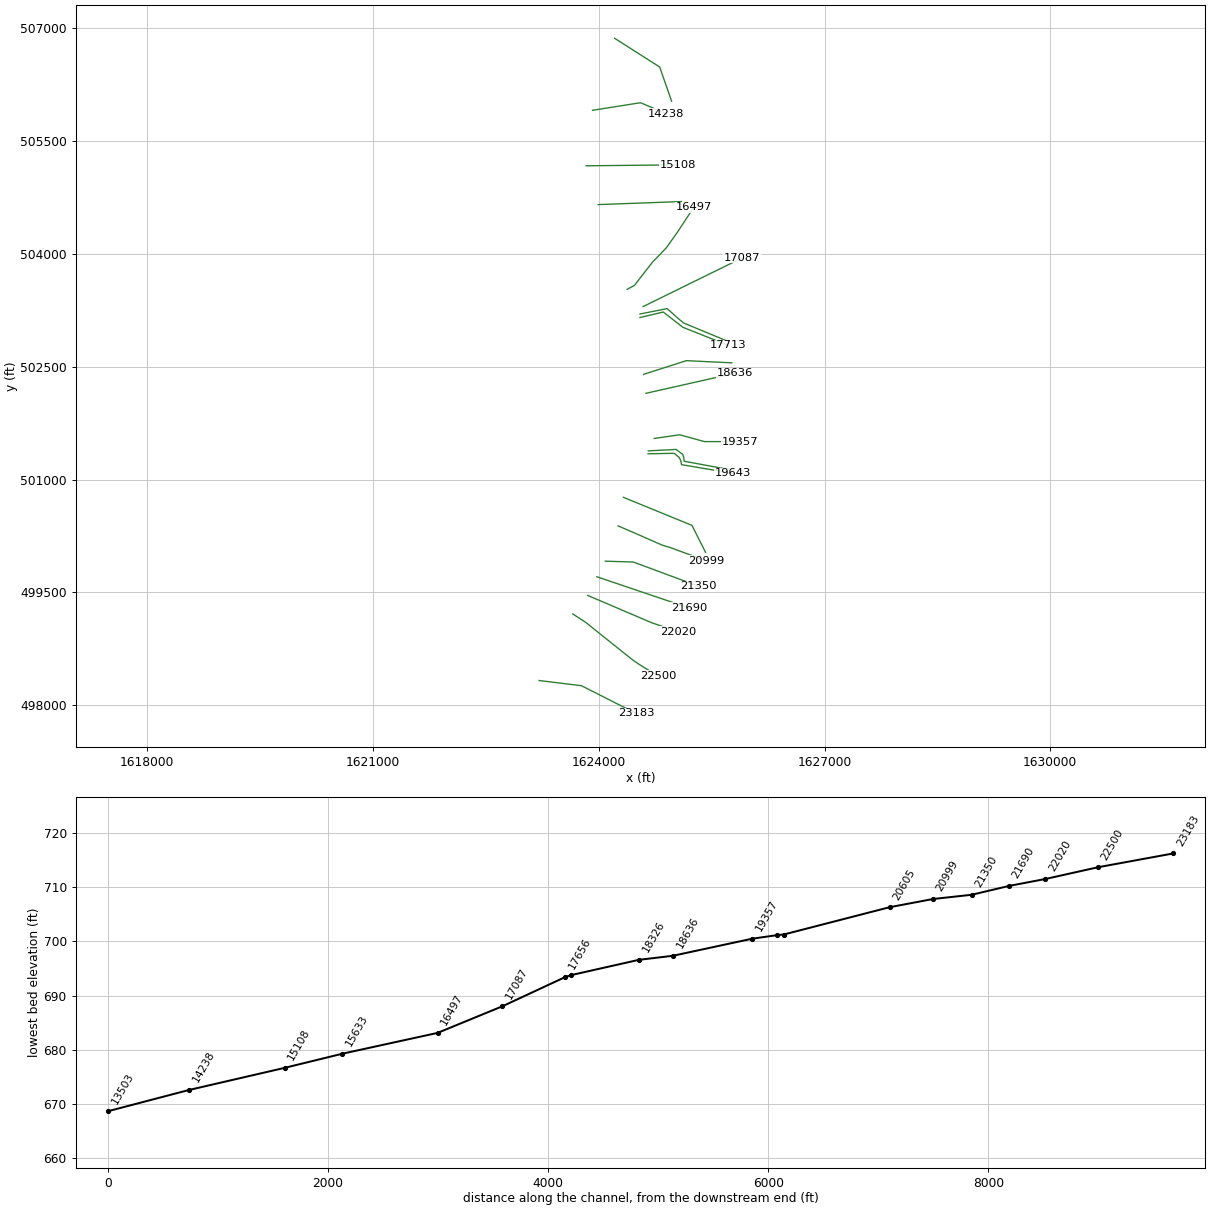
HEC-RAS study GraveCk1.prj: GraveCk1

--- GraveCk1.g01 (geometry) --- (continued)

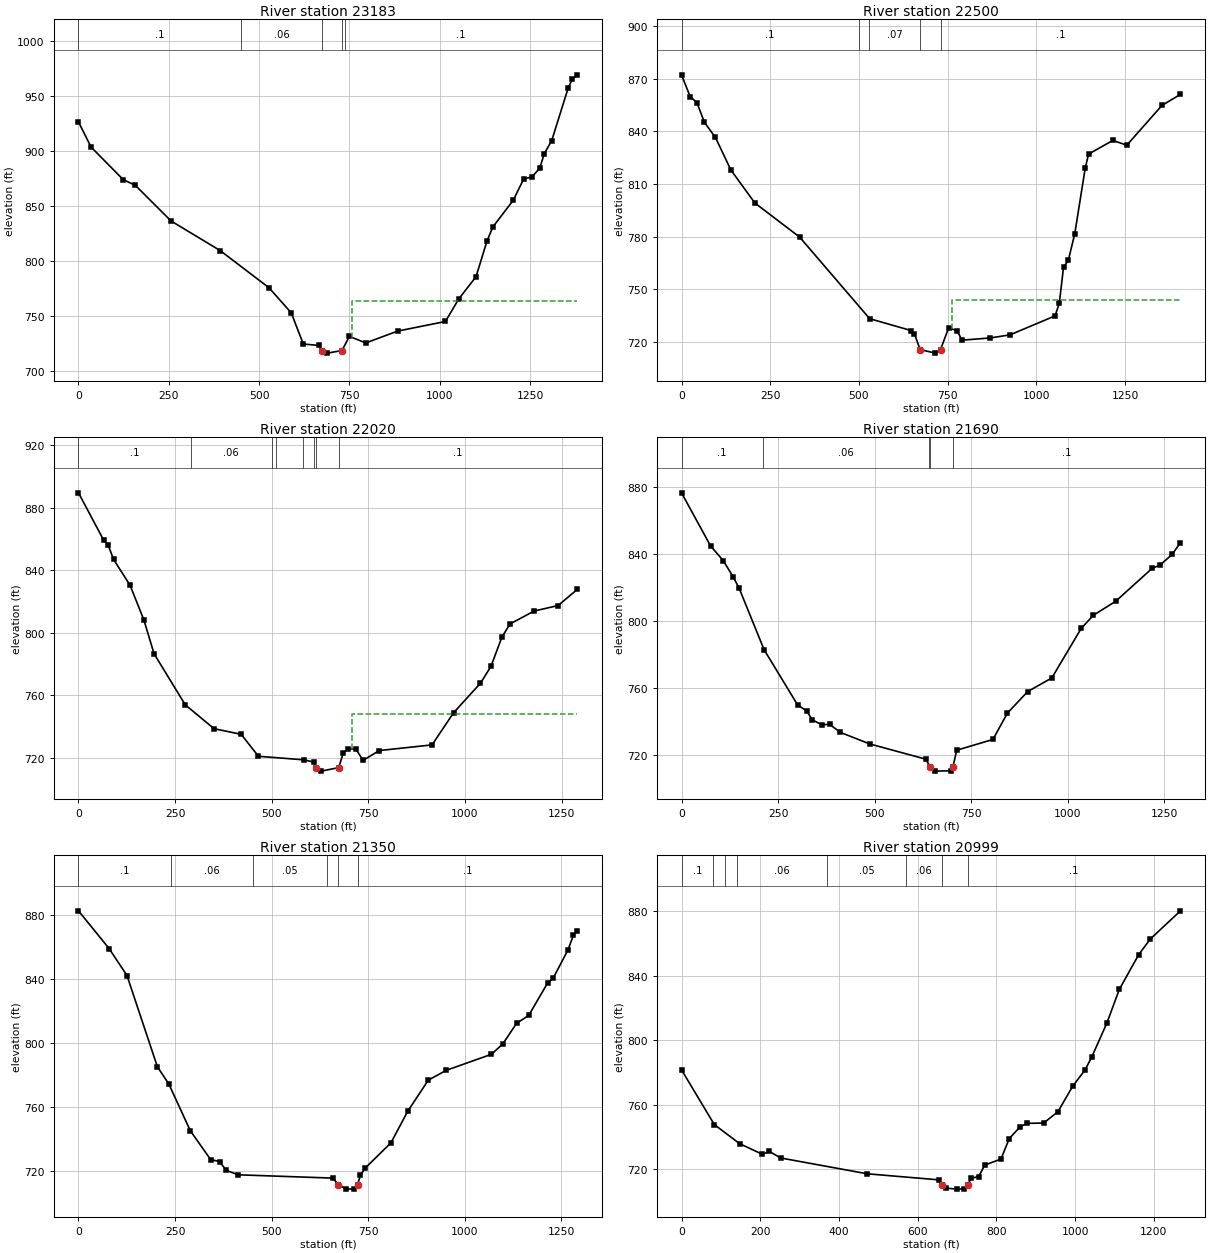
Type RM Length L Ch R = 1 ,23183   ,686.2,683.2,674.8
XS GIS Cut Line= 3
1623206.40064246498326.9906582311623769.45369166 498257.84379254
1624495.49578141497889.883685828
#Sta/Elev= 30
       0  926.34    34.9  903.46   124.1  873.78   157.2  868.76   256.4  836.26
   391.9  809.46   527.4  775.62   589.1  752.75   622.2   724.5   666.4  723.13
   673.3718.5416   688.4  716.19   729.4718.5234   749.9  731.46   795.1  725.44
   883.4  736.21  1015.8  744.95  1052.5  765.39  1100.4  785.58  1130.7  817.95
    1147  830.85  1203.4  855.08  1232.8  874.73  1254.8   876.2  1276.9  884.19
  1289.4  897.51    1310  909.38  1355.3  956.87  1367.5  965.69  1381.2  969.13
#Mann= 5 ,-1,0
       0      .1       0     450     .06       0   673.3    .045       0
   729.4     .06       0  737.28      .1       0
#XS Ineff= 2 , 0
                          758.17          763.58
Permanent Ineff=
       F       F
Bank Sta=673.3,729.4
XS Rating Curve= 0 ,0
Exp/Cntr(USF)=0,0
Exp/Cntr=0.3,0.1

Type RM Length L Ch R = 1 ,22500   ,470.5,479.8,486.2
XS GIS Cut Line= 6
 1623655.4595781499211.448069006 1623823.1994001499102.273090512
1624453.99177368498597.6326955851624534.56379101 498542.91069217
1624618.81001359498490.0682781791624791.70796175498387.140006334
#Sta/Elev= 30
       0  872.15    24.3  859.75    43.4   856.3    64.6  845.09    95.6  836.46
     139  817.99   206.8  799.13   332.7  779.77   530.2  733.26   647.9  726.46
   656.2  724.76   672.3715.6471   715.6  713.65   729.8  715.65   752.9  728.12
   776.3  726.35   790.7  721.02   870.5  722.31   925.7  724.06  1052.7  734.87
  1064.6  742.12  1076.5   762.6    1090  766.49  1108.2   781.7  1137.5   818.9
    1147  827.01  1215.5  834.78  1254.7  832.06  1353.9  854.73    1406  861.03
#Mann= 5 ,-1,0
       0      .1       0  499.23     .06       0  529.23     .07       0
   672.3    .045       0   729.8      .1       0
#XS Ineff= 2 , 0
                          761.56          743.86
Permanent Ineff=
       F       F
Bank Sta=672.3,729.8
XS Rating Curve= 0 ,0
Exp/Cntr(USF)=0,0
Exp/Cntr=0.3,0.1

Type RM Length L Ch R = 1 ,22020   ,328.3,330.6,332.8
XS GIS Cut Line= 3
1623853.20809056499458.502172492 1624707.6258901499093.398531278
1625050.14580093498976.715924292
#Sta/Elev= 30
       0  889.48    65.5  859.04    76.4  856.37    90.6  846.97   133.5  830.34
   169.1  808.21   195.6  786.54   276.2  753.92   350.6  738.64   420.9  735.03
   465.6  720.98   582.8   718.7   608.1  717.32   615.1  713.68   628.1  711.48
   673.2713.7122   685.5  723.28     698  725.82     718  725.53   736.4  718.31
     778  724.63   914.8  728.26   970.7   748.9    1040  767.68  1067.2  778.45
  1095.4  797.08  1116.2  805.57  1178.6  813.84    1241   817.4    1291  827.78
#Mann= 8 ,-1,0
       0      .1       0     290     .06       0     500     .07       0
     510     .05       0     580     .06       0     610      .1       0
   615.1    .045       0   673.2      .1       0
#XS Ineff= 2 , 0
                          708.31          748.22
Permanent Ineff=
       F       F
Bank Sta=615.1,673.2
XS Rating Curve= 0 ,0
Exp/Cntr(USF)=0,0
Exp/Cntr=0.3,0.1

Type RM Length L Ch R = 1 ,21690   ,339.6,339.2,336.5
XS GIS Cut Line= 2
1623973.65465261 499706.923206721625196.94004843499292.888149673
#Sta/Elev= 30
       0  876.53    75.1  844.83   108.2  835.96     134  826.16   149.1  819.53
   213.7   782.8   300.3  749.85   324.2  746.09   338.4  740.91   362.6  737.93
   383.4  738.15   411.1  733.36   487.6  726.42   632.1  717.36   644.1712.6224
     657   710.2   696.8  710.42   702.4712.5948   712.4   722.7     806  729.12
   843.6  744.87   896.1  757.78   958.4  765.86  1034.6   795.5  1065.7  803.29
  1123.8  811.71  1218.1  831.37  1238.9  833.41  1270.1  839.75  1291.5  846.81
#Mann= 5 ,-1,0
       0      .1       0     210     .06       0     640      .1       0
   644.1    .045       0   702.4      .1       0
Bank Sta=644.1,702.4
XS Rating Curve= 0 ,0
Exp/Cntr(USF)=0,0
Exp/Cntr=0.3,0.1

Type RM Length L Ch R = 1 ,21350   ,346.5,351.1,351.3
XS GIS Cut Line= 3
1624086.57330453499913.9407352431624459.20485587499902.648870051
1625321.15056554499582.712689606
#Sta/Elev= 30
       0  882.76    79.5  859.07   125.6  842.26   204.4  785.13   233.9  774.39
   289.7  745.09   342.3  727.05   365.2  725.86   382.8   720.3   413.7  717.53
   658.7  715.47   673.1 711.325   693.7  708.57   714.7  708.76   722.9 711.316
   729.9  717.23   742.6  721.74   809.2  737.56   852.4   757.2     906   776.8
   952.7  782.95  1069.4  792.96  1098.9  799.43  1134.6  812.35  1166.1  817.31
  1214.8  837.54  1229.1  840.49  1267.6  858.23  1281.6  867.39  1292.2  870.14
#Mann= 6 ,-1,0
       0      .1       0     240     .06       0   452.8     .05       0
   642.8      .1       0   673.1    .045       0   722.9      .1       0
Bank Sta=673.1,722.9
XS Rating Curve= 0 ,0
Exp/Cntr(USF)=0,0
Exp/Cntr=0.3,0.1

Type RM Length L Ch R = 1 ,20999   ,402.2,394.3,394.6
XS GIS Cut Line= 6
1624256.28613234500383.6773518321624530.37088601 500264.98598817
1624787.26866618 500151.629915671624857.04641376500122.716587678
1624952.93336108500094.2973531781625433.85497438499916.477086601
#Sta/Elev= 30
       0  781.74    83.3  747.83   147.5     736   205.4  729.38   223.1  731.15
   252.2   727.1   472.1  717.29     653  713.56   660.6710.2706   672.8  708.39
     701  707.79   718.1     708   726.7710.2455   736.1  714.54     755  715.58
   770.6  722.72   811.7  726.41   832.7  739.11   860.7  746.53   878.2  748.57
   920.1  748.78   956.4  755.77   993.6  771.45  1025.1  781.62  1042.6   789.8
    1081  810.87  1112.5  831.67  1161.5  853.11    1191  862.82  1267.8  880.34
#Mann= 8 ,-1,0
       0      .1       0      80     .06       0  109.95     .05       0
  139.95     .06       0  368.68     .05       0  571.07     .06       0
   660.6    .045       0   726.7      .1       0
Bank Sta=660.6,726.7
XS Rating Curve= 0 ,0
Exp/Cntr(USF)=0,0
Exp/Cntr=0.3,0.1

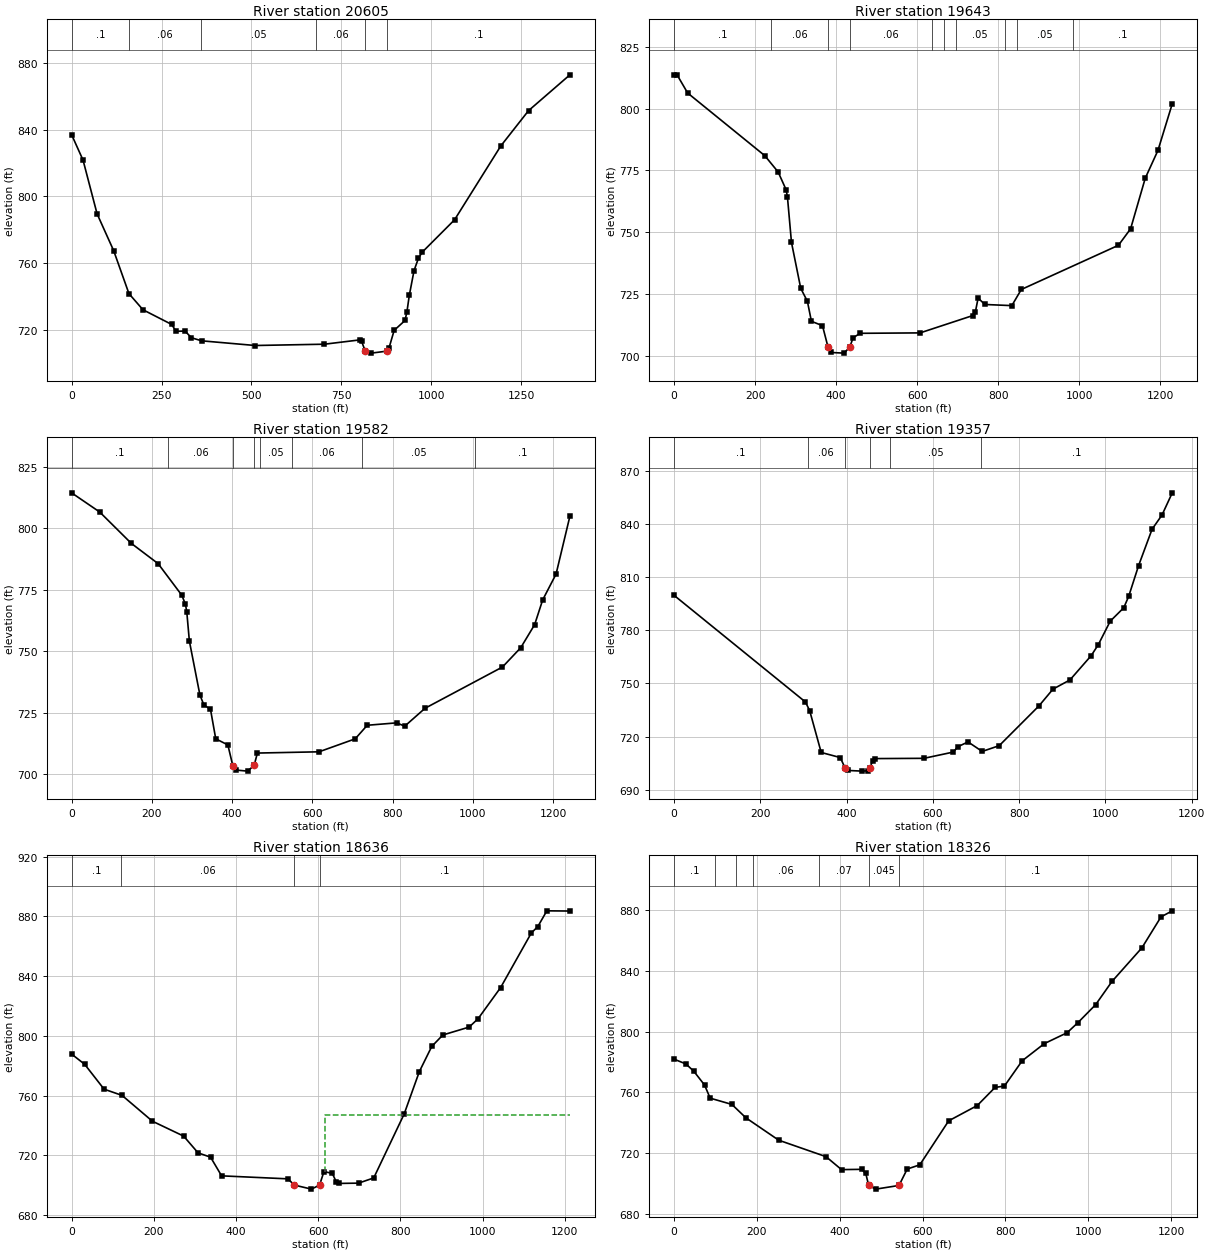
Type RM Length L Ch R = 1 ,20605   ,962.4,962.3,946.5
XS GIS Cut Line= 3
1624326.96732819500763.1266372461625238.22423676500390.227468699
1625418.49999374500032.145485657
#Sta/Elev= 30
       0  836.94    31.9  821.68    70.9  789.57     117  767.56   159.5  741.85
   198.5  732.21     278  723.47   290.7  719.32   315.5  719.47   333.2  715.47
   361.6  713.64   510.5  710.84   703.1  711.62   801.3  714.19   806.2  713.41
   816.4707.4973   833.1  706.28   877.5 707.495   882.7  709.47   896.8  719.88
     927  725.81   932.3  730.93     939  740.87   952.1  755.62   964.2  762.92
   974.8  766.64  1064.8  786.02  1193.4  830.19  1270.5  851.29  1385.5   872.7
#Mann= 6 ,-1,0
       0      .1       0     160     .06       0     360     .05       0
     680     .06       0   816.4    .045       0   877.5      .1       0
Bank Sta=816.4,877.5
XS Rating Curve= 0 ,0
Exp/Cntr(USF)=0,0
Exp/Cntr=0.3,0.1

Type RM Length L Ch R = 1 ,19643   ,59.9,60.5,62.4
XS GIS Cut Line= 6
1624653.95124925501342.1118651571625000.68672553501348.592902097
1625067.11735417501295.1243473421625089.80098346501249.757088763
1625099.52253887501197.9087932431625783.27193604501081.250128324
#Sta/Elev= 30
       0  813.41     7.7  813.61    33.9  806.26   224.2  780.96   257.1  774.37
   276.7  767.21     280  764.29   289.9  745.98   312.8   727.4   329.2  722.18
   339.1   714.1   366.4  712.34  380.01703.7393   387.4  701.51   419.8  701.25
  433.95703.7473   441.8  707.42   459.1  709.25   607.2  709.42     737  716.41
   743.6   717.9   750.3  723.49   766.9  720.89   833.5  720.43   856.8  726.94
  1096.4  744.79  1126.4  751.43  1162.6  771.88  1193.9   783.1  1229.2  801.93
#Mann= 10 ,-1,0
       0      .1       0     240     .06       0  380.01    .045       0
  433.95     .06       0  635.55     .05       0  665.55     .06       0
  695.55     .05       0  815.55      .1       0  845.55     .05       0
  985.55      .1       0
Bank Sta=380.01,433.95
XS Rating Curve= 0 ,0
Exp/Cntr(USF)=0,0
Exp/Cntr=0.3,0.1

Type RM Length L Ch R = 1 ,19582   ,214.3,225.2,234.8
XS GIS Cut Line= 6
1624657.19176772501380.9980867971625026.61087329501400.441197617
1625115.72513122501334.0105689821625130.30746433501288.643310403
1625135.16824204501243.2760518231625791.37323221501121.756609198
#Sta/Elev= 30
       0  814.48    70.1  806.66     149  793.87   215.6  785.64   274.6  772.78
   283.7  769.08     287  766.07   293.5   754.1   319.8  732.11   329.7  728.09
   346.1  726.31   359.2  714.29   389.4  711.81   401.6  703.42   408.6  701.58
   438.5  701.13   454.8  703.44     463  708.49   616.6     709   706.7  714.28
   736.7  719.81   810.1  720.79   830.1  719.43   880.7  726.73  1073.7  743.54
  1119.2   751.4  1153.8  760.79  1173.8  770.86  1207.2  781.39  1241.7  804.99
#Mann= 8 ,-1,0
       0      .1       0     240     .06       0   401.6    .045       0
   454.8     .06       0  469.93     .05       0  548.73     .06       0
  724.36     .05       0 1004.36      .1       0
Bank Sta=401.6,454.8
XS Rating Curve= 0 ,0
Exp/Cntr(USF)=0,0
Exp/Cntr=0.3,0.1

Type RM Length L Ch R = 1 ,19357   ,704.4,721.2,733.2
XS GIS Cut Line= 4
1624737.29814435 501546.104116731625074.85452562501595.176189777
1625403.48871178501504.4672062651625876.36505206501504.467206265
#Sta/Elev= 30
       0  799.81   304.8  739.52   314.6  734.63   341.3  711.02   385.5  708.14
  396.25702.4486   402.9  700.86   436.6  700.48   450.2  700.72  454.61702.3796
   460.4  706.44   465.8  707.56   579.5  707.71   647.6  711.25   657.8  714.24
   681.6  716.97   714.4  711.61   753.8  714.85   845.7  737.25   878.5  746.79
   917.8  751.98     967  765.69   983.5   771.9  1011.2  785.18  1042.5  792.74
  1053.9  799.16  1076.8   816.5  1108.1  837.09  1131.1   845.1  1154.9  857.64
#Mann= 6 ,-1,0
       0      .1       0     310     .06       0  396.25    .045       0
  454.61     .06       0   501.1     .05       0  712.03      .1       0
Bank Sta=396.25,454.61
XS Rating Curve= 0 ,0
Exp/Cntr(USF)=0,0
Exp/Cntr=0.3,0.1

Type RM Length L Ch R = 1 ,18636   ,304.4,309.8,308.2
XS GIS Cut Line= 2
 1624627.1736316502146.8295056471625809.58503491 502413.53884474
#Sta/Elev= 30
       0  787.77    31.9  780.88      79  764.26   122.8  760.08   196.7  742.78
   272.6  732.82   307.7  721.59     338  718.74   364.9  706.22   526.3  704.21
   541.8700.0321   583.5  697.33   603.2700.0472   613.8  709.07     634   707.9
   644.1  702.07   650.8  701.15   697.9  701.34   734.9  704.82   808.9  747.61
   845.8  775.97   876.1  792.88     903  800.53   966.9  805.82   988.6  811.37
  1043.5  832.25  1118.3  868.85    1134  873.11    1156  883.66  1212.1  883.52
#Mann= 4 ,-1,0
       0      .1       0     120     .06       0   541.8    .045       0
   603.2      .1       0
#XS Ineff= 2 , 0
                          616.51          746.76
Permanent Ineff=
       F       F
Bank Sta=541.8,603.2
XS Rating Curve= 0 ,0
Exp/Cntr(USF)=0,0
Exp/Cntr=0.3,0.1

Type RM Length L Ch R = 1 ,18326   ,632.5,612.6,580.1
XS GIS Cut Line= 3
1624594.65021901502398.5728681861625163.63014241502580.824249898
1625768.17131102502551.930738164
#Sta/Elev= 30
       0  781.89      29  778.72    48.1  773.89    73.8  764.93    87.5  756.27
   139.9  752.16   173.7  743.37   252.9  728.69     367  717.89   404.5  709.38
   452.7  709.57     463  706.87     470698.9689   487.2  696.58   543.2698.9924
     563  709.75   593.4  712.53   663.1  741.39   732.1  751.44   774.9  763.27
   797.8  764.28   840.4  780.77   893.8  792.04   948.9  799.21     975  805.82
  1017.8  817.63  1057.2  832.85  1129.5  854.94  1175.5  875.22  1202.7   879.2
#Mann= 7 ,-1,0
       0      .1       0     100     .06       0     150      .1       0
     190     .06       0     350     .07       0     470    .045       0
   543.2      .1       0
Bank Sta=470,543.2
XS Rating Curve= 0 ,0
Exp/Cntr(USF)=0,0
Exp/Cntr=0.3,0.1

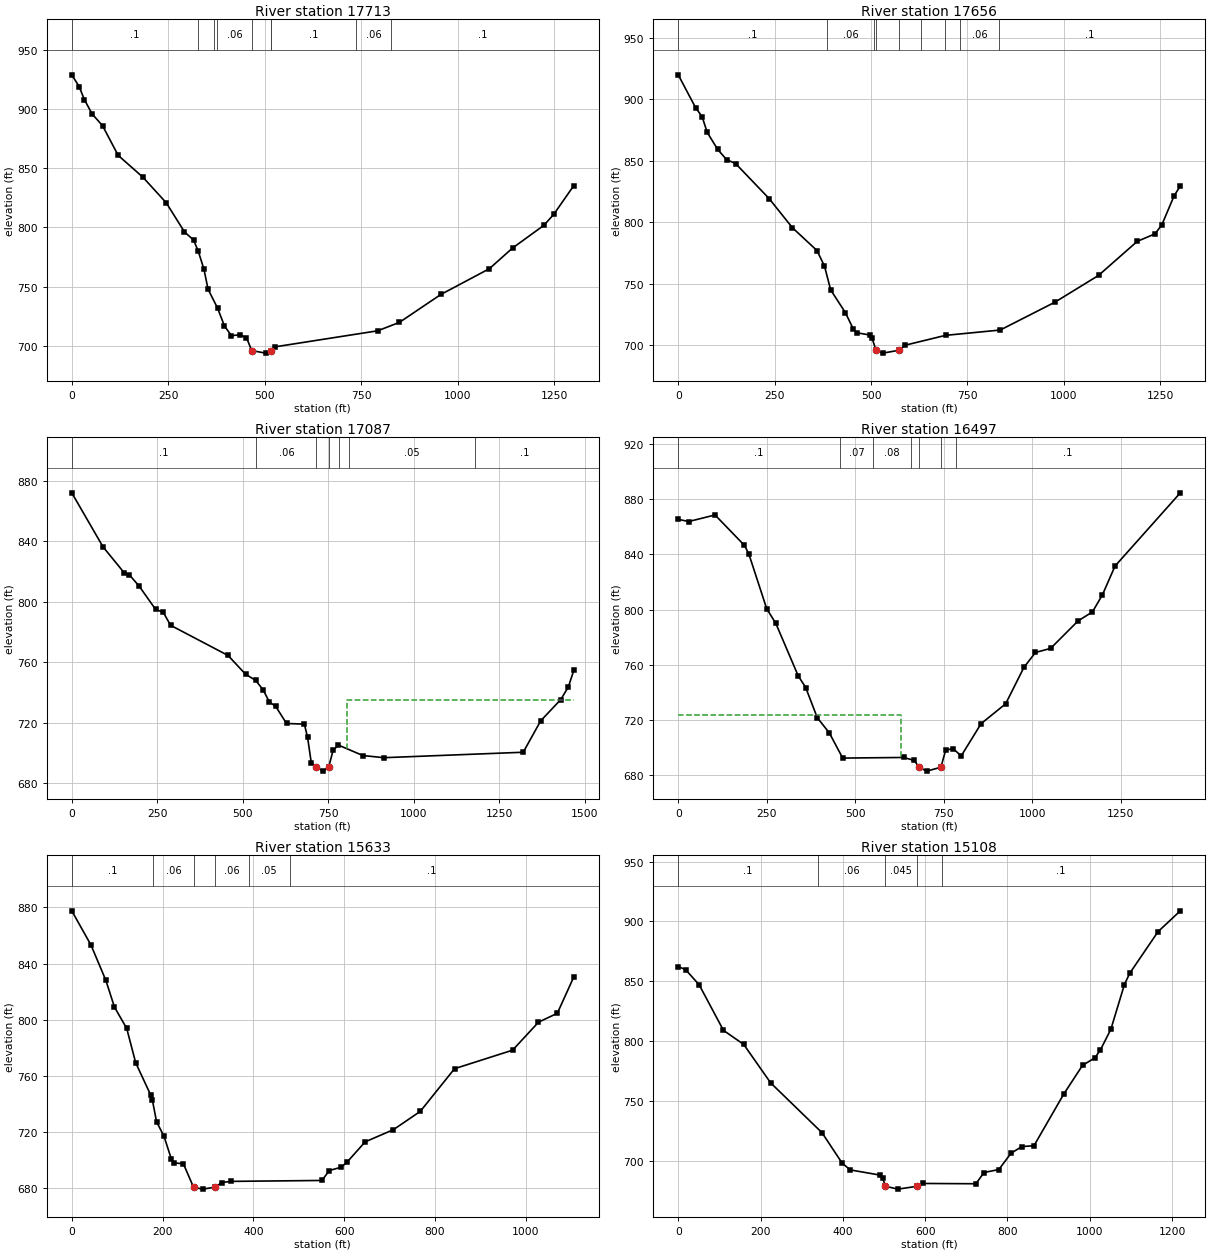
Type RM Length L Ch R = 1 ,17713   ,59,56.9,58.6
XS GIS Cut Line= 4
1624547.85727052503154.7109931031624857.00273255503227.622658678
  1625116.568262 503024.928228381625724.65155289502782.861498673
#Sta/Elev= 30
       0  929.08    19.1  919.16    32.6  908.19    52.8  895.97    79.7  886.11
   120.3  860.97   184.3  842.56     245  820.86   292.2  796.24   315.8   789.4
   327.8  780.05   342.6  764.77   353.3  747.78   377.8  731.95   395.9  716.66
   413.8  708.59     436  709.23   452.7  706.96   466.6695.9244   502.6  693.78
   515.2695.9232   527.6  699.13   792.9  712.65   849.4  719.79   956.6  743.35
  1082.5  765.15  1142.5   782.6  1223.7   801.8  1249.4  811.09  1301.5  835.49
#Mann= 9 ,-1,0
       0      .1       0  327.63     .06       0  367.63      .1       0
  377.63     .06       0   466.6    .045       0   515.2     .06       0
  517.63      .1       0  736.96     .06       0  826.96      .1       0
Bank Sta=466.6,515.2
XS Rating Curve= 0 ,0
Exp/Cntr(USF)=0,0
Exp/Cntr=0.3,0.1

Type RM Length L Ch R = 1 ,17656   ,541.9,569.6,591.4
XS GIS Cut Line= 5
1624548.49142062503201.7646105391624908.04089846503272.827891334
1625083.02889584503118.2551603161625131.15059512503080.341094217
1625722.76971116502834.811034873
#Sta/Elev= 30
       0  919.96    45.1  893.15    61.8  885.98    75.2  873.05   102.4  859.18
   125.3  850.94   148.8   847.7   235.7   819.2   295.9  795.54   359.7  776.91
   379.2  764.26   395.2   744.9   433.3  726.42   453.3  713.41   462.3  710.03
   497.5  708.11   502.2   705.9   512.8695.7646     530   693.4   573.3695.7559
   586.9  699.74   693.1  707.87   834.9   712.2   976.8  734.89  1089.7  756.65
    1190  784.36  1236.3  790.53    1254  797.94    1286  821.63  1301.8   829.5
#Mann= 9 ,-1,0
       0      .1       0   386.5     .06       0   506.5      .1       0
   512.8    .045       0   573.3      .1       0  629.99     .06       0
  691.25      .1       0  731.25     .06       0  831.25      .1       0
Bank Sta=512.8,573.3
XS Rating Curve= 0 ,0
Exp/Cntr(USF)=0,0
Exp/Cntr=0.3,0.1

Type RM Length L Ch R = 1 ,17087   ,577.6,589.4,591.1
XS GIS Cut Line= 2
1624589.49512093503300.3119382671625906.57827694503947.877823308
#Sta/Elev= 30
       0  871.99    91.3   836.3   153.5  819.06   168.1  817.86   197.4  810.18
   244.9  794.98   267.5  793.02   288.8  784.43   456.9  764.47   508.1  752.06
   537.1   748.1   559.3  741.82   577.6  733.72   595.9   730.9   627.8  719.52
   679.9  719.11   689.2   710.5   700.1  693.64   714.5690.6633   734.8  688.03
     751 690.635     764  701.88   779.7  705.22   850.8  698.35   912.1  696.91
  1319.7  700.51  1370.9   721.3  1429.4  735.31  1451.6  743.67  1467.7  754.74
#Mann= 7 ,-1,0
       0      .1       0     540     .06       0   714.5    .045       0
     751     .06       0     780      .1       0     810     .05       0
    1180      .1       0
#XS Ineff= 2 , 0
                          805.88          735.03
Permanent Ineff=
       F       F
Bank Sta=714.5,751
XS Rating Curve= 0 ,0
Exp/Cntr(USF)=0,0
Exp/Cntr=0.3,0.1

Type RM Length L Ch R = 1 ,16497   ,882.8,864,848.4
XS GIS Cut Line= 6
1624376.40400234503529.4194199291624473.64330918503581.630273506
1624713.14184593503889.9738169161624895.67264885504079.257559091
1625045.74682376504290.2033314261625262.84350242504621.208246842
#Sta/Elev= 30
       0  865.44    29.5  863.86     104   868.6   186.8  846.66   199.2   840.6
     250   800.7   275.8  790.07     339   752.1   360.2  743.65   392.8  721.83
   426.9  710.82   464.7  692.57     637  693.01   667.4  690.83     680685.9329
   702.2  683.12   742.3685.9488   755.5  698.27   776.5  699.43   799.6  694.14
   855.8  717.49   925.2  731.88   976.9   758.3  1009.5  769.06  1052.2  771.98
    1130  791.95  1170.3  798.37  1198.7  810.81  1234.2  831.59  1418.7  884.64
#Mann= 7 ,-1,0
       0      .1       0  456.54     .07       0  550.82     .08       0
  658.75     .07       0     680    .045       0   742.3     .06       0
  783.92      .1       0
#XS Ineff= 2 , 0
           628.6  723.92
Permanent Ineff=
       F       F
Bank Sta=680,742.3
XS Rating Curve= 0 ,0
Exp/Cntr(USF)=0,0
Exp/Cntr=0.3,0.1

Type RM Length L Ch R = 1 ,15633   ,522.8,525.5,527.9
XS GIS Cut Line= 2
1623992.66373451504656.4948182551625098.19858655504696.787660243
#Sta/Elev= 30
       0   877.6    42.3  853.25    75.2  827.98      94  809.06   121.1  793.78
   140.8  769.37   174.2  746.15   177.6  742.79   186.8  727.34   203.2  716.97
   219.6  700.56   226.2  697.96   245.9   697.4   268.3680.6558   288.6  679.29
   314.7680.6409   331.3  684.01   350.9  684.81   551.2  685.47   567.6  692.56
   593.9  694.94   606.9  698.65   646.4  712.96   708.8  721.68   767.9  734.68
   843.4   765.1   971.3  778.31  1028.4  798.24  1069.9   804.6  1106.3  830.58
#Mann= 6 ,-1,0
       0      .1       0     180     .06       0   268.3    .045       0
   314.7     .06       0     390     .05       0     480      .1       0
Bank Sta=268.3,314.7
XS Rating Curve= 0 ,0
Exp/Cntr(USF)=0,0
Exp/Cntr=0.3,0.1

Type RM Length L Ch R = 1 ,15108   ,858.8,869.9,865.8
XS GIS Cut Line= 2
1623833.24039643505172.609345391 1625053.3317828505184.879052146
#Sta/Elev= 30
       0  862.38      18  859.79    50.8   847.2   109.9  809.15   159.1  797.43
   224.7   765.3   349.4  723.77   398.6  698.23   418.3  692.71   490.6  688.39
   496.9  686.04   503.4  679.11   533.7  676.68  581.29 679.069   595.5  681.41
   723.4  681.16   743.1  690.53   779.2  693.03   808.7  706.59     835  712.21
   864.5  712.86   936.7  755.87   982.6  779.98  1012.2  786.13  1025.3  792.36
  1051.5  810.11  1084.3  847.33  1097.1  856.67    1166  891.48  1220.2  908.89
#Mann= 5 ,-1,0
       0      .1       0     340     .06       0   503.4    .045       0
  581.29     .06       0     640      .1       0
Bank Sta=503.4,581.29
XS Rating Curve= 0 ,0
Exp/Cntr(USF)=0,0
Exp/Cntr=0.3,0.1

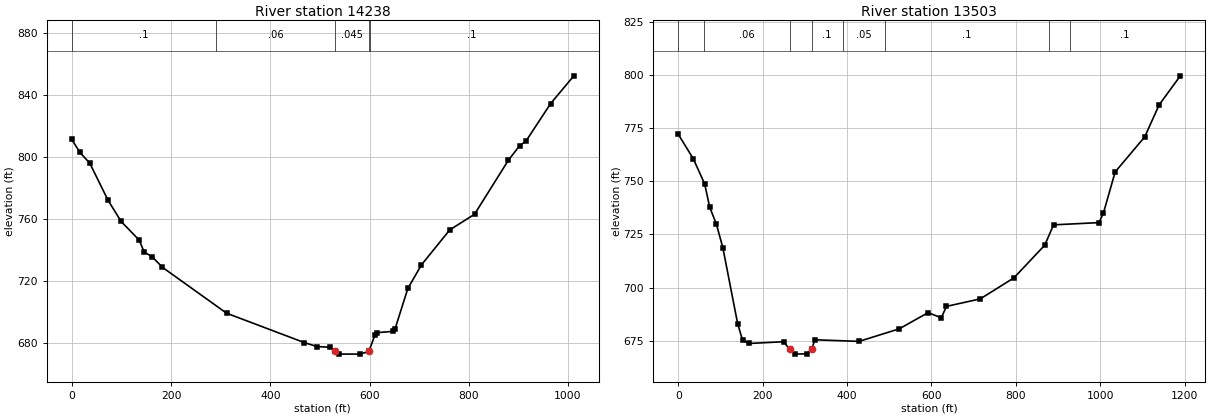
Type RM Length L Ch R = 1 ,14238   ,754.8,735.6,715.7
XS GIS Cut Line= 3
1623917.11465578505910.6095251291624554.24521971506011.341630099
1624891.69777136505867.798380517
#Sta/Elev= 30
       0  811.31    16.4   802.9    36.3  795.93    72.8  772.17    99.4  758.31
   135.9  746.26   145.9  738.59   162.5  735.39   182.4  728.75     312  699.04
   468.8  680.03   494.6  677.47   521.2  677.06  531.13674.3346   537.8  672.65
     581   672.6   598.7674.3487   610.9  684.94   614.2  686.47   647.6  687.31
   651.2  688.61   677.3  715.05   704.7  730.28   761.7  752.84   811.6  762.94
   879.9  797.87   902.4   807.2     915  810.05     965  834.46  1011.8  852.38
#Mann= 5 ,-1,0
       0      .1       0     290     .06       0  531.13    .045       0
   598.7     .06       0     600      .1       0
Bank Sta=531.13,598.7
XS Rating Curve= 0 ,0
Exp/Cntr(USF)=0,0
Exp/Cntr=0.3,0.1

Type RM Length L Ch R = 1 ,13503   ,502.1,525,539
XS GIS Cut Line= 3
 1624211.5096084506867.6346693321624809.07511437506486.534219097
1624967.61290166506032.262482415
#Sta/Elev= 30
       0  772.14    35.8  760.58    62.7  748.74    74.7  737.74    90.3  729.93
   105.8  718.69   140.8  683.03   152.5  675.17   168.1  673.71   249.8  674.52
   263.9670.9994   276.5  668.69     305  668.87   316.1 671.018     324  675.44
   428.6  674.69   523.6  680.57   592.2  688.21   623.4  685.78   635.7  691.16
   715.8  694.68   795.7   704.6   868.7  719.98   889.5  729.52   997.2  730.57
  1007.7  735.07  1035.5  754.42  1105.6  770.93  1139.7  785.97  1189.9  799.64
#Mann= 8 ,-1,0
       0      .1       0      60     .06       0   263.9    .045       0
   316.1      .1       0     390     .05       0     490      .1       0
  878.75     .08       0  928.75      .1       0
Bank Sta=263.9,316.1
XS Rating Curve= 0 ,0
Exp/Cntr(USF)=0,0
Exp/Cntr=0.3,0.1