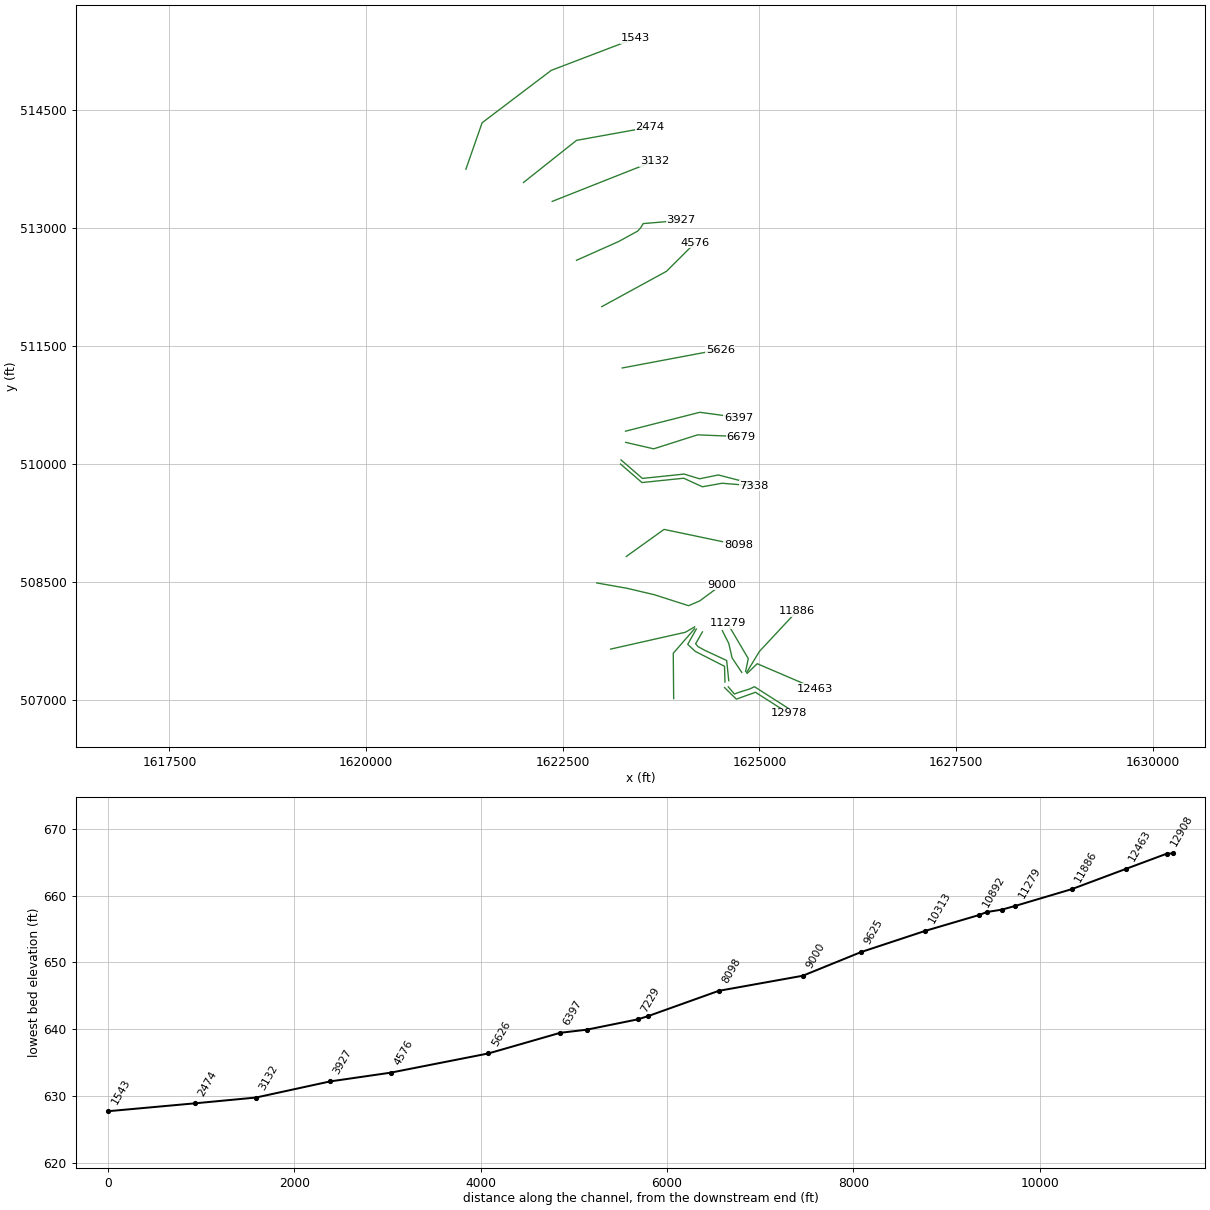
HEC-RAS study GraveCk1.prj: GraveCk1

--- GraveCk1.g01 (geometry) --- (continued)

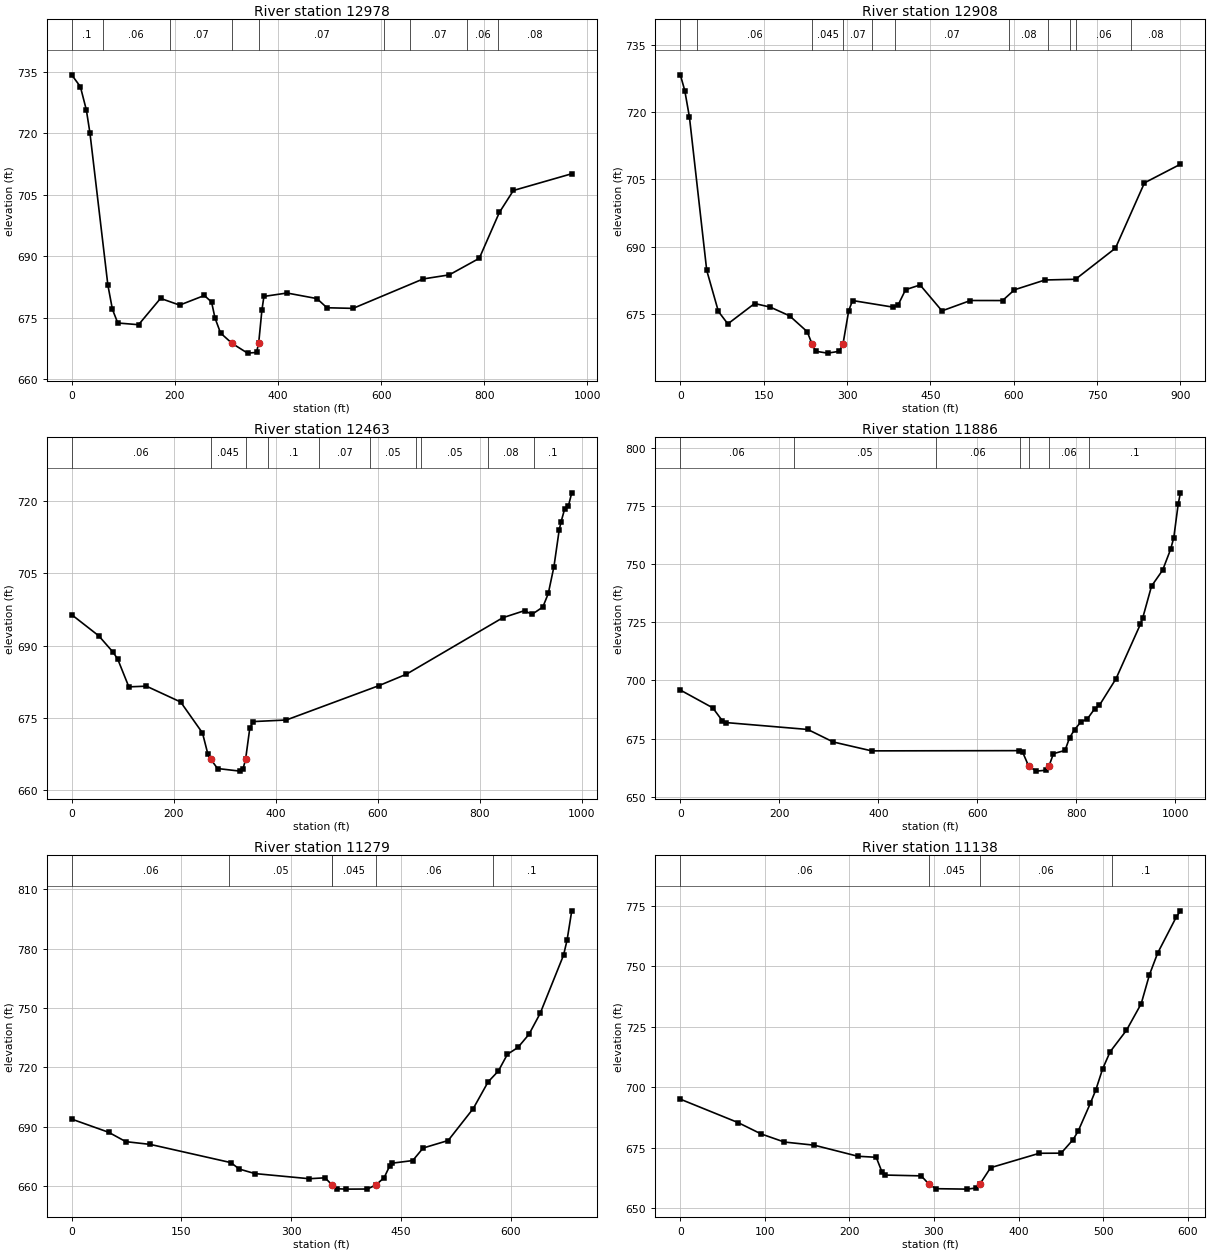
Type RM Length L Ch R = 1 ,12978   ,70.5,70,68.7
XS GIS Cut Line= 6
1624556.15780738507162.7445735481624705.75310923507015.172055536
1624871.27031872507074.4903618281624928.67513126507094.582046217
1624945.89657502507104.1495149741625370.69218782506834.346896035
#Sta/Elev= 30
       0  734.29    16.9  731.39    28.5  725.69    35.4  720.12    70.2  682.94
      79  677.02    89.4  673.68   129.7  673.26   172.3  679.69   209.4  678.05
   257.3   680.4   271.3  678.79   277.9  674.91   288.7  671.23     311   668.7
     341  666.32   358.4  666.49   362.6668.7261   368.9  676.83   372.8  680.17
   417.6     681   475.6  679.64     495   677.4   545.6  677.25   681.6  684.44
   732.1  685.43   790.4  689.48   829.3  700.67   856.5  706.04   969.7  710.13
#Mann= 9 ,-1,0
       0      .1       0      60     .06       0     190     .07       0
     311    .045       0   362.6     .07       0  606.48     .06       0
  656.48     .07       0  766.48     .06       0  826.48     .08       0
Bank Sta=311,362.6
XS Rating Curve= 0 ,0
Exp/Cntr(USF)=0,0
Exp/Cntr=0.3,0.1

Type RM Length L Ch R = 1 ,12908   ,436.5,444.3,399.8
XS GIS Cut Line= 6
1624603.82964034507171.529744101 1624682.1779701 507079.93132376
1624727.18517107507097.934204149 1624876.6090783 507144.74169316
1624936.01858358507173.5463017821625364.48713684506899.902519872
#Sta/Elev= 30
       0  728.27       8  724.76    16.4  718.84    47.5  684.72    68.5  675.57
    85.5   672.8   133.7  677.34     162  676.53   196.6   674.6   228.3  671.07
   237.2668.2841     244   666.7   264.9  666.29     286  666.69   292.7668.2856
   303.1  675.78     310     678     382  676.55   391.6  676.93   405.4  680.42
   431.5  681.47   470.9   675.7   522.2  678.01   579.9     678   601.4   680.4
   656.3  682.58   711.2  682.74   783.1  689.67   835.3  704.21     900  708.36
#Mann= 11 ,-1,0
       0      .1       0      30     .06       0   237.2    .045       0
   292.7     .07       0  345.59     .06       0  385.59     .07       0
  591.62     .08       0  661.62     .07       0  701.62     .08       0
  711.62     .06       0  811.62     .08       0
Bank Sta=237.2,292.7
XS Rating Curve= 0 ,0
Exp/Cntr(USF)=0,0
Exp/Cntr=0.3,0.1

Type RM Length L Ch R = 1 ,12463   ,549.1,577.2,598.9
XS GIS Cut Line= 3
1624845.16064047507343.379503814 1624971.1808032507465.799090458
1625711.09918718507148.948395615
#Sta/Elev= 30
       0  696.41    53.1  692.03    80.9  688.67    90.2  687.22   112.1  681.45
   146.6  681.59   213.7  678.31   256.5  671.89   267.2  667.46     273666.4069
     286  664.52   329.9  663.98     336  664.44     341  666.41   349.3   672.9
     356  674.25   420.9  674.58   602.7  681.71   656.2  684.06   845.4  695.78
   888.1  697.25   902.5  696.47   923.9  697.99   934.6  700.81   945.7  706.38
     956  713.98   959.6  715.63   966.7  718.33   973.9   718.9   980.6  721.67
#Mann= 10 ,-1,0
       0     .06       0     273    .045       0     341     .06       0
  385.69      .1       0  485.69     .07       0  585.69     .05       0
  675.69     .08       0  685.69     .05       0  815.69     .08       0
  905.69      .1       0
Bank Sta=273,341
XS Rating Curve= 0 ,0
Exp/Cntr(USF)=0,0
Exp/Cntr=0.3,0.1

Type RM Length L Ch R = 1 ,11886   ,577.6,606.6,632.2
XS GIS Cut Line= 3
1624836.15920028507352.3809440081624999.98541182 507622.42414984
1625473.46116604508130.105376804
#Sta/Elev= 30
       0  695.84    65.5  688.19    84.7  682.68    92.4  681.85   257.4  678.89
   308.7  673.51   386.5  669.68   684.1  669.78   691.6  669.03   703.7 663.066
   719.3  660.97   738.5  661.35   744.4  663.03   753.7  668.49     777  669.87
   786.2   675.3   796.2   678.8   809.4  682.21   821.7   683.3   837.3   687.9
   846.5  689.29     880  700.71   929.4   724.2   933.9   726.8   951.8  740.56
   974.2   747.4   990.5  756.48   996.7  761.39  1005.6  775.77  1010.1  780.66
#Mann= 7 ,-1,0
       0     .06       0     230     .05       0  515.85     .06       0
  685.85      .1       0   703.7    .045       0   744.4     .06       0
  825.85      .1       0
Bank Sta=703.7,744.4
XS Rating Curve= 0 ,0
Exp/Cntr(USF)=0,0
Exp/Cntr=0.3,0.1

Type RM Length L Ch R = 1 ,11279   ,151.4,141.2,133.5
XS GIS Cut Line= 3
 1624824.4934954507368.7282058621624857.76265675507530.609459857
1624594.92060307507977.080893499
#Sta/Elev= 30
       0  693.86    50.5   687.2      74  682.46   107.5  681.06   217.6  671.86
     229  668.61   250.4  666.32   324.7  663.72   346.3  664.18   355.8  660.58
   362.3  658.65     375  658.46   404.1  658.51   415.8  660.58     427  664.25
   434.6  670.17   438.4   671.6   466.1   672.9   480.3  679.24   514.5  683.03
   548.8  699.19   569.1  712.66   583.1  718.16   595.5  726.63   609.9  730.08
   624.9  736.69   640.2  747.26   672.2  776.73     677  784.33   683.4  799.13
#Mann= 6 ,-1,0
       0     .06       0  215.26     .05       0  355.26     .06       0
   355.8    .045       0   415.8     .06       0  575.26      .1       0
Bank Sta=355.8,415.8
XS Rating Curve= 0 ,0
Exp/Cntr(USF)=0,0
Exp/Cntr=0.3,0.1

Type RM Length L Ch R = 1 ,11138   ,135.5,165.1,204.7
XS GIS Cut Line= 4
 1624775.0210225507355.2511864531624652.16239598507539.539126234
1624610.00502413507723.8270660151624528.09927312507885.229575366
#Sta/Elev= 30
       0  695.08    68.4  685.39    95.4  680.74     123  677.37   158.5  676.06
     210  671.49   231.7  671.07   238.4  665.09   241.7  663.73   284.9  663.39
  294.21659.9216   302.3  658.09   339.3  657.91   349.4  658.36  354.14 659.895
     367  666.77   424.7  672.73   450.4  672.77   464.5  678.34   470.5  681.84
     485   693.4   491.4  698.87   499.5  707.61   508.4  714.69   527.7  723.55
   545.1  734.51   554.8  746.41   564.5  755.39   586.5  770.27   591.5  772.91
#Mann= 4 ,-1,0
       0     .06       0  294.21    .045       0  354.14     .06       0
  510.53      .1       0
Bank Sta=294.21,354.14
XS Rating Curve= 0 ,0
Exp/Cntr(USF)=0,0
Exp/Cntr=0.3,0.1

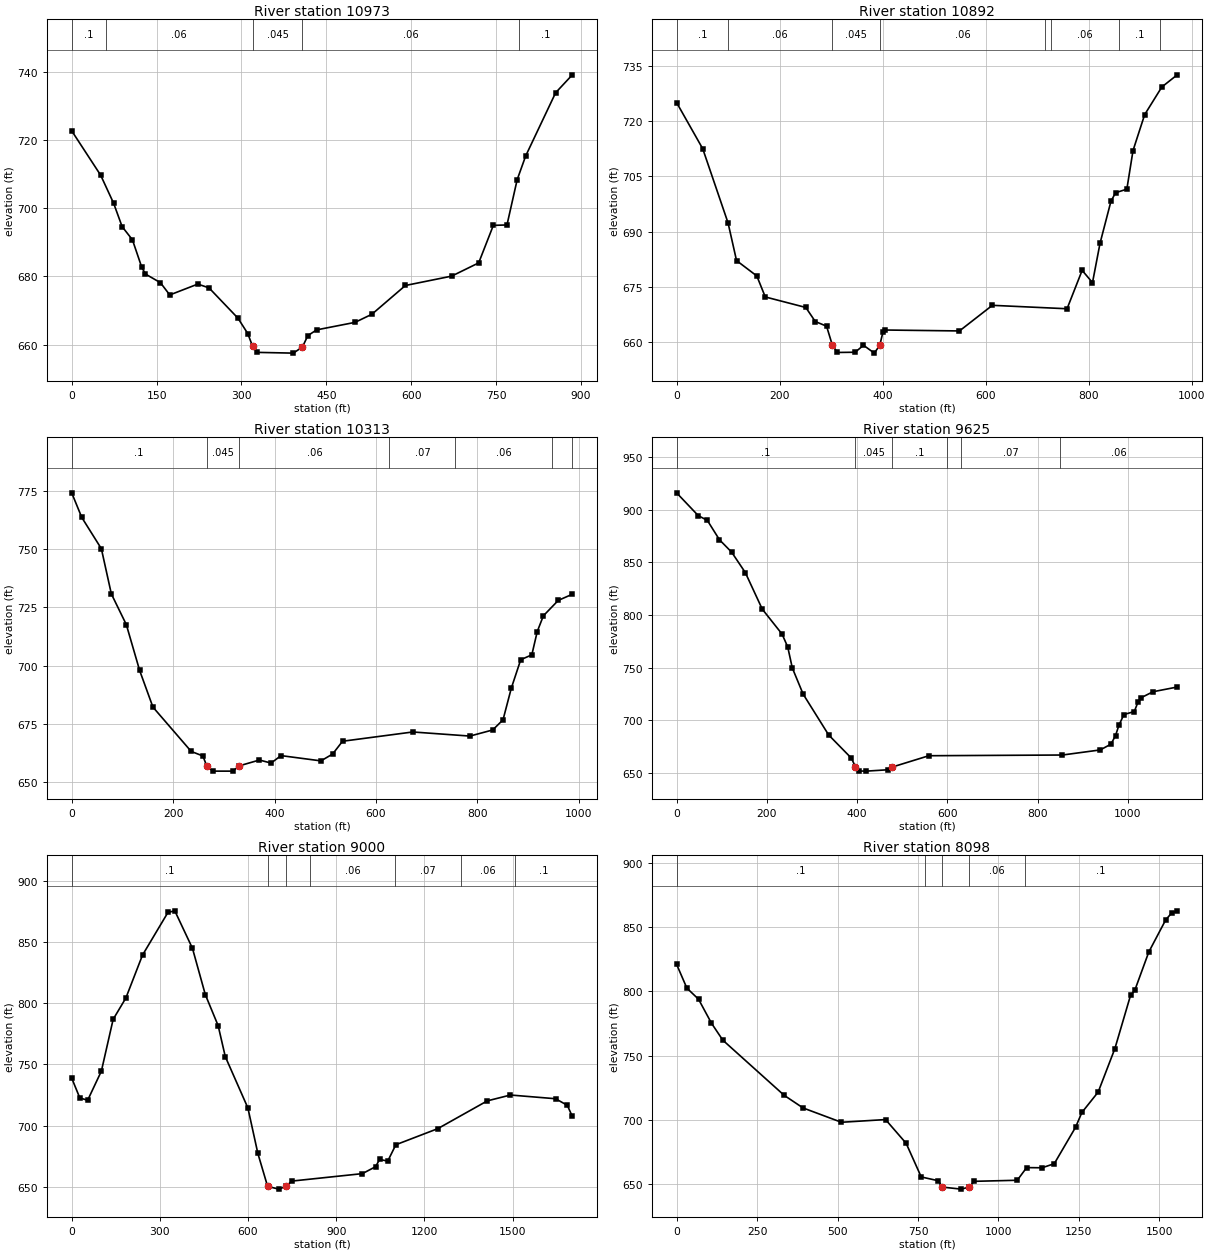
Type RM Length L Ch R = 1 ,10973   ,82.5,80.8,81.2
XS GIS Cut Line= 6
1624610.16644855507249.1583994151624583.16212796507506.599588974
1624304.11748194507636.2203277731624219.50394411507683.027816784
1624188.89904745507719.0335775621624275.31287331507870.257772828
#Sta/Elev= 30
       0  722.65    51.2  709.65    74.2  701.39    89.1  694.59   107.3  690.74
   123.8  682.68   130.4   680.7   156.8  678.17   173.3  674.58   222.8  677.76
   242.6  676.66   293.8  667.78   311.1  663.28  319.76659.5068   327.9  657.76
   391.7  657.54  407.77659.3492   417.3  662.66   432.8  664.35   500.7  666.55
   530.5  668.93   589.7  677.35   671.4  680.09   719.2  683.97   745.1  694.96
   769.2  695.08   787.2  708.33   802.3  715.31   855.2  733.81   884.7  739.05
#Mann= 5 ,-1,0
       0      .1       0      60     .06       0  319.76    .045       0
  407.77     .06       0  790.49      .1       0
Bank Sta=319.76,407.77
XS Rating Curve= 0 ,0
Exp/Cntr(USF)=0,0
Exp/Cntr=0.3,0.1

Type RM Length L Ch R = 1 ,10892   ,603.7,579.5,516.6
XS GIS Cut Line= 5
 1624561.5586715507232.9558070651624556.15780738 507432.78777938
1624185.29847137507621.8180234621624088.08291727507711.832425406
1624197.90048764507906.263533605
#Sta/Elev= 30
       0  724.98    50.8  712.46     100  692.34   116.4  682.17   155.8     678
   172.2  672.32   250.9  669.47   269.3  665.66   291.2   664.4   302.5  659.23
   312.3  657.28   346.7  657.34   362.9  659.23   383.9   657.1   394.5  659.22
   400.9  662.95   405.6  663.36   549.2  663.11   613.1  670.05   758.1  669.12
   787.4  679.52   807.5   676.2   822.1  686.84   843.3  698.23   852.3  700.55
   874.2  701.52   886.2  711.98   908.8  721.71   942.1  729.19     972  732.49
#Mann= 8 ,-1,0
       0      .1       0     100     .06       0   302.5    .045       0
   394.5     .06       0  716.16     .07       0  726.16     .06       0
  858.65      .1       0  938.65     .06       0
Bank Sta=302.5,394.5
XS Rating Curve= 0 ,0
Exp/Cntr(USF)=0,0
Exp/Cntr=0.3,0.1

Type RM Length L Ch R = 1 ,10313   ,717.9,688,619.1
XS GIS Cut Line= 3
1623909.71315391507021.7834783451623904.50019832507598.463238439
1624174.13492945507908.226002079
#Sta/Elev= 30
       0  774.21    19.9  763.63    58.5  750.22    78.2  730.81   107.7  717.64
     134  697.94   160.2  682.21   235.7  663.18   258.7  661.23  266.25  657.03
   278.2  654.72   317.7  654.72   330.8  657.01   370.2  659.49   393.2  658.18
   412.9  661.38   491.6  659.12   514.6  662.06   534.2  667.55   672.7  671.53
   785.4  669.77   830.4   672.4   850.7  676.76     867  690.31   885.6  702.55
   907.5  704.65   918.2  714.66   930.3  721.42   959.7  728.03   987.4  730.67
#Mann= 7 ,-1,0
       0      .1       0  266.25    .045       0   330.8     .06       0
   626.7     .07       0   756.7     .06       0   946.7      .1       0
   986.7     .06       0
Bank Sta=266.25,330.8
XS Rating Curve= 0 ,0
Exp/Cntr(USF)=0,0
Exp/Cntr=0.3,0.1

Type RM Length L Ch R = 1 ,9625    ,635.9,624.9,600.5
XS GIS Cut Line= 3
 1623108.8929194507651.3591344061624058.29300874507865.414857467
1624176.65323207507933.409028322
#Sta/Elev= 30
       0  916.08      48  894.43    68.2  889.86    95.1  871.44     122  859.71
   152.3  840.32   189.9  805.54   233.9  781.75   246.4  769.51   256.5  749.64
   280.5  724.76   337.2  685.87   387.7  663.78   396.5655.4175   404.5  651.66
   420.5  651.55   468.4  652.83   478.3655.4765   559.2  666.19   855.2  666.86
   939.2  671.71   962.8   677.2   972.9  685.27   980.4  695.08   991.5  705.31
  1014.5  708.19  1022.7  717.05  1029.9  721.38  1056.1  727.02  1109.7  731.49
#Mann= 6 ,-1,0
       0      .1       0   396.5    .045       0   478.3      .1       0
     600     .06       0     630     .07       0     850     .06       0
Bank Sta=396.5,478.3
XS Rating Curve= 0 ,0
Exp/Cntr(USF)=0,0
Exp/Cntr=0.3,0.1

Type RM Length L Ch R = 1 ,9000    ,889.8,902.1,895.5
XS GIS Cut Line= 6
1622931.77106485508492.4232734291623321.48714893508423.237388179
1623668.19872583508341.3336805851624099.25823118508202.826739758
1624240.38688593508263.6704500911624517.89748576508468.374765083
#Sta/Elev= 30
       0  738.77    27.6  722.55    54.3  720.65     101  744.47     141  786.76
   184.3  804.21   240.9  839.27   327.4  874.13   350.8  875.46   410.9  844.81
   454.6     807   498.3  781.61   522.6  756.29   599.5  714.35   633.3  677.29
   666.5650.3024   704.2  648.01     730   650.3     748  654.56     989  660.67
  1033.9  666.33  1047.7   672.3  1075.3   670.9  1102.9  684.28  1245.6  697.44
  1414.1  720.15  1492.9  724.92  1646.4  721.89  1686.3  716.51  1703.4   707.4
#Mann= 7 ,-1,0
       0      .1       0   666.5    .045       0     730      .1       0
  812.09     .06       0 1099.02     .07       0 1324.86     .06       0
 1508.55      .1       0
Bank Sta=666.5,730
XS Rating Curve= 0 ,0
Exp/Cntr(USF)=0,0
Exp/Cntr=0.3,0.1

Type RM Length L Ch R = 1 ,8098    ,740.6,759.4,751.1
XS GIS Cut Line= 3
1623306.96745731508828.2840550771623787.72590773509172.530192359
1624731.42995228508974.714497281
#Sta/Elev= 30
       0   821.2    31.9  802.63    68.2  793.94   108.4  775.22   143.7  761.97
   334.2  718.96   392.9   709.1   512.1  697.92   649.2  700.03   713.2  681.52
   760.1  655.26   813.2  652.29   825.5 647.345   884.2  645.75   909.6 647.358
   924.4  651.84  1058.5  652.67  1087.6  662.54  1135.6  662.41  1173.5   665.6
  1239.5  693.95  1259.4   705.6  1309.9  721.51  1361.7  755.34  1410.4  796.91
  1423.8  800.99  1467.2   830.8  1519.9  855.92  1537.8   861.1  1555.5  862.91
#Mann= 5 ,-1,0
       0      .1       0   771.3     .06       0   825.5    .045       0
   909.6     .06       0  1081.3      .1       0
Bank Sta=825.5,909.6
XS Rating Curve= 0 ,0
Exp/Cntr(USF)=0,0
Exp/Cntr=0.3,0.1

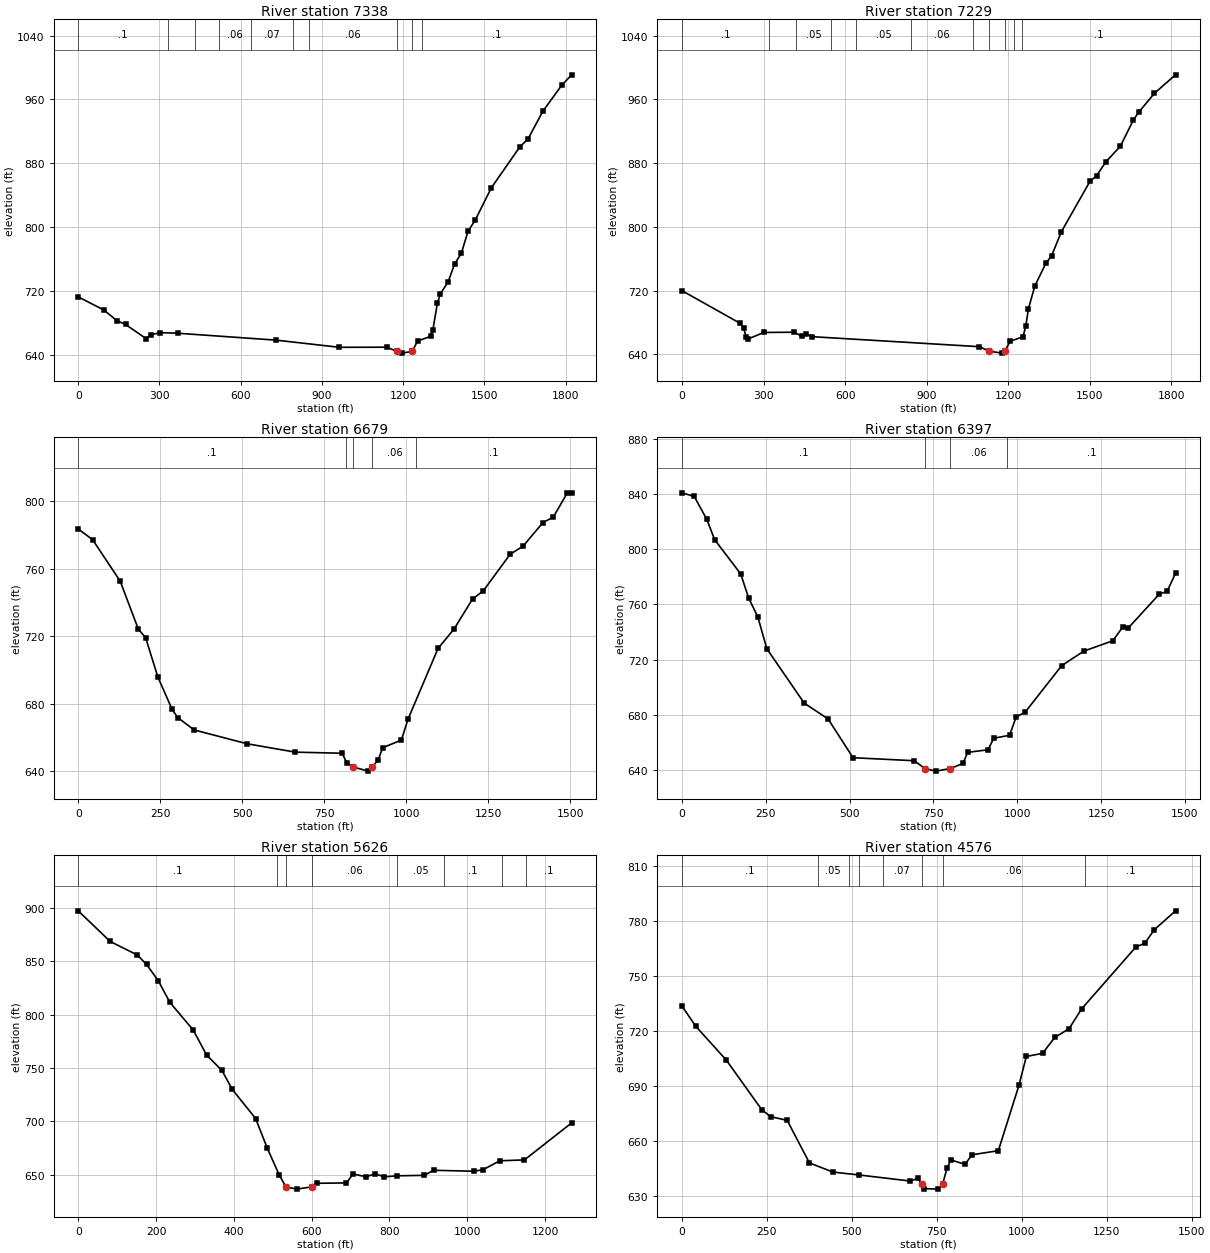
Type RM Length L Ch R = 1 ,7338    ,108.1,109.9,109.2
XS GIS Cut Line= 6
1623234.53305928510003.0253198691623506.73661076509768.087730795
 1624036.5613806509823.1765447851624275.17699054509714.348349709
1624525.98893985509759.2136519781624931.53094735509726.085199758
#Sta/Elev= 30
       0   712.5    94.7  696.02   142.9  682.65     175  677.91   250.4   660.2
   268.6  664.95   303.3  667.67   369.5  666.86   732.3   658.2   964.8  649.26
  1140.1  649.39  1175.8644.2982  1197.3  641.96  1233.8644.3052  1253.4  657.18
  1301.9  663.01    1310  671.46  1326.7  704.98  1337.9  716.46  1366.4  731.58
    1390  753.64    1415   767.2  1439.5  794.69    1466  808.61  1525.9  849.32
  1630.6   900.4  1661.7  910.74  1716.2  945.36  1785.3  977.61  1822.4   990.9
#Mann= 10 ,-1,0
       0      .1       0     330     .07       0  429.57     .05       0
  519.57     .06       0  639.57     .07       0   792.8     .05       0
   852.8     .06       0  1175.8    .045       0  1233.8     .06       0
 1270.74      .1       0
Bank Sta=1175.8,1233.8
XS Rating Curve= 0 ,0
Exp/Cntr(USF)=0,0
Exp/Cntr=0.3,0.1

Type RM Length L Ch R = 1 ,7229    ,544.8,549.1,551.4
XS GIS Cut Line= 6
 1623240.2039666510055.6837450061623512.40751808509820.746155932
1624042.23228792509875.8349699221624238.28365536509815.885378227
1624478.08202214509864.4931552771624933.37486717509746.214231123
#Sta/Elev= 30
       0  719.79   213.4  678.91   226.4  673.23   235.5  661.94   243.8  659.35
   300.4  667.41   413.3  667.72   439.7   662.7   456.2  665.81   477.9  662.13
  1093.4  649.58    1130643.9488    1177  641.48  1187.7643.9718  1206.3  656.28
    1254  662.02    1264  674.96  1274.1  697.23  1297.5  725.68  1337.7  753.97
  1359.6  763.98  1395.2  793.78  1500.3  857.02  1524.6  863.99  1558.7  881.48
  1612.2  901.12  1659.6  933.75    1679  943.45  1737.6  967.59    1815   990.7
#Mann= 11 ,-1,0
       0      .1       0     320     .07       0  419.57     .05       0
  549.57     .06       0  639.57     .05       0   842.8     .06       0
 1069.31     .07       0    1130    .045       0  1187.7     .07       0
  1219.9     .06       0  1249.9      .1       0
Bank Sta=1130,1187.7
XS Rating Curve= 0 ,0
Exp/Cntr(USF)=0,0
Exp/Cntr=0.3,0.1

Type RM Length L Ch R = 1 ,6679    ,280.8,282.5,276.1
XS GIS Cut Line= 4
1623299.94078665510278.9115922351623655.55323878510196.676212681
1624213.42027305510374.4824387431624766.84215167510352.256660485
#Sta/Elev= 30
       0  783.61    43.9   777.3   128.1  752.63   183.2  724.23   205.6  719.09
   242.6   695.9   286.4  676.51   303.2  671.74   353.7  664.35   515.3  656.15
   662.1  651.19   804.6  650.55   818.3  644.99   838.6642.3715   883.8  639.93
     897642.3535   914.7  646.75   928.5  653.84   985.4  658.37  1005.1   670.6
    1097  712.73  1146.2  724.38  1202.1  742.03  1234.9   746.9    1317  768.66
  1356.4  773.46  1416.7  787.41  1448.4   790.7    1491  805.01  1504.4  805.09
#Mann= 5 ,-1,0
       0      .1       0     815     .06       0   838.6    .045       0
     897     .06       0 1030.51      .1       0
Bank Sta=838.6,897
XS Rating Curve= 0 ,0
Exp/Cntr(USF)=0,0
Exp/Cntr=0.3,0.1

Type RM Length L Ch R = 1 ,6397    ,767.5,770.9,762.7
XS GIS Cut Line= 3
1623297.71820883510421.1565730841624242.31378478510661.194978268
1624735.72606211510594.517643495
#Sta/Elev= 30
       0  840.73    36.3  838.12    73.5   821.7    97.2  806.86   175.1  782.05
   198.8  764.57   225.9  751.11   252.9  727.99   364.6  688.61   435.7  677.23
   510.2  649.17     693  646.99     725641.2916   756.9  639.47   800.2641.3162
   838.6  645.09   852.1  653.04     913  654.91     930  663.24   977.3  665.41
   997.1  678.72  1023.6  682.04  1132.8  715.76  1199.1  726.27  1285.2  733.73
    1315  743.63  1331.2  742.88  1424.2  767.52  1447.4  769.42  1472.5  782.58
#Mann= 4 ,-1,0
       0      .1       0     725    .045       0   800.2     .06       0
     970      .1       0
Bank Sta=725,800.2
XS Rating Curve= 0 ,0
Exp/Cntr(USF)=0,0
Exp/Cntr=0.3,0.1

Type RM Length L Ch R = 1 ,5626    ,1043.2,1049.9,1061.3
XS GIS Cut Line= 2
1623255.35846258511224.4538130891624502.04932029511458.976868275
#Sta/Elev= 30
       0  897.52    82.2  868.78   152.3  856.02   175.7  847.16   205.8     832
   235.8  811.53   295.9  785.57   330.1  762.16   369.4  747.79     396  729.98
   456.1  702.61   486.2  674.73   516.2  650.09     534638.5308   562.5  636.38
   599.9638.5007     613  641.85   689.7  642.21   706.5  650.59   739.9  647.98
   763.3  650.75   786.6  647.91     820  648.86   890.1  649.33   913.5  654.06
    1017  653.18  1040.3  654.51  1083.7  662.96  1147.2  663.81  1268.6  698.54
#Mann= 8 ,-1,0
       0      .1       0     510     .06       0     534    .045       0
   599.9     .06       0     820     .05       0     940      .1       0
    1090     .08       0    1150      .1       0
Bank Sta=534,599.9
XS Rating Curve= 0 ,0
Exp/Cntr(USF)=0,0
Exp/Cntr=0.3,0.1

Type RM Length L Ch R = 1 ,4576    ,644.3,649.7,642
XS GIS Cut Line= 3
1622995.71429373512003.7966201641623818.21394375512453.042867989
1624183.41519178512816.604649471
#Sta/Elev= 30
       0  733.31    40.3  722.39     130  703.97   234.7  676.83   260.8  673.06
   309.4  671.03   374.9   647.8     444  642.81     520  641.25     672  637.91
   694.5   639.4     706636.0412   713.2  633.78   754.5   633.5   766.7636.0821
   780.5  645.28   791.7  649.43   832.8  647.03   853.6  652.25     931  654.48
   991.6  690.13  1013.3   705.9  1061.2  707.62    1097  716.29  1138.9     721
  1176.1  731.87  1335.7  765.62  1362.1  767.71    1390  775.07  1452.5  785.39
#Mann= 8 ,-1,0
       0      .1       0     400     .05       0     490     .07       0
     520     .06       0     590     .07       0     706    .045       0
   766.7     .06       0 1187.19      .1       0
Bank Sta=706,766.7
XS Rating Curve= 0 ,0
Exp/Cntr(USF)=0,0
Exp/Cntr=0.3,0.1

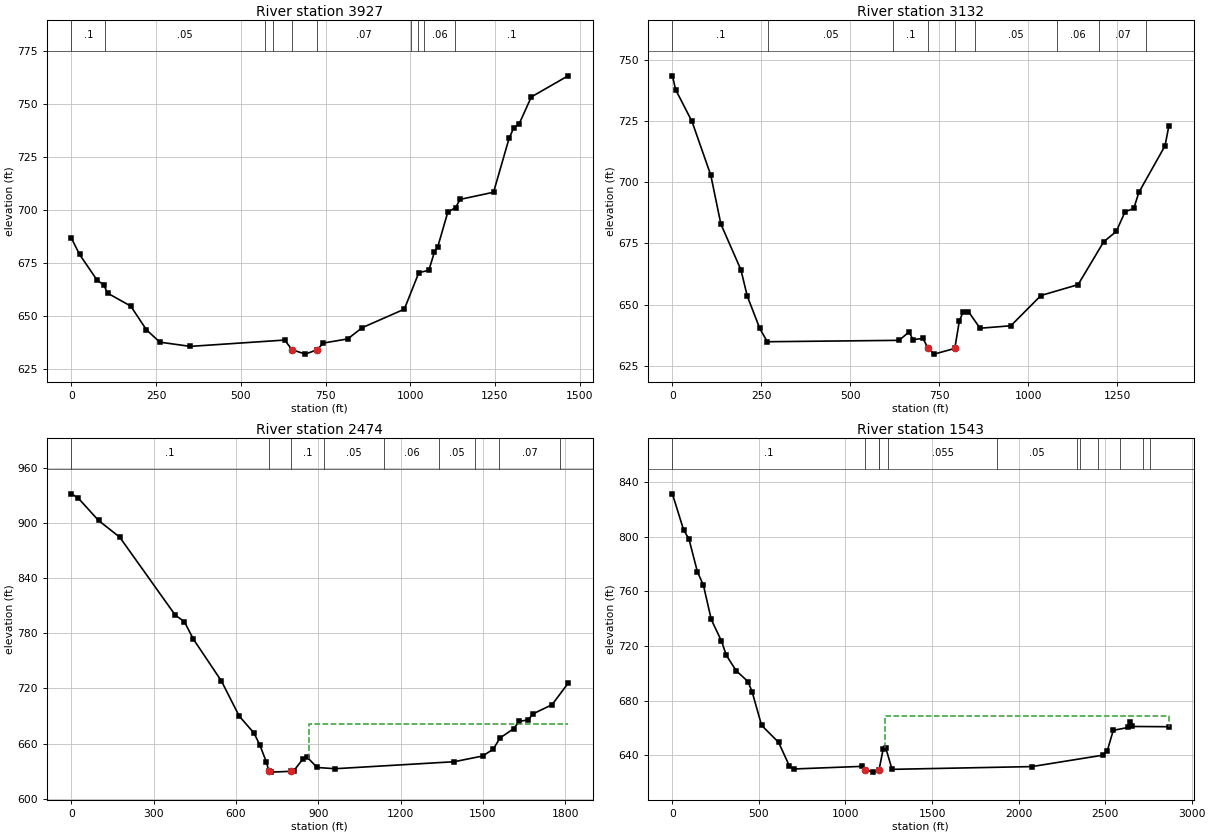
Type RM Length L Ch R = 1 ,3927    ,797.1,794.3,784.3
XS GIS Cut Line= 6
1622674.73349359512593.0097070021623209.41904114512831.187814546
1623452.45792639512964.0490718151623491.34414803 513007.79607116
1623522.12907349513059.6443666791624004.96632552513100.150847554
#Sta/Elev= 30
       0  686.79    23.7  679.22    75.3  667.12    95.6  664.79   106.3  660.96
     175  654.83   221.3  643.64   260.8  637.83   350.6  635.84   629.4  638.82
   650.8 634.291   690.4  632.19   725.5634.3043   743.1   637.4   815.4  639.35
   858.1  644.65   982.6  653.39  1025.4  670.59    1055  671.72  1071.5  680.35
  1081.6  682.93    1111  699.16    1134  701.29  1147.2  705.15    1246  708.52
    1292  733.98  1305.9  738.99  1321.7   740.8  1357.5  753.46    1466  763.41
#Mann= 10 ,-1,0
       0      .1       0     100     .05       0     570     .06       0
  595.34     .07       0   650.8    .045       0   725.5     .07       0
 1001.51     .06       0 1021.51     .07       0 1041.51     .06       0
 1131.51      .1       0
Bank Sta=650.8,725.5
XS Rating Curve= 0 ,0
Exp/Cntr(USF)=0,0
Exp/Cntr=0.3,0.1

Type RM Length L Ch R = 1 ,3132    ,646.3,658.6,663.8
XS GIS Cut Line= 2
1622366.34732692513341.8259761781623664.10515592513855.324873077
#Sta/Elev= 30
       0  743.39     9.2  737.72    55.1  724.76     108  702.81   136.2  682.91
   192.7  664.18   210.3  653.55   245.6  640.26   266.8  634.84   637.2  635.41
   665.5  638.87     676   635.7   704.3  636.17   718.8632.1839   735.8  629.78
   793.8632.1193   806.6  643.33   816.7  646.83   831.9  647.18   864.8  640.35
   951.3  641.36  1035.9  653.71  1140.3  658.14  1212.3  675.64  1247.6  679.86
  1272.3   687.9    1297  689.27  1311.1   695.8  1384.6   714.8  1395.7  723.11
#Mann= 9 ,-1,0
       0      .1       0     270     .05       0     620      .1       0
   718.8    .045       0   793.8      .1       0     850     .05       0
    1080     .06       0    1200     .07       0    1330      .1       0
Bank Sta=718.8,793.8
XS Rating Curve= 0 ,0
Exp/Cntr(USF)=0,0
Exp/Cntr=0.3,0.1

Type RM Length L Ch R = 1 ,2474    ,934.9,930.8,931.9
XS GIS Cut Line= 3
1622000.96063482513582.1288811311622675.08204234514117.460587104
1623610.13435431 514286.01511469
#Sta/Elev= 30
       0  931.97      25  927.18    98.5  902.98   175.9  884.77   378.7  799.76
   411.4  792.83   444.1  773.93   546.9  728.03   611.6  689.96     666  671.25
     687  658.28   710.3  640.24     720629.8075   728.9  628.91   799.1  629.79
   810.7  630.41   845.2  643.68   858.7  645.38   895.8  633.96   961.2  632.62
  1395.9  640.25  1499.2  646.47  1537.8  653.78  1562.6  666.01  1612.6  676.29
  1632.6   684.1  1665.9  685.86  1682.6  692.29  1752.6  702.38  1810.9  725.59
#Mann= 9 ,-1,0
       0      .1       0     720    .045       0   799.1      .1       0
  920.83     .05       0 1140.83     .06       0 1340.83     .05       0
 1470.83     .06       0 1560.83     .07       0 1780.83      .1       0
#XS Ineff= 2 , 0
                          867.16          681.73
Permanent Ineff=
       F       F
Bank Sta=720,799.1
XS Rating Curve= 0 ,0
Exp/Cntr(USF)=0,0
Exp/Cntr=0.3,0.1

Type RM Length L Ch R = 1 ,1543    ,,,
XS GIS Cut Line= 4
1621269.33289448513751.4025043921621474.83680611514340.974558924
1622353.48129521515006.910790656 1623420.3384615515414.144495175
#Sta/Elev= 30
       0  831.49    64.7  805.13      96   798.3   144.6  774.37   179.4  764.53
   224.5  739.51   283.6   723.7   311.4  713.32   368.6  701.98   436.5  694.06
   460.8   686.5   515.4  661.97   613.7  649.52   676.5   632.1   699.9  630.03
  1095.7  631.95  1110.2629.5986  1158.9  627.73 1194.12629.5524  1217.4  644.36
  1232.2  645.72    1269  629.77  2076.4  631.78    2488  640.16  2511.8  642.99
  2546.9  658.32  2634.7  660.49  2645.3   664.1  2655.8  661.16  2868.8  660.97
#Mann= 12 ,-1,0
       0      .1       0  1110.2    .045       0 1194.12      .1       0
 1194.36     .08       0 1244.36    .055       0 1876.85     .05       0
 2336.85     .06       0 2356.85     .07       0 2456.85     .05       0
 2586.85     .07       0 2716.85     .08       0 2756.85      .1       0
#XS Ineff= 2 , 0
                         1230.42          669.16
Permanent Ineff=
       F       F
Bank Sta=1110.2,1194.12
XS Rating Curve= 0 ,0
Exp/Cntr(USF)=0,0
Exp/Cntr=0.3,0.1
LCMann Table=0

Chan Stop Cuts=-1
Use User Specified Reach Order=0
Composite Channel Slope=5